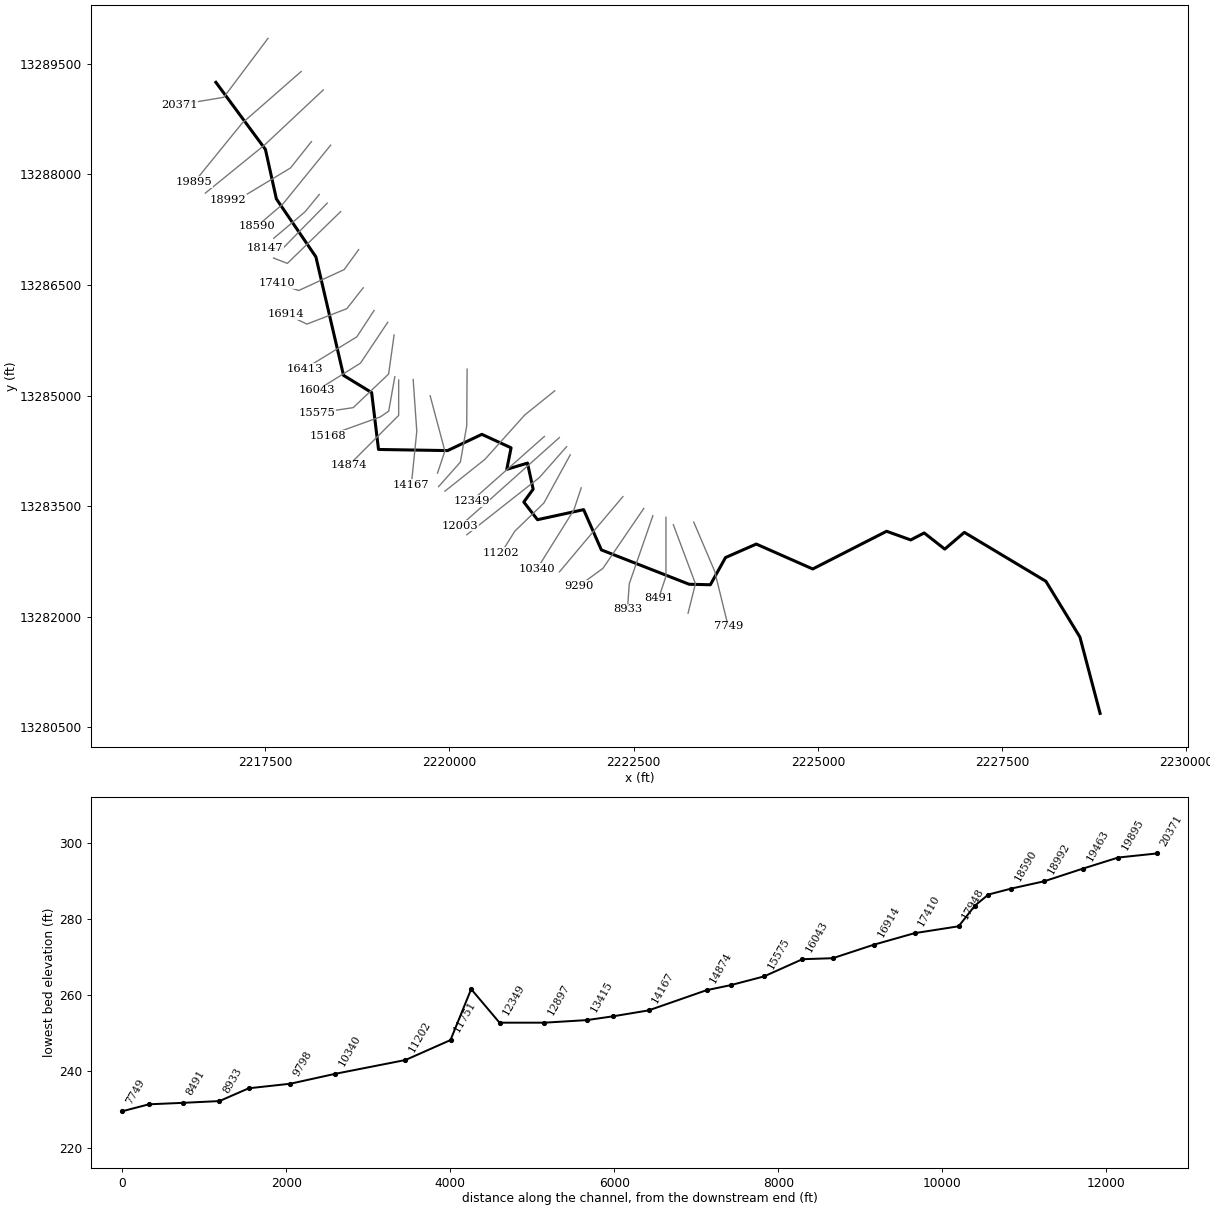
--- UNT014 IN SPCR.prj (project) ---

Proj Title=UNT014 IN SPCR Base Level Engineering
Current Plan=p01
Default Exp/Contr=0.3,0.1
English Units
Geom File=g01
Flow File=f01
Plan File=p01
Y Axis Title=Elevation
X Axis Title(PF)=Main Channel Distance
X Axis Title(XS)=Station
BEGIN DESCRIPTION:
UNT014 IN SPCR
END DESCRIPTION:
DSS Export Rating Curves= 0
DSS Export Rating Curve Sorted= 0
DSS Export Volume Flow Curves= 0
DXF OffsetX= 0
DXF OffsetY= 0
DXF ScaleX= 1
DXF ScaleY= 10

--- UNT014 IN SPCR.p01 (plan) ---

Plan Title=Multiple Run
Short Identifier=Multiple
Geom File=g01
Flow File=f01
Subcritical Flow
K Sum by GR= 0
Std Step Tol= 0.01
Critical Tol= 0.01
Num of Std Step Trials= 20
Max Error Tol= 0.3
Flow Tol Ratio= 0.001
Split Flow NTrial= 30
Split Flow Tol= 0.02
Split Flow Ratio= 0.02
Log Output Level= 0
Friction Slope Method= 1
Unsteady Friction Slope Method= 2
Unsteady Bridges Friction Slope Method= 1
Parabolic Critical Depth
Global Vel Dist=  1 , 1 , 1
Global Log Level= 0
CheckData=True
Encroach Param= -1, 0, 0, 0
BEGIN DESCRIPTION:
Multiple Run
END DESCRIPTION:

--- UNT014 IN SPCR.f01 (steady flow) ---

Flow Title=Multiple
Program Version=4.10
Number of Profiles= 7
Profile Names=10-year,25-year,50-year,1pct_min,100-year,1pct_plu,500-year
River Rch & RM=UNT014 IN SPCR,Reach-1         ,20371
     332     468     583     534     722     976    1125
River Rch & RM=UNT014 IN SPCR,Reach-1         ,12897
     402     573     717     660     893    1207    1405
River Rch & RM=UNT014 IN SPCR,Reach-1         ,4053
     490     702     883     816    1103    1492    1750
River Rch & RM=UNT014 IN SPCR,Reach-1         ,3802
     490     702     883     816    1103    1492    1750
Boundary for River Rch & Prof#=UNT014 IN SPCR,Reach-1         , 1
Up Type= 0
Dn Type= 3
Dn Slope=0.005
Boundary for River Rch & Prof#=UNT014 IN SPCR,Reach-1         , 2
Up Type= 0
Dn Type= 3
Dn Slope=0.005
Boundary for River Rch & Prof#=UNT014 IN SPCR,Reach-1         , 3
Up Type= 0
Dn Type= 3
Dn Slope=0.005
Boundary for River Rch & Prof#=UNT014 IN SPCR,Reach-1         , 4
Up Type= 0
Dn Type= 3
Dn Slope=0.005
Boundary for River Rch & Prof#=UNT014 IN SPCR,Reach-1         , 5
Up Type= 0
Dn Type= 3
Dn Slope=0.005
Boundary for River Rch & Prof#=UNT014 IN SPCR,Reach-1         , 6
Up Type= 0
Dn Type= 3
Dn Slope=0.005
Boundary for River Rch & Prof#=UNT014 IN SPCR,Reach-1         , 7
Up Type= 0
Dn Type= 3
Dn Slope=0.005
DSS Import GetInterval= 0
DSS Import GetPeak= 0
DSS Import FillOption= 0

--- UNT014 IN SPCR.g01 (geometry) ---

Geom Title=Existing Conditions
Program Version=4.10

River Reach=UNT014 IN SPCR  ,Reach-1
Reach XY= 30
      2216830.41     13289249.95      2217502.72      13288339.5
      2217651.13     13287668.28      2218187.37     13286881.71
      2218562.22     13285273.89      2218943.86     13285040.05
      2219037.22     13284267.95       2219974.9     13284252.95
      2220440.01     13284473.26      2220836.03     13284290.45
      2220777.68     13283998.52      2221058.71     13284083.16
      2221135.32     13283729.21      2221008.58     13283554.73
      2221194.35     13283315.14      2221820.61     13283451.44
      2222061.11      13282905.2      2223252.79     13282438.86
       2223540.1     13282432.39      2223745.84     13282801.63
      2224163.14     13282984.33       2224929.3     13282646.51
      2225931.33     13283158.03      2226258.48     13283040.57
      2226442.01       13283135.      2226720.74     13282916.14
      2226986.36     13283142.98      2228092.88     13282479.58
      2228554.89      13281722.7      2228828.62     13280686.97

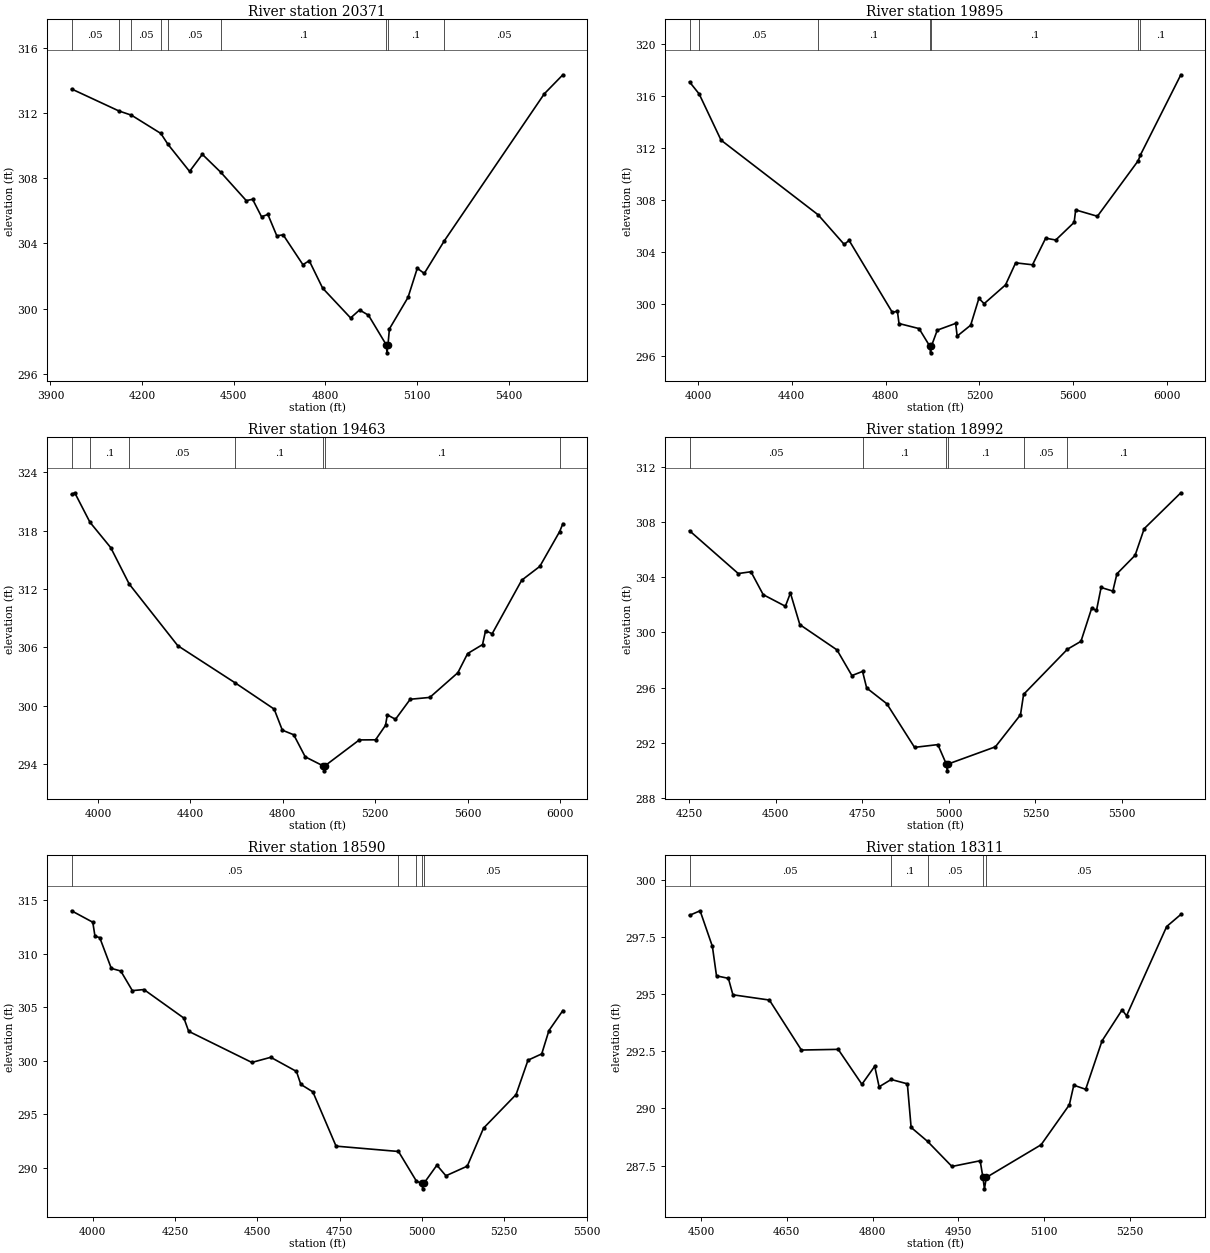
Type RM Length L Ch R = 1 ,20371   ,476,476,476
BEGIN DESCRIPTION:
UNT014 IN SPCR 42.0
END DESCRIPTION:
XS GIS Cut Line= 3
      2217537.71     13289846.84      2216937.72     13289046.85
      2216337.67     13288946.85
#Sta/Elev= 30
  3969.1  313.48  4124.1  312.13  4165.3  311.87  4261.4  310.75  4284.4  310.09
  4355.5  308.42  4397.2  309.47    4458  308.36    4541  306.63  4561.8  306.71
    4591  305.64  4611.8  305.78    4641  304.47  4661.8  304.53  4726.4   302.7
  4747.2  302.94    4791  301.26  4882.6  299.43  4911.8  299.92    4941   299.6
    4999  297.79  5001.8  297.29    5005  297.79  5009.6  298.76  5070.5  300.69
  5100.9  302.48  5123.7  302.16  5188.9  304.15  5516.5  313.18  5577.4  314.35
#Mann= 9 ,-1 , 0
  3969.1     .05       0  4124.1      .1       0  4165.3     .05       0
  4261.4      .1       0  4284.4     .05       0    4458      .1       0
    4999     .07       0    5005      .1       0  5188.9     .05       0
Bank Sta=4999,5005
XS Rating Curve= 0 ,0
Exp/Cntr=0.3,0.1

Type RM Length L Ch R = 1 ,19895   ,432,432,432
BEGIN DESCRIPTION:
UNT014 IN SPCR 41.0
END DESCRIPTION:
XS GIS Cut Line= 3
      2217987.72     13289396.86      2217187.72     13288696.85
      2216537.72     13287896.85
#Sta/Elev= 30
  3964.4   317.1  4005.5  316.17  4098.7  312.61  4512.7  306.85  4623.6  304.57
  4644.4  304.88  4828.6  299.33  4850.4  299.42  4857.1  298.47  4942.5  298.08
  4988.8  296.71  4991.6  296.21  4994.8  296.71  5020.3  297.96  5098.5  298.48
    5105   297.5  5162.5  298.34  5197.6  300.41  5219.9     300  5311.1  301.45
  5354.2  303.15  5426.1     303  5482.1  305.05  5525.2  304.91  5603.5  306.27
    5610  307.23  5702.6  306.74  5876.3  311.02  5885.7  311.46  6058.2  317.65
#Mann= 7 ,-1 , 0
  3964.4      .1       0  4005.5     .05       0  4512.7      .1       0
  4988.8     .07       0  4994.8      .1       0  5876.3     .05       0
  5885.7      .1       0
Bank Sta=4988.8,4994.8
XS Rating Curve= 0 ,0
Exp/Cntr=0.3,0.1

Type RM Length L Ch R = 1 ,19463   ,471,471,471
BEGIN DESCRIPTION:
UNT014 IN SPCR 40.0
END DESCRIPTION:
XS GIS Cut Line= 3
      2218287.72     13289146.85      2217487.72     13288396.85
      2216687.69     13287746.83
#Sta/Elev= 30
  3885.4  321.71  3899.3  321.88  3965.1  318.85  4055.1  316.24    4135   312.5
  4345.3  306.16  4594.9  302.32  4762.7  299.64  4798.1  297.47  4847.4     297
  4897.2  294.73  4975.6  293.79  4978.3  293.29  4981.6  293.79  5131.4  296.47
  5201.8  296.48  5244.9  297.97  5252.6  299.05    5288  298.59  5351.9  300.65
  5436.7  300.84  5558.1  303.38  5600.4  305.35  5664.9  306.27    5678  307.69
  5706.7  307.39  5834.6  312.89  5912.9  314.31  5998.8  317.89  6012.8   318.7
#Mann= 7 ,-1 , 0
  3885.4     .05       0  3965.1      .1       0    4135     .05       0
  4594.9      .1       0  4975.6     .07       0  4981.6      .1       0
  5998.8     .05       0
Bank Sta=4975.6,4981.6
XS Rating Curve= 0 ,0
Exp/Cntr=0.3,0.1

Type RM Length L Ch R = 1 ,18992   ,402,402,402
BEGIN DESCRIPTION:
UNT014 IN SPCR 39.0
END DESCRIPTION:
XS GIS Cut Line= 4
      2218127.23     13288445.93      2217843.83     13288088.59
      2217190.79     13287694.31      2216993.64     13287657.34
#Sta/Elev= 30
  4250.8  307.36  4391.6  304.26  4428.3  304.39  4463.7  302.73  4527.8  301.89
  4542.3  302.85  4569.5  300.56  4676.8  298.73  4719.9  296.87  4750.7  297.17
  4762.6  295.97  4820.8  294.83  4900.9  291.67  4968.3  291.87  4992.5  290.47
  4995.2  289.97  4998.5  290.47  5134.5  291.71    5207  294.03    5216  295.51
  5342.7  298.78  5381.7  299.35  5412.7  301.75  5426.6  301.59  5439.9  303.25
  5473.8  302.99  5485.6  304.24  5538.1  305.58  5564.4  307.51  5670.3  310.11
#Mann= 6 ,-1 , 0
  4250.8     .05       0  4750.7      .1       0  4992.5     .07       0
  4998.5      .1       0    5216     .05       0  5342.7      .1       0
Bank Sta=4992.5,4998.5
XS Rating Curve= 0 ,0
Exp/Cntr=0.3,0.1

Type RM Length L Ch R = 1 ,18590   ,279,279,279
BEGIN DESCRIPTION:
UNT014 IN SPCR 38.0
END DESCRIPTION:
XS GIS Cut Line= 3
      2218387.75     13288396.89      2217737.72     13287596.85
      2217387.72     13287296.85
#Sta/Elev= 30
  3936.2  314.03  4000.7  312.96  4007.4  311.64  4021.7  311.53  4056.9  308.65
  4085.7   308.4  4120.8  306.57    4156  306.67  4277.4     304  4291.8  302.77
  4483.6  299.86  4541.1  300.34  4619.1  299.02  4632.3  297.81  4668.9  297.11
  4739.3  292.04  4928.9  291.54  4983.3  288.77  4999.7  288.55  5002.4  288.05
  5005.7  288.55  5045.5  290.26  5072.9  289.27  5137.7  290.17  5187.1  293.72
  5285.9  296.86  5322.1  300.07  5363.8  300.66  5385.7  302.84    5428  304.71
#Mann= 5 ,-1 , 0
  3936.2     .05       0  4928.9      .1       0  4983.3     .05       0
  4999.7     .03       0  5005.7     .05       0
Bank Sta=4999.7,5005.7
XS Rating Curve= 0 ,0
Exp/Cntr=0.3,0.1

Type RM Length L Ch R = 1 ,18311   ,164,164,164
BEGIN DESCRIPTION:
Mapping XS 9a310c19
END DESCRIPTION:
XS GIS Cut Line= 3
      2218233.13     13287727.77      2218040.42     13287493.39
      2217615.95     13287134.02
#Sta/Elev= 30
  4479.8  298.46  4498.3  298.66  4519.8   297.1    4527  295.81  4547.8   295.7
  4555.7  294.98  4619.5  294.75  4675.5  292.56  4739.9  292.59  4781.4  291.06
  4803.8  291.85  4811.5  290.95  4832.6  291.27  4860.9  291.08  4867.5  289.17
  4896.2  288.56  4938.9  287.46  4988.3  287.71  4993.1  286.98  4995.8  286.48
  4999.1  286.98  5094.9  288.41  5144.3  290.16  5152.1  291.02  5172.9  290.84
  5201.5  292.96  5236.6  294.32  5244.4  294.06  5314.6  297.97  5339.4   298.5
#Mann= 5 ,-1 , 0
  4479.8     .05       0  4832.6      .1       0  4896.2     .05       0
  4993.1     .03       0  4999.1     .05       0
Bank Sta=4993.1,4999.1
XS Rating Curve= 0 ,0
Exp/Cntr=0.3,0.1

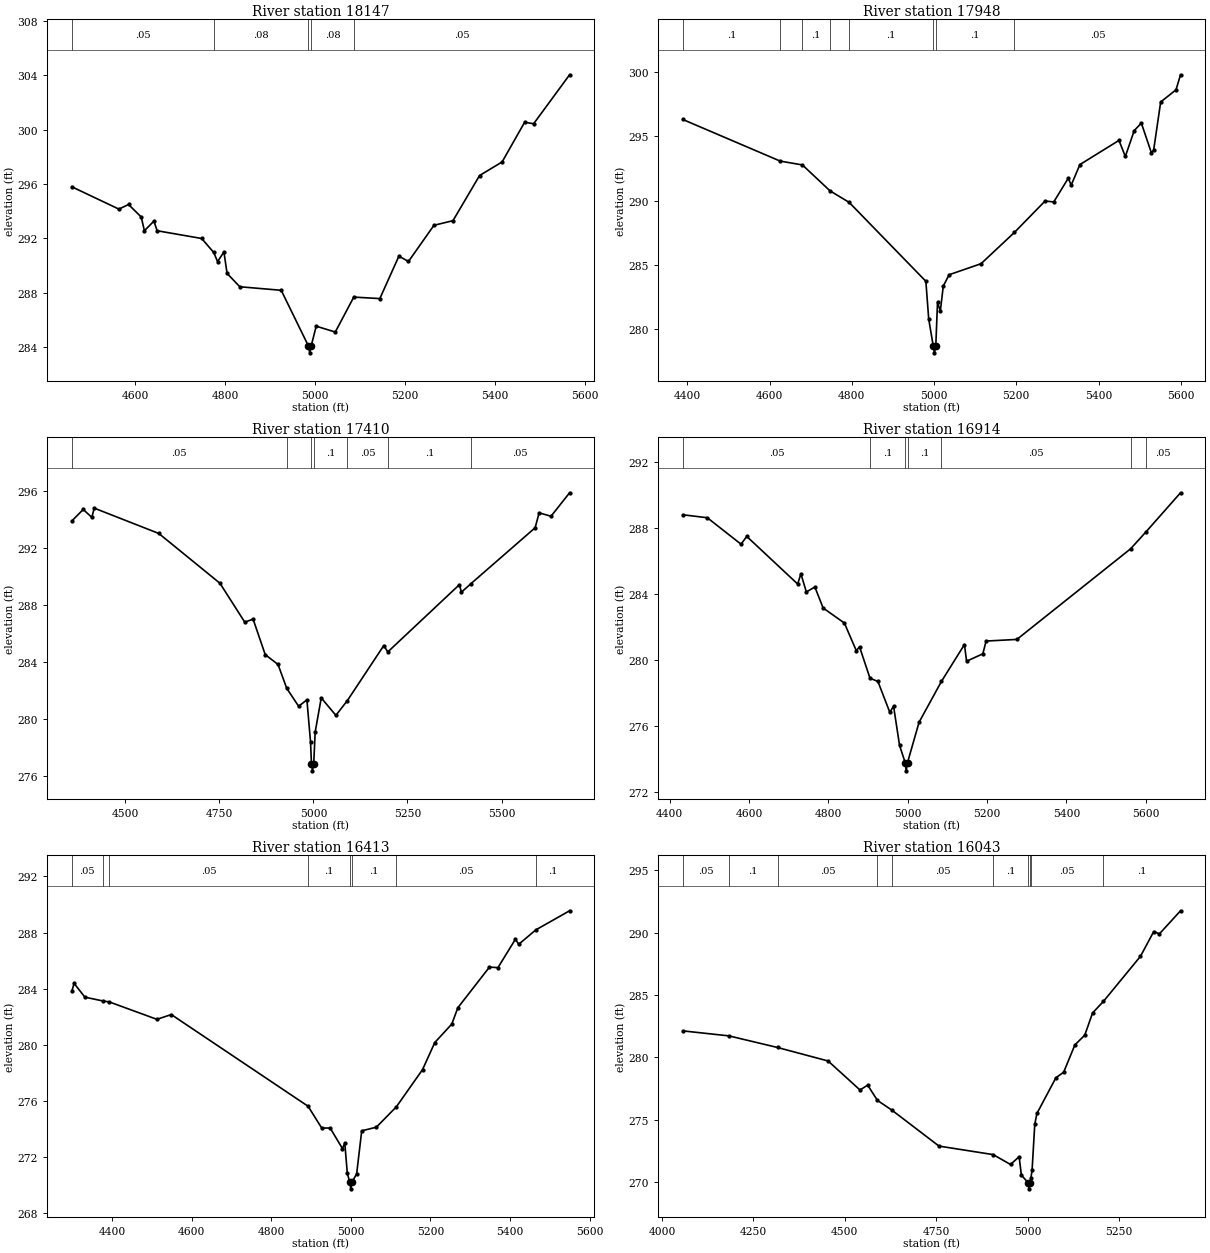
Type RM Length L Ch R = 1 ,18147   ,199,199,199
BEGIN DESCRIPTION:
UNT014 IN SPCR 37.0
END DESCRIPTION:
XS GIS Cut Line= 3
      2218341.85     13287610.72      2217727.25      13286985.7
      2217498.05     13287001.33
#Sta/Elev= 30
  4459.5  295.79  4564.1  294.15  4585.4  294.49  4613.7  293.57  4620.7  292.56
  4641.9  293.27    4649  292.56    4748  291.99  4774.6  290.97  4783.4  290.29
  4797.5     291  4804.5  289.42  4832.8  288.44  4924.8  288.18  4985.4  284.08
  4988.2  283.58  4991.4  284.08  5002.6  285.54    5045  285.11  5086.1  287.68
    5144  287.57  5186.4  290.69  5207.7   290.3  5264.3  292.96  5306.6   293.3
  5365.7  296.62  5415.8  297.62  5465.9  300.54  5485.9  300.43  5565.8  304.03
#Mann= 5 ,-1 , 0
  4459.5     .05       0  4774.6     .08       0  4985.4     .07       0
  4991.4     .08       0  5086.1     .05       0
Bank Sta=4985.4,4991.4
XS Rating Curve= 0 ,0
Exp/Cntr=0.3,0.1

Type RM Length L Ch R = 1 ,17948   ,538,538,538
BEGIN DESCRIPTION:
UNT014 IN SPCR 36.0
END DESCRIPTION:
XS GIS Cut Line= 3
      2218524.15     13287496.14      2217800.17     13286792.99
      2217612.69      13286865.9
#Sta/Elev= 30
    4389  296.31  4625.8  293.07  4679.9  292.77  4747.1  290.75  4793.4  289.86
  4980.1  283.71    4987  280.78  4998.2  278.64  5000.9  278.14  5004.2  278.64
  5008.4  282.07  5015.3   281.4  5022.5  283.34  5036.6  284.22  5114.3  285.08
  5195.3  287.51    5270  289.96  5291.1  289.89  5326.5  291.74  5333.5   291.2
  5354.8   292.8  5449.7  294.68  5465.2  293.43  5486.7  295.44  5504.1  296.03
  5528.7   293.7    5534  293.92  5551.1  297.67  5588.4  298.62  5599.4  299.79
#Mann= 8 ,-1 , 0
    4389      .1       0  4625.8     .05       0  4679.9      .1       0
  4747.1     .05       0  4793.4      .1       0  4998.2     .07       0
  5004.2      .1       0  5195.3     .05       0
Bank Sta=4998.2,5004.2
XS Rating Curve= 0 ,0
Exp/Cntr=0.3,0.1

Type RM Length L Ch R = 1 ,17410   ,496,496,496
BEGIN DESCRIPTION:
UNT014 IN SPCR 35.0
END DESCRIPTION:
XS GIS Cut Line= 4
      2218767.96      13286979.7      2218570.79     13286708.59
      2217954.72      13286425.2      2217660.86     13286523.16
#Sta/Elev= 30
  4357.9   293.9  4388.1  294.71  4410.9  294.15  4417.4   294.8    4589  293.02
  4751.5  289.52  4817.6  286.78  4839.6     287  4871.9   284.5  4905.9  283.81
  4929.1  282.13  4960.7  280.87  4982.7  281.32  4992.3  278.37  4994.8  276.83
  4997.5  276.33  5000.8  276.83  5004.7  279.06  5020.8  281.46  5059.7  280.23
    5090  281.26  5187.1  285.14  5197.7  284.69  5388.1  289.42  5393.4  288.89
  5419.2   289.5  5589.4  293.42    5600  294.47  5631.6  294.23    5681  295.88
#Mann= 7 ,-1 , 0
  4357.9     .05       0  4929.1      .1       0  4994.8     .07       0
  5000.8      .1       0    5090     .05       0  5197.7      .1       0
  5419.2     .05       0
Bank Sta=4994.8,5000.8
XS Rating Curve= 0 ,0
Exp/Cntr=0.3,0.1

Type RM Length L Ch R = 1 ,16914   ,501,501,501
BEGIN DESCRIPTION:
UNT014 IN SPCR 34.0
END DESCRIPTION:
XS GIS Cut Line= 4
      2218829.52     13286462.14      2218607.75     13286178.77
      2218065.61     13285969.31      2217782.46     13286104.73
#Sta/Elev= 30
    4433  288.79  4494.8  288.61  4579.8  287.01  4594.3  287.48  4722.6   284.6
  4730.8  285.22  4744.5  284.12    4766  284.42  4786.8  283.15  4840.4  282.24
  4870.4  280.57  4878.6   280.8    4905   278.9  4924.9  278.71  4954.9  276.84
  4964.4  277.21  4979.5  274.84  4993.6   273.8  4996.3   273.3  4999.6   273.8
  5028.7  276.24  5085.1  278.71  5143.1  280.94  5148.5  279.93  5189.5  280.38
  5197.7  281.15  5275.3  281.25    5562  286.73  5600.6  287.75  5687.9  290.12
#Mann= 7 ,-1 , 0
    4433     .05       0    4905      .1       0  4993.6     .07       0
  4999.6      .1       0  5085.1     .05       0    5562      .1       0
  5600.6     .05       0
Bank Sta=4993.6,4999.6
XS Rating Curve= 0 ,0
Exp/Cntr=0.3,0.1

Type RM Length L Ch R = 1 ,16413   ,370,370,370
BEGIN DESCRIPTION:
UNT014 IN SPCR 33.0
END DESCRIPTION:
XS GIS Cut Line= 3
       2218977.4     13286154.14      2218743.29     13285796.81
      2218041.86     13285366.11
#Sta/Elev= 30
  4299.3  283.83  4304.9  284.38    4332   283.4  4376.9  283.13  4393.3  283.06
  4512.9  281.82  4549.1  282.16  4892.7  275.63  4926.9  274.08  4948.1  274.08
    4979  272.62  4984.9  273.01  4991.2  270.85  4997.3  270.25    5000  269.75
  5003.3  270.25  5014.7  270.82  5027.4  273.88  5064.2  274.14  5114.4  275.59
  5180.2  278.24    5211  280.17  5253.6  281.48    5269  282.65  5348.3  285.54
  5369.6   285.5  5413.6  287.53  5421.7  287.16  5464.8  288.19  5549.6  289.55
#Mann= 8 ,-1 , 0
  4299.3     .05       0  4376.9      .1       0  4393.3     .05       0
  4892.7      .1       0  4997.3     .07       0  5003.3      .1       0
  5114.4     .05       0  5464.8      .1       0
Bank Sta=4997.3,5003.3
XS Rating Curve= 0 ,0
Exp/Cntr=0.3,0.1

Type RM Length L Ch R = 1 ,16043   ,468,468,468
BEGIN DESCRIPTION:
UNT014 IN SPCR 32.0
END DESCRIPTION:
XS GIS Cut Line= 3
       2219162.2     13285993.92      2218792.58     13285439.49
      2218203.51     13285071.32
#Sta/Elev= 30
  4057.2  282.13  4183.3  281.73  4316.3   280.8  4454.6  279.72  4541.7   277.4
  4562.7  277.79  4589.3  276.57  4628.8  275.79  4757.8  272.91  4905.8  272.23
  4953.3  271.44  4976.9  272.06    4983  270.59  5001.2  269.99    5004  269.49
  5007.2  269.99  5009.1  270.36  5012.3  270.97  5019.6  274.65  5025.5  275.52
  5077.4  278.38  5098.6  278.82  5129.2     281  5156.4  281.79  5177.6  283.56
  5207.4  284.49  5308.5  288.09    5345  290.08  5360.4  289.89  5418.2  291.74
#Mann= 10 ,-1 , 0
  4057.2     .05       0  4183.3      .1       0  4316.3     .05       0
  4589.3      .1       0  4628.8     .05       0  4905.8      .1       0
  5001.2     .07       0  5007.2      .1       0  5009.1     .05       0
  5207.4      .1       0
Bank Sta=5001.2,5007.2
XS Rating Curve= 0 ,0
Exp/Cntr=0.3,0.1

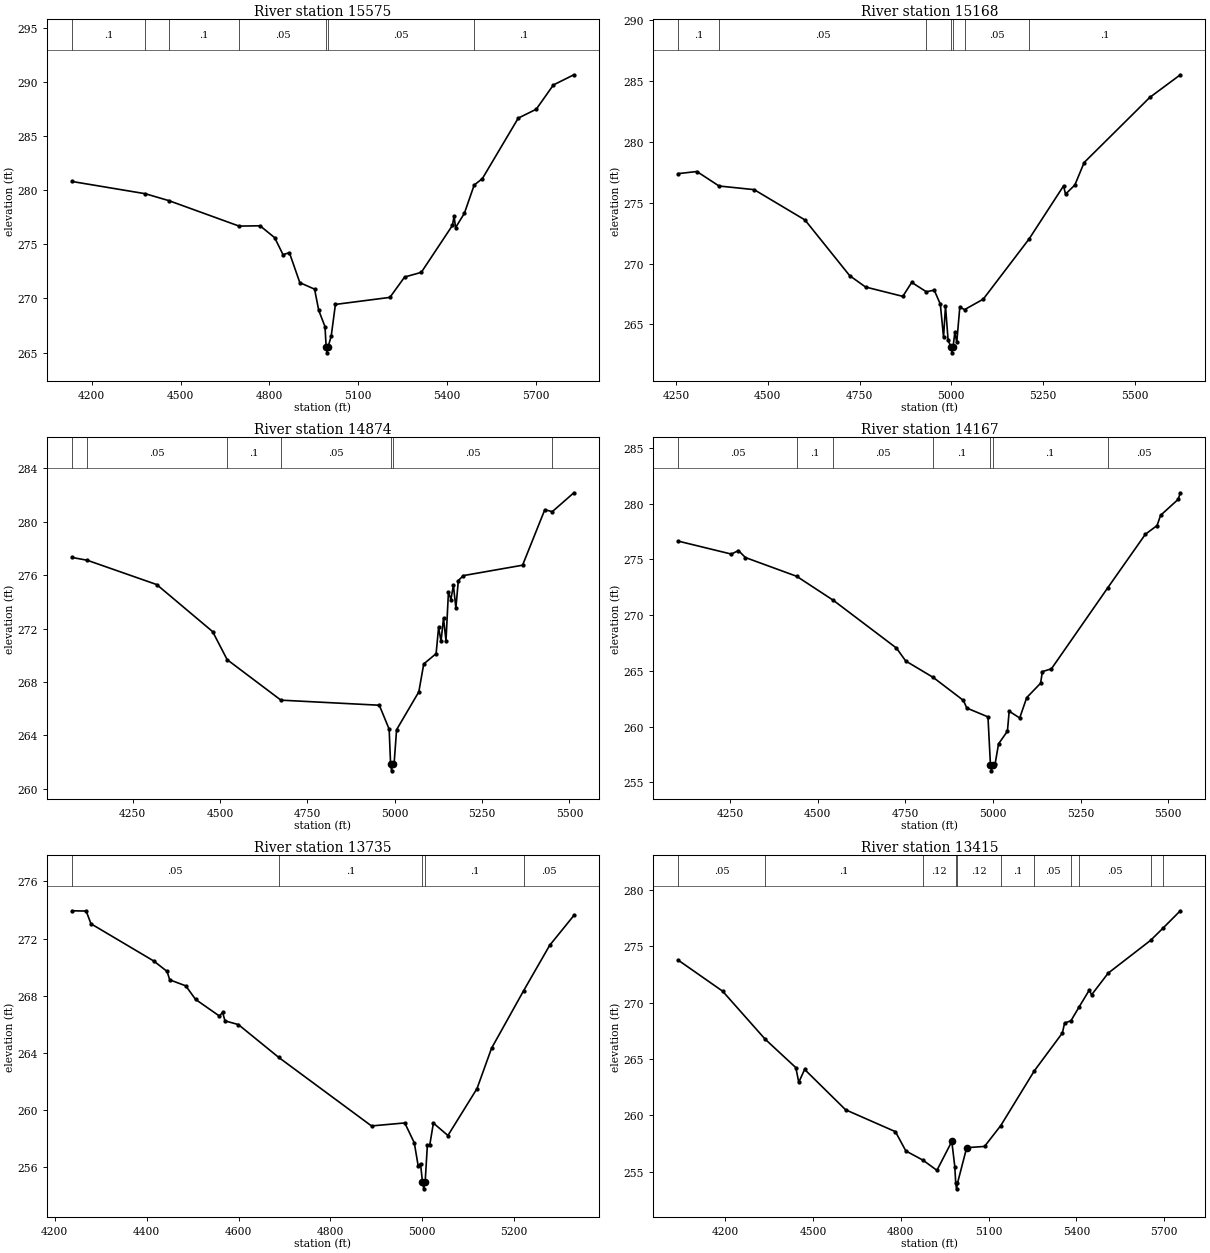
Type RM Length L Ch R = 1 ,15575   ,407,407,407
BEGIN DESCRIPTION:
UNT014 IN SPCR 31.0
END DESCRIPTION:
XS GIS Cut Line= 4
      2219248.47     13285821.44      2219174.54     13285291.63
        2218694.     13284835.74      2218202.13     13284761.96
#Sta/Elev= 30
  4133.2  280.79  4380.8  279.66  4460.5  279.02  4697.6  276.67  4768.3   276.7
  4817.7   275.6    4846  274.03  4867.4  274.22  4902.6  271.45  4952.4  270.85
  4966.5  268.89  4987.6  267.39  4991.6  265.47  4994.3  264.97  4997.6  265.47
  5008.6  266.52  5022.8  269.44  5206.8  270.09  5256.5  271.97  5312.8   272.4
  5417.8  276.73  5423.5  277.58  5428.5  276.53  5458.2  277.85  5491.4  280.46
  5518.9  281.05  5640.2  286.64  5700.9  287.46  5758.8   289.7  5827.9  290.64
#Mann= 7 ,-1 , 0
  4133.2      .1       0  4380.8     .05       0  4460.5      .1       0
  4697.6     .05       0  4991.6     .03       0  4997.6     .05       0
  5491.4      .1       0
Bank Sta=4991.6,4997.6
XS Rating Curve= 0 ,0
Exp/Cntr=0.3,0.1

Type RM Length L Ch R = 1 ,15168   ,294,294,294
BEGIN DESCRIPTION:
Mapping XS 30dce71b
END DESCRIPTION:
XS GIS Cut Line= 4
      2219258.61     13285256.35      2219175.29     13284787.64
       2219060.7     13284709.52      2218352.51     13284454.36
#Sta/Elev= 30
  4256.3   277.4  4306.6  277.57    4367  276.38  4462.7  276.08  4601.1  273.59
    4723  269.01  4766.1  268.08  4867.7  267.31  4891.9  268.46  4931.7  267.69
  4953.3  267.82  4969.9  266.67  4978.7  263.95    4984  266.52  4991.1   263.7
  4998.8  263.17  5001.5  262.67  5004.8  263.17  5009.4  264.35  5014.7  263.54
    5023  266.43  5035.9  266.22  5086.8  267.08  5211.8  272.03  5305.7  276.39
    5311  275.71  5336.4  276.46  5361.8  278.31  5540.6  283.66  5623.8  285.52
#Mann= 7 ,-1 , 0
  4256.3      .1       0    4367     .05       0  4931.7      .1       0
  4998.8     .07       0  5004.8      .1       0  5035.9     .05       0
  5211.8      .1       0
Bank Sta=4998.8,5004.8
XS Rating Curve= 0 ,0
Exp/Cntr=0.3,0.1

Type RM Length L Ch R = 1 ,14874   ,707,707,707
BEGIN DESCRIPTION:
UNT014 IN SPCR 30.0
END DESCRIPTION:
XS GIS Cut Line= 3
       2219310.7     13285209.54       2219310.7     13284730.35
      2218633.64     13284053.29
#Sta/Elev= 30
  4075.9  277.32  4119.7  277.11  4318.6  275.29  4478.6  271.77  4520.2  269.67
  4674.1  266.64  4955.7  266.26  4983.9  264.47    4988  261.85  4990.8  261.35
    4994  261.85  4998.1  261.91  5005.2  264.43  5068.8  267.26  5082.9  269.35
  5118.3  270.12  5125.4  272.09  5132.4  271.05  5139.5  272.78  5146.6  271.08
  5153.6  274.73  5160.7  274.17  5167.8  275.24  5174.9  273.53  5181.9  275.59
  5196.1  275.96  5365.8  276.74  5429.4  280.89    5451  280.75  5512.6  282.16
#Mann= 7 ,-1 , 0
  4075.9      .1       0  4119.7     .05       0  4520.2      .1       0
  4674.1     .05       0    4988     .03       0    4994     .05       0
    5451      .1       0
Bank Sta=4988,4994
XS Rating Curve= 0 ,0
Exp/Cntr=0.3,0.1

Type RM Length L Ch R = 1 ,14167   ,432,432,432
BEGIN DESCRIPTION:
UNT014 IN SPCR 29.0
END DESCRIPTION:
XS GIS Cut Line= 3
      2219507.22     13285217.65       2219556.5     13284515.38
      2219482.82     13283790.82
#Sta/Elev= 30
  4102.4  276.64  4253.6  275.48  4273.6   275.8  4293.7  275.17  4439.8  273.49
  4544.7  271.33  4724.7  267.05  4751.1  265.89  4829.5  264.42  4915.5  262.36
  4925.5  261.67  4985.8  260.88  4992.9  256.54  4995.6  256.04  4998.9  256.54
  5005.9  256.61    5016  258.46  5041.3   259.6  5046.3  261.39  5076.3  260.78
  5096.4  262.61    5136   263.9    5141  264.94  5166.8  265.19  5327.2  272.44
    5435  277.26  5468.3  278.04  5478.4  278.96  5528.6  280.39  5534.7  280.98
#Mann= 7 ,-1 , 0
  4102.4     .05       0  4439.8      .1       0  4544.7     .05       0
  4829.5      .1       0  4992.9     .07       0  4998.9      .1       0
  5327.2     .05       0
Bank Sta=4992.9,4998.9
XS Rating Curve= 0 ,0
Exp/Cntr=0.3,0.1

Type RM Length L Ch R = 1 ,13735   ,320,320,320
BEGIN DESCRIPTION:
UNT014 IN SPCR 28.0
END DESCRIPTION:
XS GIS Cut Line= 3
      2219737.73     13284996.82      2219937.72     13284246.85
      2219837.72     13283946.86
#Sta/Elev= 30
  4237.4  273.94  4268.4  273.92  4278.8  273.03  4415.3  270.43  4444.4   269.7
  4450.2  269.11  4485.1  268.69  4506.5  267.74  4558.2  266.58  4565.3  266.83
  4570.5  266.24  4599.6  265.98  4687.6  263.68  4889.4  258.89  4961.8   259.1
  4982.5  257.71  4990.9  256.11  4996.1  256.25  5000.2  254.99    5003  254.49
  5006.2  254.99    5011  257.56  5016.2  257.56  5024.1  259.09  5055.7  258.22
    5119   261.5  5150.6  264.32  5220.3  268.34  5277.1  271.52  5329.8  273.61
#Mann= 5 ,-1 , 0
  4237.4     .05       0  4687.6      .1       0  5000.2     .07       0
  5006.2      .1       0  5220.3     .05       0
Bank Sta=5000.2,5006.2
XS Rating Curve= 0 ,0
Exp/Cntr=0.3,0.1

Type RM Length L Ch R = 1 ,13415   ,518,518,518
BEGIN DESCRIPTION:
UNT014 IN SPCR 27.0
END DESCRIPTION:
XS GIS Cut Line= 4
      2220239.38     13285357.77      2220234.18     13284589.31
      2220147.93     13284096.45      2219852.44     13283764.02
#Sta/Elev= 30
  4040.9  273.76  4191.8  271.02  4337.1  266.76  4441.8  264.24  4451.8  262.94
  4471.8  264.08  4611.8   260.5  4781.8  258.56  4817.4  256.85    4876  256.03
  4923.5  255.13  4974.3  257.69  4984.5  255.47  4987.7  253.99  4990.5  253.49
  4993.7  253.99  5025.1  257.14    5086  257.25  5141.5   259.1  5255.9  263.95
  5351.8  267.31  5359.4  268.19  5381.2   268.4  5408.2  269.59  5443.8  271.12
  5451.4  270.69  5508.2  272.62  5652.7  275.52  5694.2  276.58  5754.5  278.15
#Mann= 11 ,-1 , 0
  4040.9     .05       0  4337.1      .1       0    4876     .12       0
  4987.7     .07       0  4993.7     .12       0  5141.5      .1       0
  5255.9     .05       0  5381.2      .1       0  5408.2     .05       0
  5652.7      .1       0  5694.2     .05       0
Bank Sta=4974.3,5025.1
XS Rating Curve= 0 ,0
Exp/Cntr=0.3,0.1

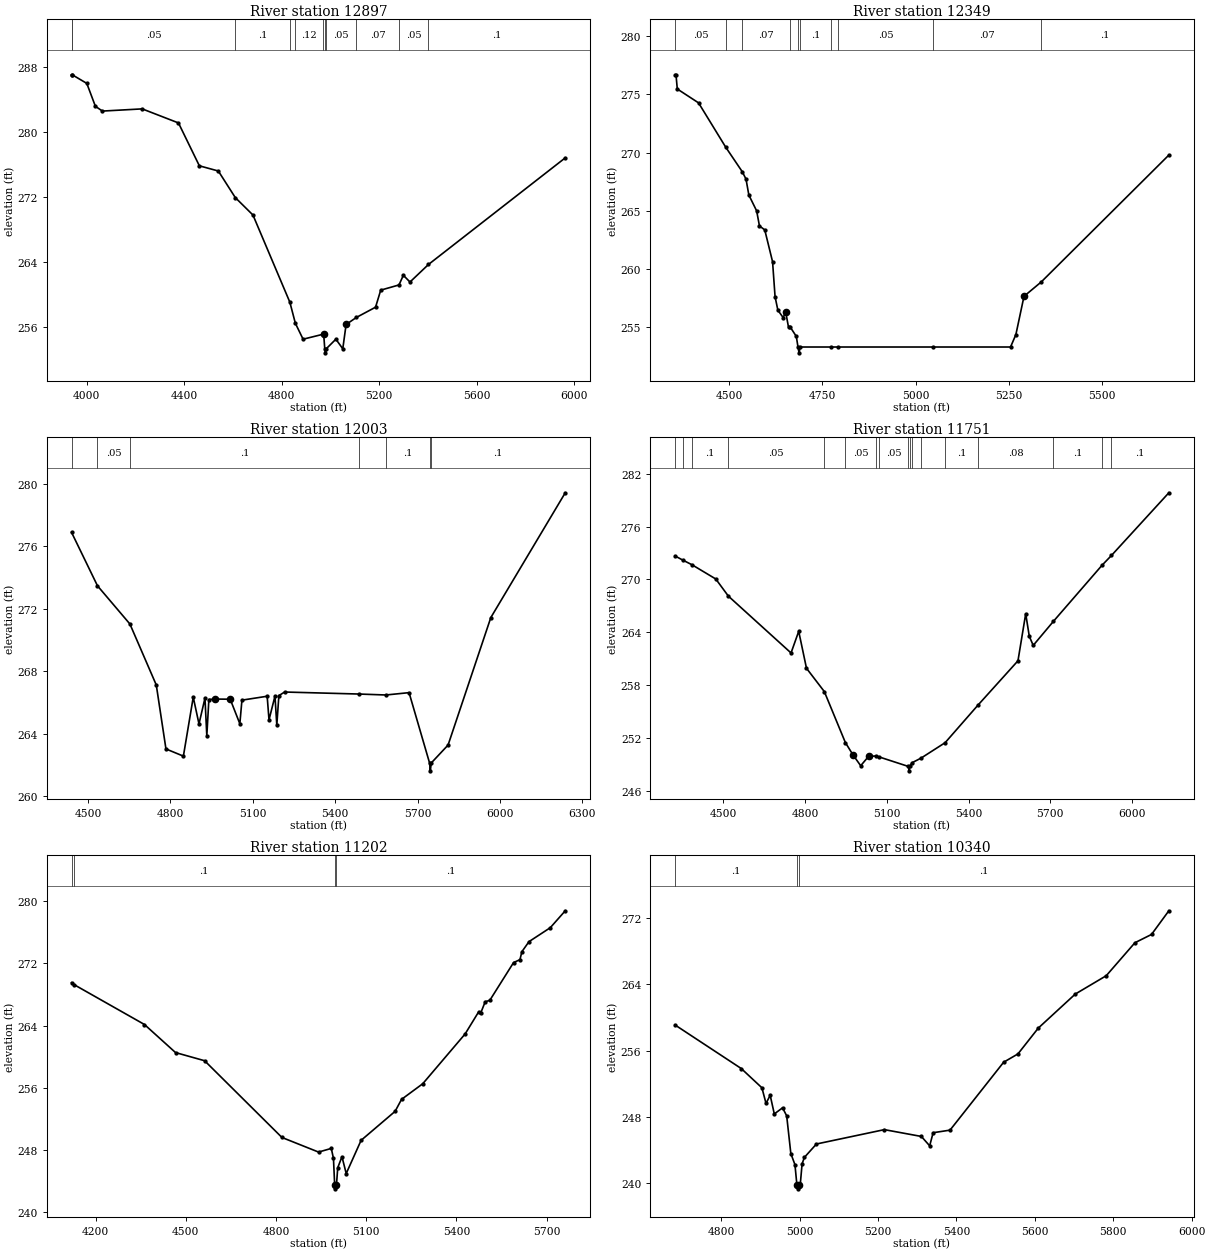
Type RM Length L Ch R = 1 ,12897   ,548,548,548
BEGIN DESCRIPTION:
UNT014 IN SPCR 26.0
END DESCRIPTION:
XS GIS Cut Line= 4
      2221428.32     13285063.64      2221022.75     13284737.17
      2220480.61     13284133.42      2219938.49     13283702.18
#Sta/Elev= 30
  3938.5  287.02  3941.3  287.05  4001.1  285.99  4036.3  283.17  4065.1  282.58
  4228.3  282.85    4377  281.12  4462.7  275.84  4540.5   275.2    4610  271.93
  4682.5  269.78  4833.9  259.04  4856.4  256.45  4888.1  254.49  4970.3   255.1
  4972.5  255.13    4977  253.31  4979.8  252.81    4983  253.31  5022.6  254.49
  5050.9  253.31  5064.5   256.3  5106.7  257.17  5185.3  258.43  5206.5  260.53
  5281.4  261.17  5299.3  262.36  5326.5  261.53  5402.3  263.69  5963.3  276.82
#Mann= 11 ,-1 , 0
  3938.5      .1       0  3941.3     .05       0    4610      .1       0
  4833.9     .05       0  4856.4     .12       0  4970.3     .05       0
    4977    .033       0    4983     .05       0  5106.7     .07       0
  5281.4     .05       0  5402.3      .1       0
Bank Sta=4972.5,5064.5
XS Rating Curve= 0 ,0
Exp/Cntr=0.3,0.1

Type RM Length L Ch R = 1 ,12349   ,346,346,346
BEGIN DESCRIPTION:
Mapping XS 0f71d2f4
END DESCRIPTION:
XS GIS Cut Line= 2
        2221288.     13284444.89      2220298.42     13283568.15
#Sta/Elev= 30
    4356  276.67  4358.3  276.67  4361.8  275.45  4418.7  274.26  4491.4  270.46
  4535.6  268.36  4545.8  267.72  4553.4  266.35  4574.3  264.99  4581.8   263.7
    4596  263.36  4616.9  260.63  4623.6  257.63  4631.1  256.47  4645.4  255.83
    4652  256.33  4659.6  255.01  4663.4  255.06  4680.5  254.22    4685  253.31
  4687.8  252.81    4691  253.31  4773.2  253.31  4791.2  253.31  5046.8  253.31
  5254.2  253.31  5268.5  254.38  5290.2  257.66  5336.3  258.89  5678.1  269.78
#Mann= 10 ,-1 , 0
    4356     .05       0  4491.4      .1       0  4535.6     .07       0
  4663.4      .1       0    4685    .033       0    4691      .1       0
  4773.2     .07       0  4791.2     .05       0  5046.8     .07       0
  5336.3      .1       0
Bank Sta=4652,5290.2
XS Rating Curve= 0 ,0
Exp/Cntr=0.3,0.1

Type RM Length L Ch R = 1 ,12003   ,252,252,252
BEGIN DESCRIPTION:
Mapping XS d823a618
END DESCRIPTION:
XS GIS Cut Line= 3
      2221490.99     13284429.15      2220455.97     13283505.02
      2220147.91     13283233.93
#Sta/Elev= 30
    4440  276.88  4534.5  273.46  4652.5  271.02  4748.6  267.12  4783.8  263.03
  4847.3  262.57  4883.2  266.34  4904.1  264.63  4925.9  266.28  4932.6  263.87
  4940.1  266.19    4961  266.22  5017.8  266.21  5052.9  264.64  5060.5  266.15
  5152.4   266.4  5159.1  264.89  5180.8  266.41  5187.5  264.55    5195  266.44
    5216  266.67  5488.5  266.54  5584.7  266.48  5669.1  266.63  5743.8  262.13
  5746.6  261.63  5749.8  262.13  5811.2  263.28  5966.8  271.43  6237.9  279.41
#Mann= 7 ,-1 , 0
    4440      .1       0  4534.5     .05       0  4652.5      .1       0
  5488.5     .07       0  5584.7      .1       0  5743.8     .07       0
  5749.8      .1       0
Bank Sta=4961,5017.8
XS Rating Curve= 0 ,0
Exp/Cntr=0.3,0.1

Type RM Length L Ch R = 1 ,11751   ,549,549,549
BEGIN DESCRIPTION:
Mapping XS e12b393f
END DESCRIPTION:
XS GIS Cut Line= 3
      2221589.53     13284305.91       2221219.9     13283886.99
      2220234.85     13283111.27
#Sta/Elev= 30
  4322.5  272.66  4350.5   272.2  4384.8  271.66  4471.7  270.05    4518   268.1
    4748  261.64  4776.2   264.1  4804.7   259.9  4870.2  257.25  4947.4  251.46
  4974.9  250.08  5003.7  248.82  5032.6  249.88  5060.1  249.93  5069.5  249.84
  5178.7  248.74  5181.5  248.24  5184.7  248.74  5191.6  249.15    5226   249.7
  5313.7  251.44    5434   255.7  5581.1  260.75  5609.5   266.1  5622.7  263.53
  5637.1   262.5  5711.4  265.24    5890  271.62  5924.2  272.72    6135  279.85
#Mann= 17 ,-1 , 0
  4322.5      .1       0  4350.5     .05       0  4384.8      .1       0
    4518     .05       0  4870.2      .1       0  4947.4     .05       0
  5060.1      .1       0  5069.5     .05       0  5178.7     .04       0
  5184.7     .05       0  5191.6      .1       0    5226     .05       0
  5313.7      .1       0    5434     .08       0  5711.4      .1       0
    5890     .08       0  5924.2      .1       0
Bank Sta=4974.9,5032.6
XS Rating Curve= 0 ,0
Exp/Cntr=0.3,0.1

Type RM Length L Ch R = 1 ,11202   ,862,862,862
BEGIN DESCRIPTION:
Mapping XS 5cb37b2a
END DESCRIPTION:
XS GIS Cut Line= 4
      2221638.84     13284195.05       2221281.5     13283541.99
      2220887.22     13283160.02      2220702.56     13282864.57
#Sta/Elev= 30
    4120  269.52  4127.9  269.28  4362.5  264.14  4465.8  260.53  4562.5  259.48
  4819.6  249.61  4941.4  247.73  4983.8   248.2    4991  246.91    4995   243.5
  4997.7     243    5001   243.5  5005.2  245.72  5019.3  247.13  5033.4  244.97
  5082.9  249.24    5196  252.97  5217.4  254.51  5287.9  256.52  5428.9  262.93
  5474.3   265.8  5480.2  265.57  5495.6  267.07  5510.9  267.25  5589.9  272.11
  5611.1  272.48  5617.6  273.51  5641.2   274.8  5711.9  276.59  5761.8  278.77
#Mann= 4 ,-1 , 0
    4120     .05       0  4127.9      .1       0    4995     .07       0
    5001      .1       0
Bank Sta=4995,5001
XS Rating Curve= 0 ,0
Exp/Cntr=0.3,0.1

Type RM Length L Ch R = 1 ,10340   ,542,542,542
BEGIN DESCRIPTION:
UNT014 IN SPCR 22.0
END DESCRIPTION:
XS GIS Cut Line= 3
      2221787.73     13283746.88      2221687.72     13283446.85
      2221187.75      13282646.9
#Sta/Elev= 30
  4682.2  259.08  4850.9  253.84  4903.6  251.52  4914.1  249.64  4924.7  250.62
  4935.2  248.37  4956.3  249.11  4966.8  248.14  4977.4   243.6  4987.9  242.26
  4992.8  239.85  4995.6  239.35  4998.8  239.85  5001.4  239.85  5006.1  242.36
    5012  243.14  5042.7  244.75    5216  246.48  5310.4  245.66  5331.6  244.53
  5340.4  246.11  5383.5  246.42  5520.3   254.6  5556.8   255.6  5608.7  258.71
  5703.1  262.81  5782.1  265.02  5855.2  268.99  5897.6  269.99  5941.8  272.84
#Mann= 3 ,-1 , 0
  4682.2      .1       0  4992.8     .07       0  4998.8      .1       0
Bank Sta=4992.8,4998.8
XS Rating Curve= 0 ,0
Exp/Cntr=0.3,0.1

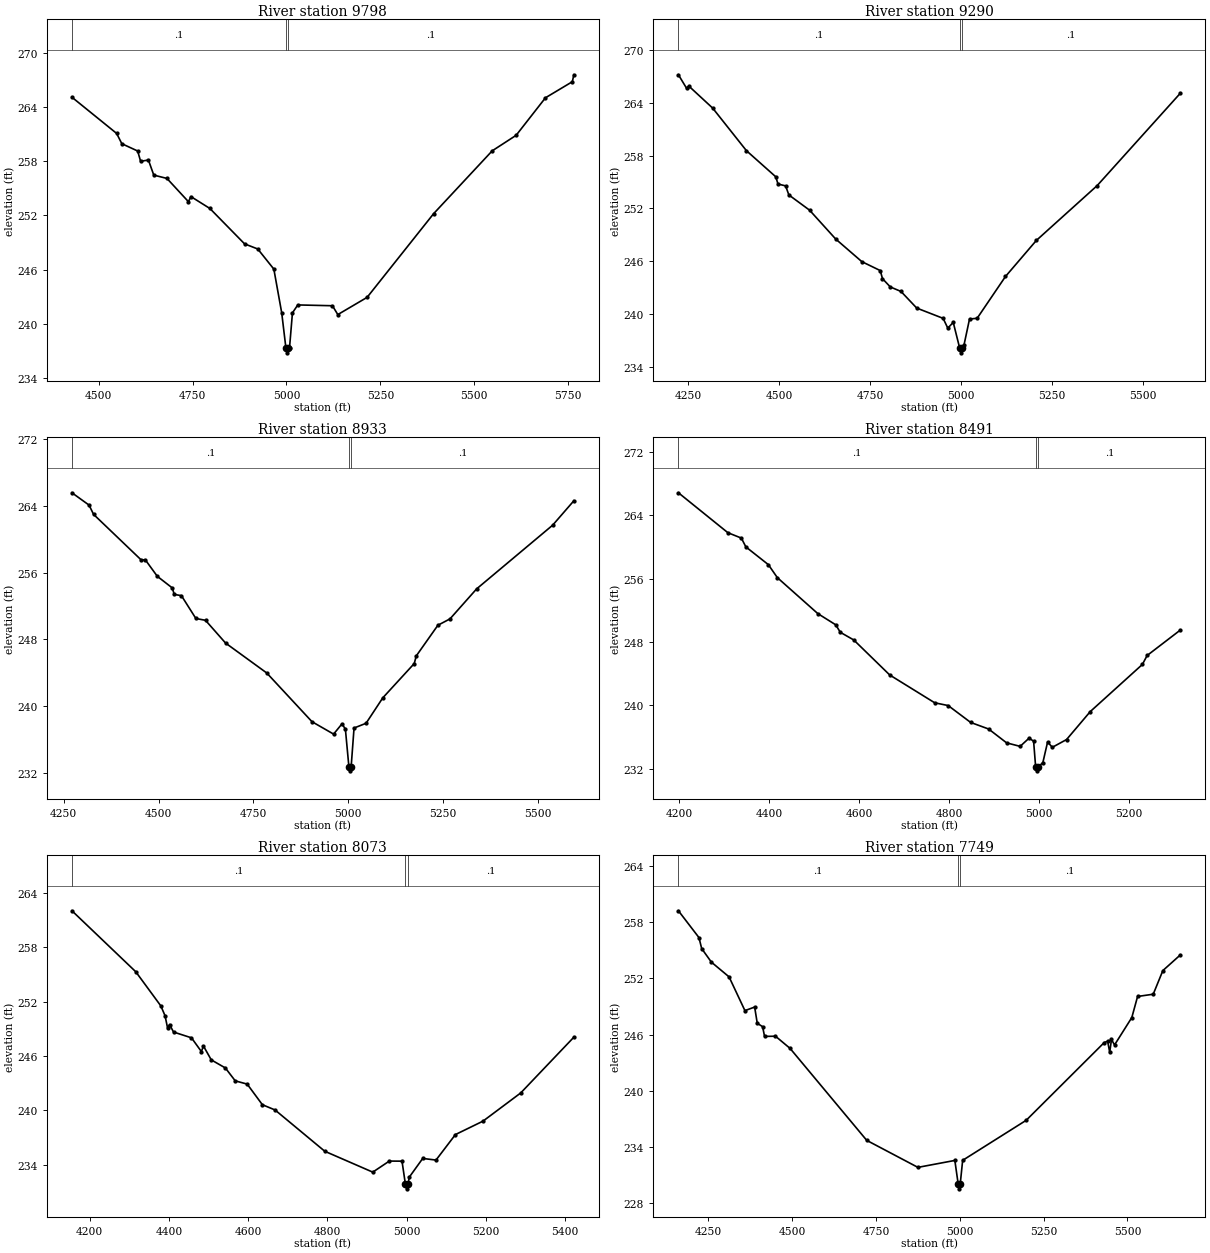
Type RM Length L Ch R = 1 ,9798    ,508,508,508
BEGIN DESCRIPTION:
UNT014 IN SPCR 21.0
END DESCRIPTION:
XS GIS Cut Line= 3
      2222353.44     13283628.21      2221811.33     13282987.52
      2221491.86     13282606.62
#Sta/Elev= 30
  4428.8   265.1  4547.8  261.09  4561.6  259.95  4603.8  259.14  4611.6     258
  4632.4  258.14  4646.7  256.47  4681.8   256.1    4739  253.52  4745.5  254.09
  4796.1  252.77  4888.4  248.85  4923.6  248.28  4966.4  246.05  4987.3  241.21
  4998.6  237.27  5001.3  236.77  5004.6  237.27  5008.1  237.31  5015.9   241.2
  5030.1  242.08  5122.4  241.99  5136.7  241.01  5214.7  242.92  5391.7  252.19
  5547.8  259.16  5611.5  260.88  5689.6  265.04  5761.1  266.82  5765.2  267.59
#Mann= 3 ,-1 , 0
  4428.8      .1       0  4998.6     .07       0  5004.6      .1       0
Bank Sta=4998.6,5004.6
XS Rating Curve= 0 ,0
Exp/Cntr=0.3,0.1

Type RM Length L Ch R = 1 ,9290    ,357,357,357
BEGIN DESCRIPTION:
UNT014 IN SPCR 20.0
END DESCRIPTION:
XS GIS Cut Line= 3
      2222636.89      13283468.1       2222082.4     13282654.84
      2221763.15     13282421.55
#Sta/Elev= 30
  4223.1  267.18  4245.5  265.65  4251.6   265.9  4317.3  263.39  4410.1  258.55
  4490.8  255.58  4496.8  254.76  4517.8  254.55  4526.7  253.52  4583.6  251.79
  4655.4  248.51  4727.2  245.94    4778  244.92  4784.1     244  4805.6  243.06
  4834.9  242.55  4878.2  240.66  4950.8  239.49  4963.6  238.38  4978.6  239.03
  4996.5  236.07  4999.3  235.57  5002.5  236.07  5008.4  236.51  5023.3  239.41
  5044.3   239.5  5122.2  244.25  5207.1  248.35  5374.2  254.58  5602.8  265.08
#Mann= 3 ,-1 , 0
  4223.1      .1       0  4996.5     .07       0  5002.5      .1       0
Bank Sta=4996.5,5002.5
XS Rating Curve= 0 ,0
Exp/Cntr=0.3,0.1

Type RM Length L Ch R = 1 ,8933    ,442,442,442
BEGIN DESCRIPTION:
UNT014 IN SPCR 19.0
END DESCRIPTION:
XS GIS Cut Line= 3
      2222760.08     13283369.49      2222439.72     13282445.38
      2222415.13     13282101.13
#Sta/Elev= 30
  4271.5  265.59  4316.6  264.11  4328.5     263  4454.2  257.52  4464.8  257.55
  4496.6  255.56  4535.9  254.17  4541.2  253.39  4560.1  253.24  4598.2   250.5
  4623.6  250.28  4676.5  247.55    4785  243.96  4904.3  238.11  4961.3  236.62
  4983.4  237.85  4992.4  237.22  5001.6  232.71  5004.3  232.21  5007.6  232.71
  5015.2  237.35  5046.9  237.92  5091.1  240.98  5173.9  245.09  5179.3  246.01
  5236.3  249.69  5268.1  250.45  5338.3  254.05  5538.8   261.7  5594.7  264.63
#Mann= 3 ,-1 , 0
  4271.5      .1       0  5001.6     .07       0  5007.6      .1       0
Bank Sta=5001.6,5007.6
XS Rating Curve= 0 ,0
Exp/Cntr=0.3,0.1

Type RM Length L Ch R = 1 ,8491    ,418,418,418
BEGIN DESCRIPTION:
UNT014 IN SPCR 18.0
END DESCRIPTION:
XS GIS Cut Line= 3
      2222937.72     13283346.88      2222937.72     13282546.85
      2222837.71     13282246.81
#Sta/Elev= 30
  4198.2  266.85  4308.2  261.81  4338.2  261.13  4348.2  260.02  4398.2  257.78
  4418.2  256.14  4508.2   251.6  4548.2  250.18  4558.2  249.24  4588.2  248.27
  4668.2  243.85  4768.2  240.34  4798.2  239.99  4848.2  237.86  4888.2  237.03
  4928.2  235.28  4958.2  234.84  4978.2  235.88  4988.2  235.49  4992.7  232.25
  4995.5  231.75  4998.7  232.25  5008.8   232.8  5019.3  235.39  5029.8  234.72
  5061.5   235.7  5114.2  239.23  5230.1  245.18  5240.7  246.31  5314.5  249.52
#Mann= 3 ,-1 , 0
  4198.2      .1       0  4992.7     .07       0  4998.7      .1       0
Bank Sta=4992.7,4998.7
XS Rating Curve= 0 ,0
Exp/Cntr=0.3,0.1

Type RM Length L Ch R = 1 ,8073    ,324,324,324
BEGIN DESCRIPTION:
UNT014 IN SPCR 17.0
END DESCRIPTION:
XS GIS Cut Line= 3
      2223037.72     13283246.85      2223337.72     13282446.85
      2223237.72     13282046.87
#Sta/Elev= 30
  4155.3     262  4316.4  255.28  4379.6  251.52  4390.3  250.43  4396.5  249.11
  4401.8  249.46  4411.6  248.64    4457     248  4481.9  246.49  4487.3  247.09
  4506.9  245.57  4542.5  244.68  4567.4  243.26  4597.6   242.9  4635.9  240.63
  4667.9  240.05  4793.4   235.5  4914.5   233.2  4956.3  234.42  4988.3  234.41
  4996.9  231.86  4999.7  231.36  5002.9  231.86    5007  232.67  5040.6  234.71
  5074.1  234.53  5123.1  237.34  5192.7  238.82    5288  241.93    5422  248.07
#Mann= 3 ,-1 , 0
  4155.3      .1       0  4996.9     .07       0  5002.9      .1       0
Bank Sta=4996.9,5002.9
XS Rating Curve= 0 ,0
Exp/Cntr=0.3,0.1

Type RM Length L Ch R = 1 ,7749    ,543,543,543
BEGIN DESCRIPTION:
UNT014 IN SPCR 16.0
END DESCRIPTION:
XS GIS Cut Line= 3
      2223314.53     13283283.27      2223597.93     13282617.88
      2223782.75      13281866.3
#Sta/Elev= 30
  4160.7   259.2    4222  256.34  4230.1  255.17  4259.1  253.72  4311.8  252.15
  4359.1  248.55  4388.1  248.93  4395.9   247.2  4411.8  246.84  4417.7   245.8
  4450.3  245.82  4493.8  244.52  4722.5  234.71  4875.1  231.83  4985.3  232.57
  4995.3  230.04    4998  229.54  5001.3  230.04  5008.6  232.58  5198.1  236.85
  5430.8  245.14  5441.1  245.29  5447.3   244.1  5452.5  245.47  5461.7  244.89
  5513.2  247.81  5530.4  250.06  5577.1   250.3  5605.8  252.82  5657.9  254.49
#Mann= 3 ,-1 , 0
  4160.7      .1       0  4995.3     .07       0  5001.3      .1       0
Bank Sta=4995.3,5001.3
XS Rating Curve= 0 ,0
Exp/Cntr=0.3,0.1