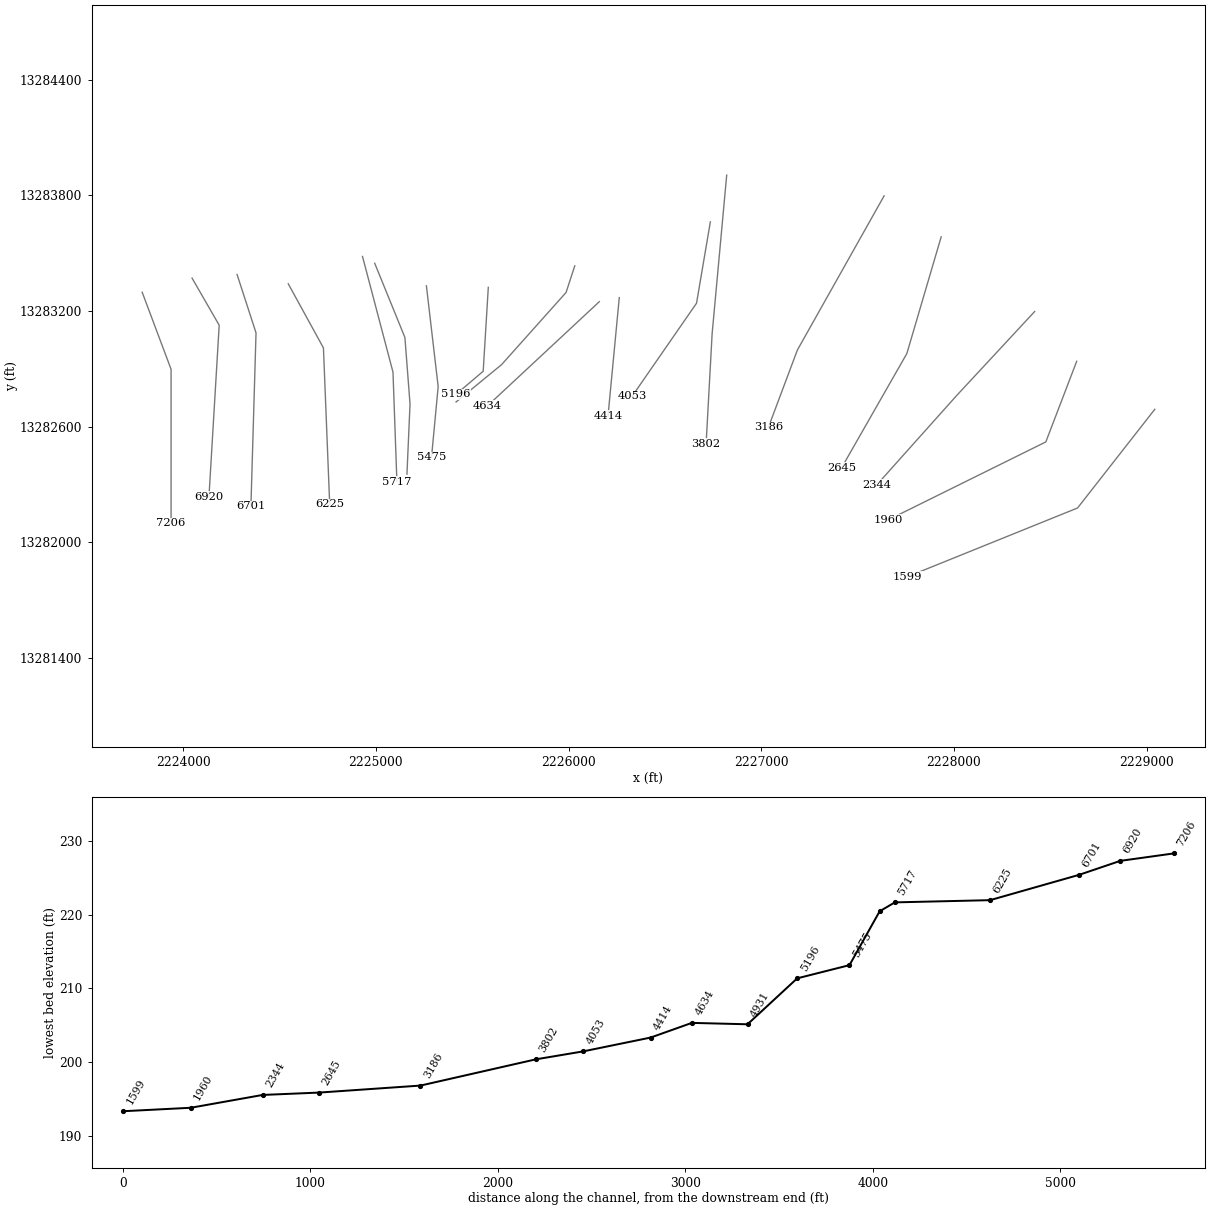
HEC-RAS study UNT014 IN SPCR.prj: UNT014 IN SPCR Base Level Engineering

--- UNT014 IN SPCR.g01 (geometry) --- (continued)

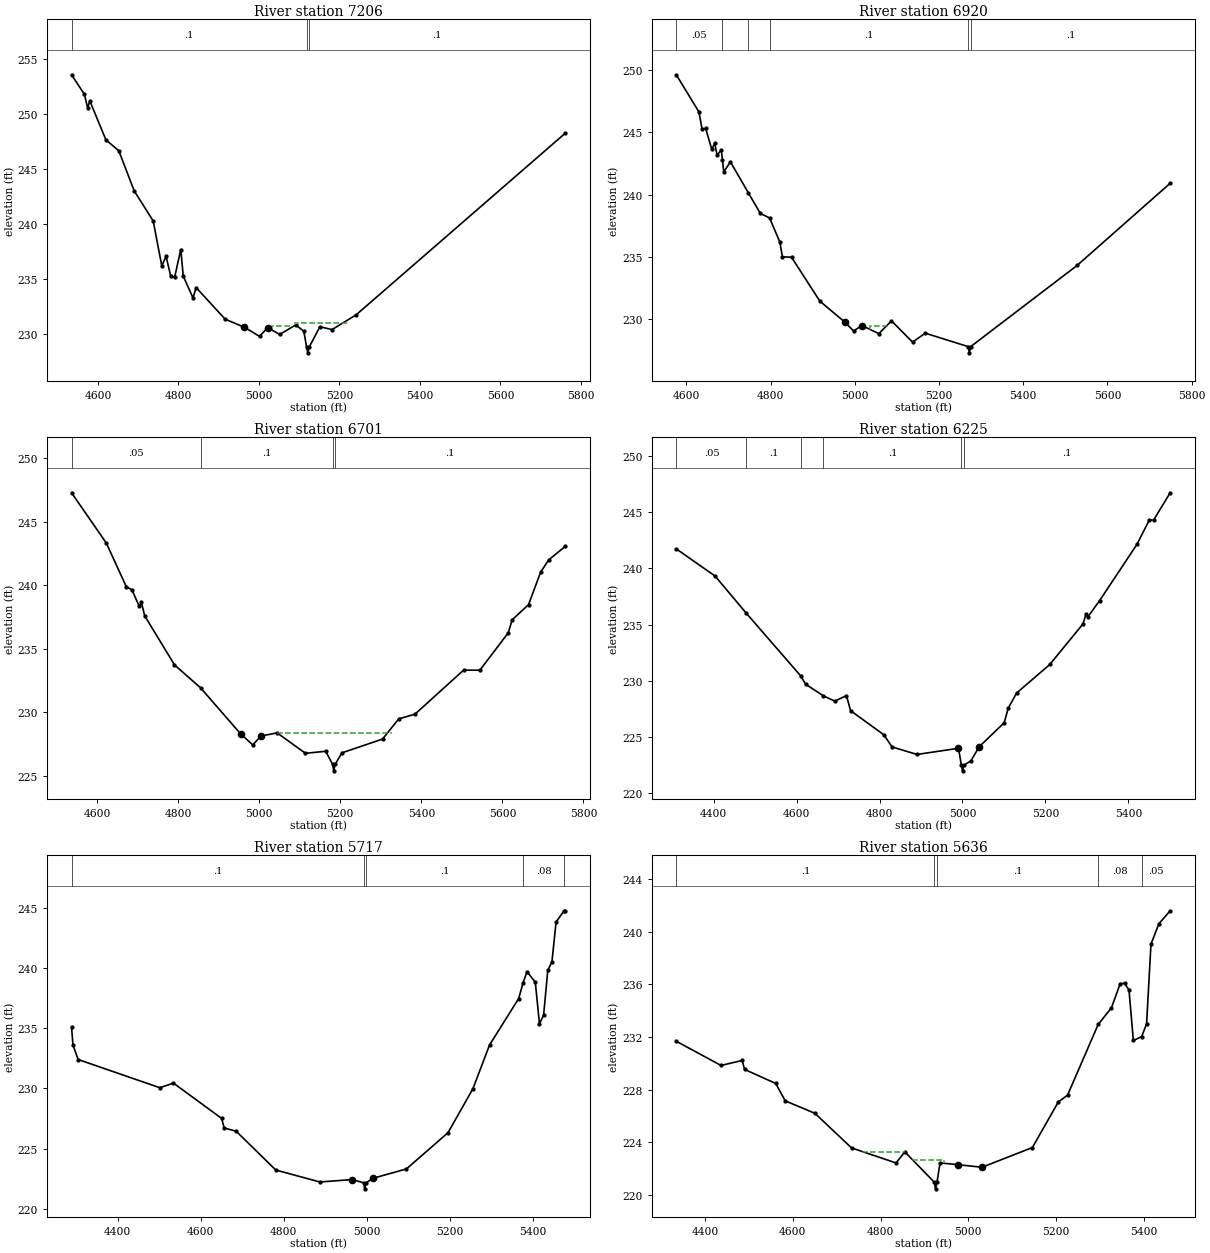
Type RM Length L Ch R = 1 ,7206    ,286,286,286
BEGIN DESCRIPTION:
UNT014 IN SPCR 15.0
END DESCRIPTION:
XS GIS Cut Line= 3
      2223787.73     13283296.82      2223937.72     13282896.85
      2223937.72     13282096.82
#Sta/Elev= 30
  4534.3  253.54  4566.3  251.76  4574.3  250.54  4579.7  251.17  4619.7  247.63
  4651.7  246.64    4690     243  4737.2  240.27  4758.5   236.2  4769.2  237.06
  4780.8  235.25  4790.6  235.18  4805.7  237.68  4811.9  235.26    4836  233.29
    4844  234.22  4916.1  231.35    4964  230.62  5001.5  229.79  5021.5  230.59
  5051.5  229.97  5091.5  230.84  5111.5  230.25  5118.5   228.8  5121.2   228.3
  5124.5   228.8  5151.5  230.67  5181.5  230.41  5241.5  231.75  5761.5  248.25
#Mann= 3 ,-1 , 0
  4534.3      .1       0  5118.5     .07       0  5124.5      .1       0
#XS Ineff= 2 ,-1
 5032.39  5082.5  230.74 5090.45  5221.7  230.97
Permanent Ineff=
       F       F
Bank Sta=4964,5021.5
XS Rating Curve= 0 ,0
Exp/Cntr=0.3,0.1

Type RM Length L Ch R = 1 ,6920    ,219,219,219
BEGIN DESCRIPTION:
Mapping XS c93744fc
END DESCRIPTION:
XS GIS Cut Line= 3
      2224046.68     13283369.86      2224187.39     13283125.61
       2224134.3     13282236.27
#Sta/Elev= 30
  4576.2  249.62    4630  246.63  4637.4  245.25  4645.8  245.32  4660.4  243.64
  4667.3  244.12  4673.1  243.15  4683.1  243.59  4685.8  242.77  4688.9  241.82
  4704.7  242.63  4747.6  240.12  4775.9  238.48  4797.8  238.12    4822  236.19
  4828.2     235  4849.8  234.97  4916.9  231.45    4977  229.74  4997.1  229.05
  5017.1  229.48  5057.2  228.83  5087.2  229.86  5137.3  228.15  5167.4  228.87
  5269.3  227.79  5272.1  227.29  5275.3  227.79    5528  234.31    5749  240.91
#Mann= 6 ,-1 , 0
  4576.2     .05       0  4685.8      .1       0  4747.6     .05       0
  4797.8      .1       0  5269.3     .07       0  5275.3      .1       0
#XS Ineff= 2 ,-1
 5037.16 5078.52  229.41 5087.27 5374.43  229.85
Permanent Ineff=
       F       F
Bank Sta=4977,5017.1
XS Rating Curve= 0 ,0
Exp/Cntr=0.3,0.1

Type RM Length L Ch R = 1 ,6701    ,476,476,476
BEGIN DESCRIPTION:
UNT014 IN SPCR 14.0
END DESCRIPTION:
XS GIS Cut Line= 3
      2224280.32     13283388.42      2224378.54     13283085.78
      2224351.99     13282185.75
#Sta/Elev= 30
  4536.9  247.29  4622.7  243.33  4672.1  239.89  4685.7  239.66  4704.1  238.34
  4709.3  238.66  4717.3  237.61  4790.9  233.74  4855.1  231.94    4954  228.31
  4984.1  227.44  5004.1  228.14  5044.1  228.39  5114.1  226.78  5164.1  226.94
  5181.1   225.9  5183.9   225.4  5187.1   225.9  5204.2  226.82  5304.2   227.9
  5344.2  229.49  5384.2  229.86  5504.3  233.33  5544.3  233.32  5614.3  236.26
  5624.3   237.3  5664.4  238.48  5694.4  241.05  5714.4  242.01  5755.5  243.08
#Mann= 4 ,-1 , 0
  4536.9     .05       0  4855.1      .1       0  5181.1     .07       0
  5187.1      .1       0
#XS Ineff= 1 ,-1
  5043.7 5327.62  228.39
Permanent Ineff=
       F
Bank Sta=4954,5004.1
XS Rating Curve= 0 ,0
Exp/Cntr=0.3,0.1

Type RM Length L Ch R = 1 ,6225    ,508,508,508
BEGIN DESCRIPTION:
Mapping XS 87d8c48a
END DESCRIPTION:
XS GIS Cut Line= 3
      2224545.84     13283340.32      2224728.32      13283007.8
      2224760.76     13282196.75
#Sta/Elev= 30
  4309.9  241.74  4403.4  239.32  4479.1  235.99  4609.7  230.43  4621.8  229.68
  4664.3  228.65  4692.2  228.17  4720.2  228.67  4730.2  227.32  4810.2  225.18
  4830.3  224.09  4890.3  223.42  4990.4  223.97  4997.4  222.46  5000.1  221.96
  5003.4  222.46  5020.4  222.85  5040.4  224.11  5100.5  226.24  5110.5  227.55
  5130.5  228.89  5210.6  231.44  5290.6  235.05  5297.7  235.91  5302.7   235.7
  5330.7  237.13  5420.7  242.14  5450.8  244.33  5460.8   244.3  5500.9  246.74
#Mann= 6 ,-1 , 0
  4309.9     .05       0  4479.1      .1       0  4609.7     .05       0
  4664.3      .1       0  4997.4     .07       0  5003.4      .1       0
Bank Sta=4990.4,5040.4
XS Rating Curve= 0 ,0
Exp/Cntr=0.3,0.1

Type RM Length L Ch R = 1 ,5717    ,81,81,81
BEGIN DESCRIPTION:
UNT014 IN SPCR 13.0
END DESCRIPTION:
XS GIS Cut Line= 3
      2224931.07     13283482.25      2225089.22     13282882.09
       2225109.5      13282314.4
#Sta/Elev= 30
  4289.2  235.09  4292.6  233.59  4305.1  232.39  4501.6  230.05  4534.5  230.43
  4650.2  227.51  4656.7  226.71  4685.4  226.44  4780.8  223.22  4886.9  222.23
  4965.1  222.43  4992.1  222.16  4994.9  221.66  4998.1  222.16  5015.2  222.54
  5095.2  223.31  5195.3  226.32  5255.3  229.97  5295.3   233.6  5365.4  237.45
  5375.9  238.75  5385.4  239.68  5405.4   238.8  5415.4  235.35  5425.4  236.08
  5435.4  239.78  5445.4   240.5  5455.4   243.8  5474.6  244.73  5477.9  244.73
#Mann= 5 ,-1 , 0
  4289.2      .1       0  4992.1     .07       0  4998.1      .1       0
  5375.9     .08       0  5474.6     .05       0
Bank Sta=4965.1,5015.2
XS Rating Curve= 0 ,0
Exp/Cntr=0.3,0.1

Type RM Length L Ch R = 1 ,5636    ,161,161,161
BEGIN DESCRIPTION:
Mapping XS 8c381fd7
END DESCRIPTION:
XS GIS Cut Line= 4
      2224994.47     13283446.86      2225151.11     13283061.89
      2225177.66     13282716.75      2225161.73     13282353.08
#Sta/Elev= 30
  4334.4  231.67  4436.4  229.83  4484.6  230.21    4490  229.53  4561.1  228.46
  4582.7  227.14  4650.5  226.19  4733.9  223.56  4835.3  222.42  4855.4  223.26
  4922.6  220.95  4925.3  220.45  4928.6  220.95  4935.6  222.42  4975.7  222.29
  5031.3  222.09  5146.1  223.59  5205.1  227.05  5226.2  227.57  5296.1  232.95
  5326.3  234.21  5346.3  236.05  5356.3  236.07  5366.3  235.57  5376.3  231.73
  5395.1  232.02  5406.4  232.99  5416.4  239.05  5434.5  240.61  5460.2  241.59
#Mann= 5 ,-1 , 0
  4334.4      .1       0  4922.6     .07       0  4928.6      .1       0
  5296.1     .08       0  5395.1     .05       0
#XS Ineff= 2 ,-1
 4758.24 4855.01  223.27 4871.23 4945.39  222.67
Permanent Ineff=
       F       F
Bank Sta=4975.7,5031.3
XS Rating Curve= 0 ,0
Exp/Cntr=0.3,0.1

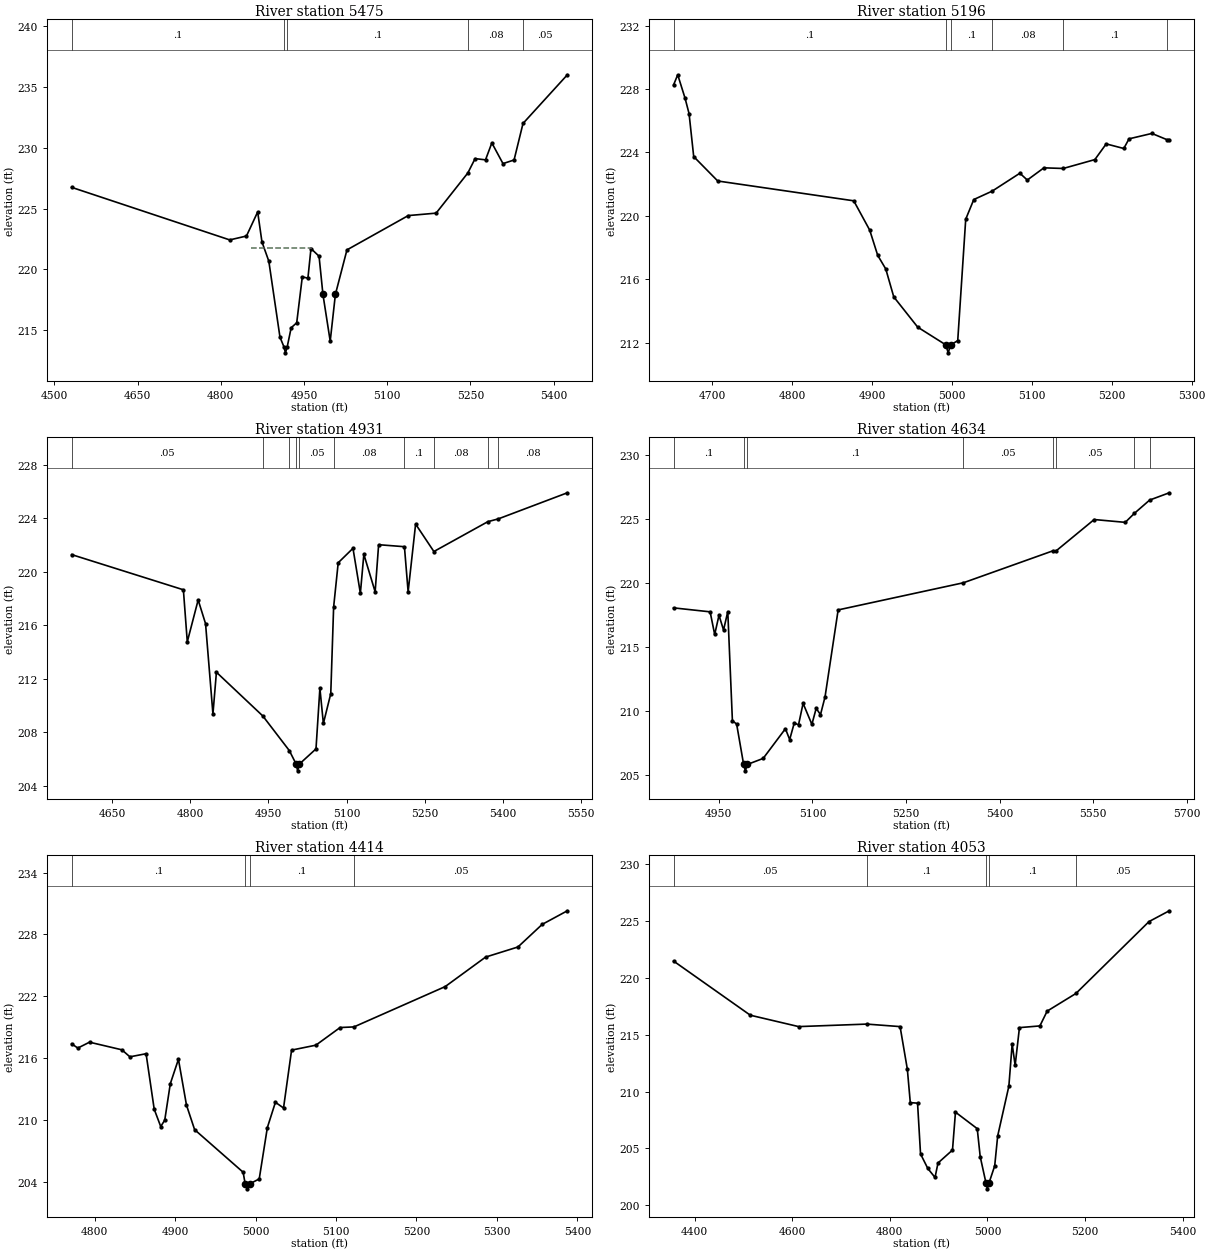
Type RM Length L Ch R = 1 ,5475    ,279,279,279
BEGIN DESCRIPTION:
Mapping XS 7d68987f
END DESCRIPTION:
XS GIS Cut Line= 3
      2225262.61     13283330.05      2225323.68     13282807.02
      2225289.22     13282441.23
#Sta/Elev= 30
    4531  226.75  4816.1  222.43  4846.3  222.75  4866.5  224.73  4874.2  222.27
  4886.6  220.68  4906.7  214.44  4913.8  213.65  4916.6  213.15  4919.8  213.65
  4926.9  215.21  4936.9  215.62    4947   219.4  4957.1  219.28  4962.6  221.72
  4977.2  221.09  4984.2  217.95  4997.3  214.11 5006.65  217.95  5027.5  221.61
  5138.1  224.43  5188.3  224.63  5245.5  227.93  5258.6  229.11  5277.4  229.01
  5288.8   230.4  5308.9   228.7  5328.9     229    5345     232    5425     236
#Mann= 5 ,-1 , 0
    4531      .1       0  4913.8     .07       0  4919.8      .1       0
  5245.5     .08       0    5345     .05       0
#XS Ineff= 1 ,-1
 4855.03 4962.61  221.74
Permanent Ineff=
       F
Bank Sta=4984.2,5006.65
XS Rating Curve= 0 ,0
Exp/Cntr=0.3,0.1

Type RM Length L Ch R = 1 ,5196    ,265,265,265
BEGIN DESCRIPTION:
UNT014 IN SPCR 12.0
END DESCRIPTION:
XS GIS Cut Line= 3
      2225583.85     13283322.02      2225557.31     13282886.67
      2225416.64     13282767.23
#Sta/Elev= 30
  4651.3  228.26  4656.5   228.9  4665.7  227.42  4670.7  226.45  4676.5  223.74
  4706.6   222.2  4876.9  220.95  4896.9   219.1  4906.9  217.51    4917  216.65
    4927  214.89    4957  212.98  4992.3  211.86  4995.1  211.36  4998.3  211.86
  5007.1  212.13  5017.1  219.79  5027.2  221.03  5050.2  221.56  5084.9  222.69
  5094.2  222.26    5115  223.03  5139.2  222.99  5178.8  223.55    5193  224.54
    5215  224.25  5221.6  224.86  5250.2   225.2  5268.9  224.81    5272  224.81
#Mann= 6 ,-1 , 0
  4651.3      .1       0  4992.3     .07       0  4998.3      .1       0
  5050.2     .08       0  5139.2      .1       0  5268.9     .08       0
Bank Sta=4992.3,4998.3
XS Rating Curve= 0 ,0
Exp/Cntr=0.3,0.1

Type RM Length L Ch R = 1 ,4931    ,297,297,297
BEGIN DESCRIPTION:
Mapping XS e6b9f41c
END DESCRIPTION:
XS GIS Cut Line= 4
      2226032.53     13283433.58       2225987.4     13283295.52
      2225652.88     13282921.18      2225416.58     13282727.36
#Sta/Elev= 30
  4571.6  221.29  4786.4  218.66  4793.9  214.77  4814.8   217.9    4829  216.13
  4843.2  209.38  4849.9   212.5  4939.1  209.23  4990.1  206.64  5003.2  205.63
    5006  205.13  5009.2  205.63  5041.3  206.77  5048.8   211.3  5055.5  208.67
  5069.7   210.9  5075.2  217.37    5084  220.68  5112.4  221.76  5126.6   218.4
  5133.3  221.31    5155  218.51  5161.7  222.03  5211.3  221.88  5218.4  218.51
  5232.8  223.57  5267.9  221.52  5371.6  223.75  5391.8  223.96  5524.5  225.91
#Mann= 10 ,-1 , 0
  4571.6     .05       0  4939.1     .08       0  4990.1     .05       0
  5003.2     .04       0  5009.2     .05       0  5075.2     .08       0
  5211.3      .1       0  5267.9     .08       0  5371.6      .1       0
  5391.8     .08       0
Bank Sta=5003.2,5009.2
XS Rating Curve= 0 ,0
Exp/Cntr=0.3,0.1

Type RM Length L Ch R = 1 ,4634    ,220,220,220
BEGIN DESCRIPTION:
UNT014 IN SPCR 11.0
END DESCRIPTION:
XS GIS Cut Line= 2
      2226159.96     13283247.72      2225578.53     13282706.12
#Sta/Elev= 30
  4877.5  218.05  4936.1  217.74  4943.4  215.97  4950.3  217.47  4957.6  216.32
  4964.4  217.76  4971.8  209.24  4978.6  208.97  4989.8  205.82  4992.5  205.32
  4995.8  205.82  5021.1  206.29  5056.8  208.61  5063.6  207.76  5070.9  209.05
  5077.8  208.92  5085.1  210.59  5099.2  208.95  5106.1   210.2    5113  209.71
  5120.3   211.1  5141.3  217.89    5342  220.01  5485.8  222.51  5490.9  222.51
  5551.7  224.95  5601.5  224.73  5616.3  225.44  5640.6  226.47  5672.1  227.04
#Mann= 8 ,-1 , 0
  4877.5      .1       0  4989.8     .07       0  4995.8      .1       0
    5342     .05       0  5485.8      .1       0  5490.9     .05       0
  5616.3      .1       0  5640.6     .05       0
Bank Sta=4989.8,4995.8
XS Rating Curve= 0 ,0
Exp/Cntr=0.3,0.1

Type RM Length L Ch R = 1 ,4414    ,361,361,361
BEGIN DESCRIPTION:
UNT014 IN SPCR 10.0
END DESCRIPTION:
XS GIS Cut Line= 2
       2226263.5     13283268.95       2226205.1     13282655.72
#Sta/Elev= 30
  4771.5  217.39  4779.2  216.98  4793.7  217.55  4833.9  216.81  4843.9  216.13
    4864  216.43  4874.1  211.05  4882.2  209.37  4887.2  209.99  4894.1  213.52
  4904.2  215.89  4914.2  211.45  4924.3  209.07  4984.6  204.94  4987.1  203.83
  4989.9  203.33  4993.1  203.83  5004.6  204.29  5014.7  209.27  5024.7  211.72
  5034.8  211.17  5044.8  216.78    5075  217.26  5105.1  218.97  5122.3  219.03
  5235.7  222.94  5285.9   225.8  5326.1  226.78  5356.2  228.97  5387.5  230.29
#Mann= 4 ,-1 , 0
  4771.5      .1       0  4987.1     .07       0  4993.1      .1       0
  5122.3     .05       0
Bank Sta=4987.1,4993.1
XS Rating Curve= 0 ,0
Exp/Cntr=0.3,0.1

Type RM Length L Ch R = 1 ,4053    ,251,251,251
BEGIN DESCRIPTION:
Mapping XS f34e93aa
END DESCRIPTION:
XS GIS Cut Line= 3
      2226736.08     13283661.91      2226664.39     13283239.77
      2226329.86     13282756.55
#Sta/Elev= 30
  4356.9  221.47  4514.2  216.71  4613.2  215.71  4752.9  215.93  4821.1  215.71
    4836  211.96    4842  209.03  4856.9  208.98    4863  204.52  4877.9  203.24
  4892.7  202.45  4898.8  203.72  4928.5  204.86  4934.6  208.19  4979.2  206.74
  4985.3  204.28  4997.2  201.95  4999.9  201.45  5003.2  201.95    5015  203.47
  5021.1   206.1    5044  210.47  5050.8  214.18  5056.9   212.3  5065.7  215.62
  5107.6  215.77  5122.5  217.07  5181.4  218.62  5331.2  224.94  5372.8  225.89
#Mann= 5 ,-1 , 0
  4356.9     .05       0  4752.9      .1       0  4997.2     .07       0
  5003.2      .1       0  5181.4     .05       0
Bank Sta=4997.2,5003.2
XS Rating Curve= 0 ,0
Exp/Cntr=0.3,0.1

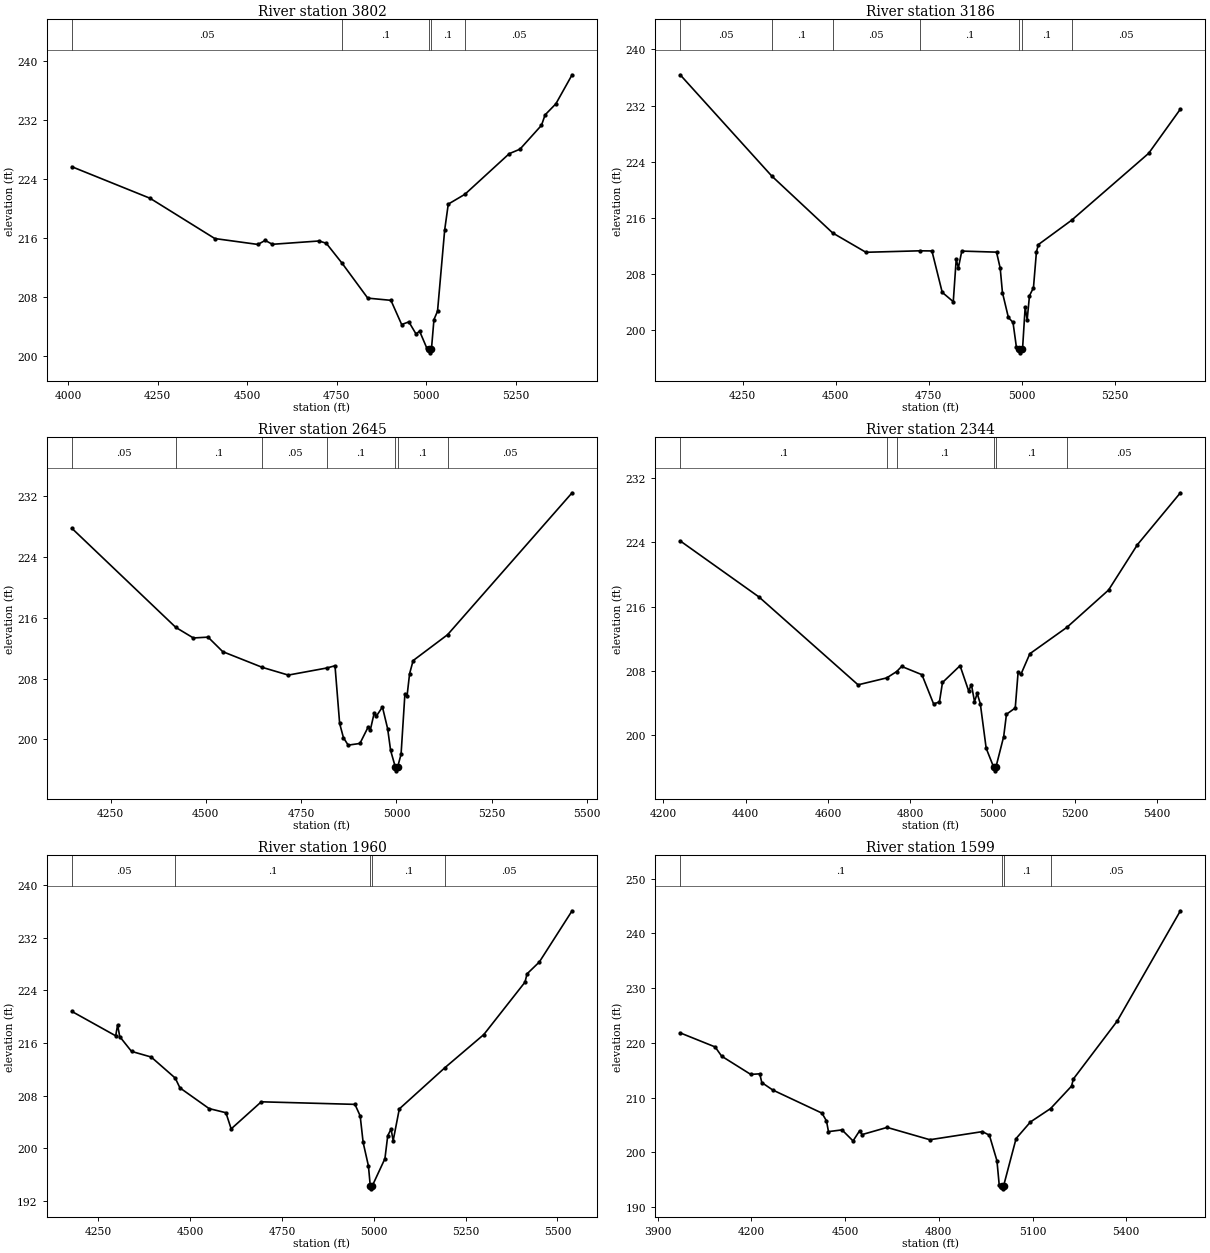
Type RM Length L Ch R = 1 ,3802    ,616,616,616
BEGIN DESCRIPTION:
UNT014 IN SPCR 8.0
END DESCRIPTION:
XS GIS Cut Line= 3
      2226820.93     13283904.48      2226745.26     13283080.97
      2226714.11      13282511.5
#Sta/Elev= 30
  4010.3  225.62  4228.8  221.34  4409.6  215.88  4530.1  215.08  4550.2  215.63
  4570.3   215.1  4700.8  215.55  4720.9  215.24  4765.3  212.52  4836.8   207.8
  4901.5   207.5  4931.5  204.22  4951.6  204.58  4971.6  202.94  4981.6  203.32
  5001.6  201.04  5008.7  200.88  5011.4  200.38  5014.7  200.88  5021.7  204.89
  5031.7  206.03  5051.7  217.06  5061.7  220.55  5108.1  221.88    5232  227.39
    5262     228  5322.1  231.24  5332.1  232.65  5362.2  234.15  5407.6  238.09
#Mann= 5 ,-1 , 0
  4010.3     .05       0  4765.3      .1       0  5008.7     .07       0
  5014.7      .1       0  5108.1     .05       0
Bank Sta=5008.7,5014.7
XS Rating Curve= 0 ,0
Exp/Cntr=0.3,0.1

Type RM Length L Ch R = 1 ,3186    ,541,541,541
BEGIN DESCRIPTION:
UNT014 IN SPCR 7.0
END DESCRIPTION:
XS GIS Cut Line= 3
       2227637.7     13283796.81      2227187.72     13282996.85
      2227037.73     13282596.88
#Sta/Elev= 30
    4082  236.39  4328.1  221.99  4492.1  213.88  4581.4  211.13  4726.4  211.34
  4758.9  211.32  4786.6  205.43  4816.3   204.1  4824.2  210.14    4830   208.9
  4839.2   211.3  4932.6  211.15  4942.5  208.87  4948.5   205.4  4964.5  201.85
  4976.9  201.15  4986.1  197.61    4994  197.32  4996.7  196.82    5000  197.32
  5002.5  197.32  5009.6  203.32    5015  201.53  5021.2  204.95  5031.9  206.08
  5039.9  211.19  5045.2  212.23  5134.4  215.69  5341.6  225.21    5427  231.51
#Mann= 7 ,-1 , 0
    4082     .05       0  4328.1      .1       0  4492.1     .05       0
  4726.4      .1       0    4994     .07       0    5000      .1       0
  5134.4     .05       0
Bank Sta=4994,5000
XS Rating Curve= 0 ,0
Exp/Cntr=0.3,0.1

Type RM Length L Ch R = 1 ,2645    ,301,301,301
BEGIN DESCRIPTION:
UNT014 IN SPCR 6.0
END DESCRIPTION:
XS GIS Cut Line= 3
      2227933.82     13283583.97      2227755.76     13282978.59
      2227417.46     13282386.56
#Sta/Elev= 30
  4148.3  227.76  4421.1  214.73  4467.2  213.34  4505.7  213.45  4544.3  211.54
  4648.4  209.47  4716.3  208.46  4818.3   209.4  4838.9  209.69  4851.1   202.1
  4861.1  200.22  4873.5  199.25  4904.3  199.47  4925.9  201.63  4931.7  201.26
  4941.8  203.48  4947.5  203.06  4963.4  204.27  4977.1   201.4  4984.9  198.55
  4997.2  196.37  4999.9  195.87  5003.2  196.37  5012.3  198.04  5022.4  205.99
  5028.1  205.76  5034.7  208.65    5044  210.37  5134.4  213.77  5461.2  232.43
#Mann= 7 ,-1 , 0
  4148.3     .05       0  4421.1      .1       0  4648.4     .05       0
  4818.3      .1       0  4997.2     .07       0  5003.2      .1       0
  5134.4     .05       0
Bank Sta=4997.2,5003.2
XS Rating Curve= 0 ,0
Exp/Cntr=0.3,0.1

Type RM Length L Ch R = 1 ,2344    ,384,384,384
BEGIN DESCRIPTION:
UNT014 IN SPCR 5.0
END DESCRIPTION:
XS GIS Cut Line= 3
      2228419.04      13283196.7      2228013.95     13282760.46
      2227599.95     13282297.49
#Sta/Elev= 30
  4240.8  224.18  4432.4   217.2  4673.4  206.26    4743  207.12  4767.2  207.91
  4779.4  208.55  4828.7  207.52    4857  203.89  4871.2  204.12  4878.7  206.55
  4921.4  208.64  4942.3   205.5    4949  206.29  4956.5  204.18  4963.2  205.18
  4970.7  203.89  4984.9  198.36  5002.8  196.05  5005.6  195.55  5008.8  196.05
  5027.5  199.82  5034.2  202.59  5055.6  203.38  5062.6  207.86  5069.4  207.57
  5091.1  210.13  5181.3  213.42  5282.5  218.06  5352.7  223.71  5457.2  230.17
#Mann= 6 ,-1 , 0
  4240.8      .1       0    4743     .05       0  4767.2      .1       0
  5002.8     .07       0  5008.8      .1       0  5181.3     .05       0
Bank Sta=5002.8,5008.8
XS Rating Curve= 0 ,0
Exp/Cntr=0.3,0.1

Type RM Length L Ch R = 1 ,1960    ,361,361,361
BEGIN DESCRIPTION:
UNT014 IN SPCR 4.0
END DESCRIPTION:
XS GIS Cut Line= 3
      2228637.17     13282938.53      2228476.92     13282520.08
      2227657.81     13282114.97
#Sta/Elev= 30
  4177.9   220.8  4297.2  217.09  4302.5  218.76  4308.2  216.97  4340.3  214.72
  4393.9  213.86  4459.3  210.66  4472.1  209.17  4551.5  206.02  4597.3  205.39
  4611.6  202.93  4693.6  207.05  4948.6  206.66  4962.8  204.91  4970.9  200.86
  4985.3   197.3  4990.2  194.31    4993  193.81  4996.2  194.31  5030.2   198.4
  5037.9  201.91    5047   202.9  5052.6  201.13  5069.4  205.97  5193.7  212.25
  5299.4  217.28  5411.5  225.25  5417.2  226.52  5450.6  228.32  5539.8  236.11
#Mann= 5 ,-1 , 0
  4177.9     .05       0  4459.3      .1       0  4990.2     .07       0
  4996.2      .1       0  5193.7     .05       0
Bank Sta=4990.2,4996.2
XS Rating Curve= 0 ,0
Exp/Cntr=0.3,0.1

Type RM Length L Ch R = 1 ,1599    ,427,427,427
BEGIN DESCRIPTION:
UNT014 IN SPCR 3.0
END DESCRIPTION:
XS GIS Cut Line= 3
      2229042.29     13282689.27      2228641.62     13282177.31
      2227760.17     13281821.16
#Sta/Elev= 30
  3972.3  221.83  4084.2  219.26  4105.1  217.57  4198.2  214.24  4227.1  214.35
  4233.5  212.75  4268.7  211.39    4426  207.17  4440.5  205.75  4446.9  203.79
  4490.2  204.11  4525.5  202.09  4546.8  203.97  4554.4  203.25  4634.5  204.56
  4771.3  202.31  4939.4  203.79  4961.8  203.14    4986  198.48  4993.3  194.04
  5001.1  193.84  5003.9  193.34  5007.1  193.84  5047.3  202.53  5093.3  205.56
  5157.8  208.01  5224.7   212.1  5230.6  213.41  5370.8  223.98  5573.1  244.13
#Mann= 4 ,-1 , 0
  3972.3      .1       0  5001.1     .07       0  5007.1      .1       0
  5157.8     .05       0
Bank Sta=5001.1,5007.1
XS Rating Curve= 0 ,0
Exp/Cntr=0.3,0.1