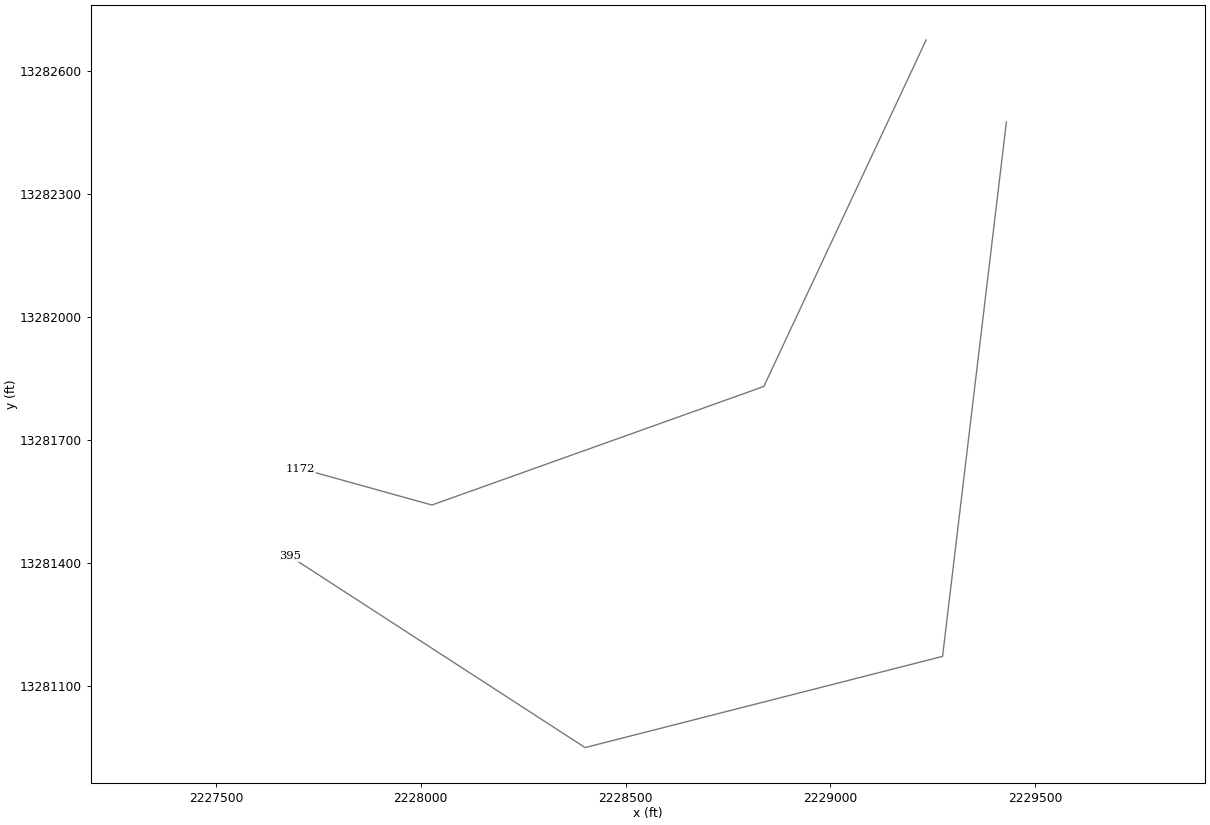
HEC-RAS study UNT014 IN SPCR.prj: UNT014 IN SPCR Base Level Engineering

--- UNT014 IN SPCR.g01 (geometry) --- (continued)

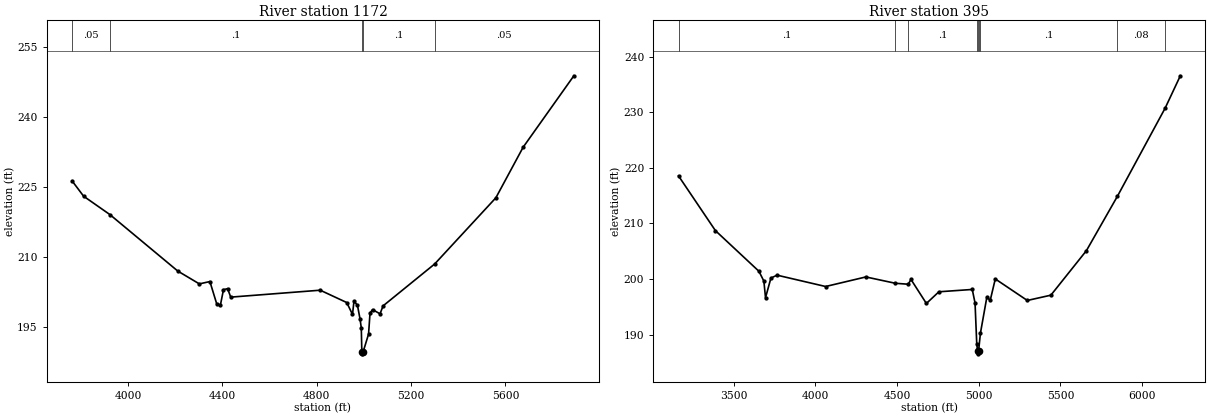
Type RM Length L Ch R = 1 ,1172    ,777,777,777
BEGIN DESCRIPTION:
UNT014 IN SPCR 2.0
END DESCRIPTION:
XS GIS Cut Line= 4
      2229233.68     13282675.87      2228837.49     13281830.08
      2228027.31     13281540.73      2227706.83     13281629.75
#Sta/Elev= 30
  3763.2  226.32  3812.2  223.04  3923.6  219.11  4211.4  207.03  4302.7  204.29
  4347.4  204.79  4376.7  199.96  4391.6  199.67    4405  203.06  4422.4  203.27
  4435.7  201.46    4815  202.94  4927.5   200.3  4951.8  197.76  4958.3  200.65
    4973  199.67  4983.6  196.85  4989.1  194.89  4991.4  189.83  4994.2  189.33
  4997.4  189.83  5019.9  193.55  5026.1  198.04  5036.7  198.79  5068.6  197.89
  5081.5  199.59  5300.2  208.55  5559.6  222.71  5675.1  233.52  5890.1   248.8
#Mann= 5 ,-1 , 0
  3763.2     .05       0  3923.6      .1       0  4991.4     .07       0
  4997.4      .1       0  5300.2     .05       0
Bank Sta=4991.4,4997.4
XS Rating Curve= 0 ,0
Exp/Cntr=0.3,0.1

Type RM Length L Ch R = 1 ,395     ,0,0,0
BEGIN DESCRIPTION:
UNT014 IN SPCR 1.0
END DESCRIPTION:
XS GIS Cut Line= 4
      2229429.56      13282475.6      2229273.75     13281171.25
      2228401.24     13280948.67      2227681.39     13281415.24
#Sta/Elev= 30
  3161.8  218.55  3387.6  208.71    3654   201.4  3684.2  199.63  3694.3  196.65
  3727.4  200.18  3764.8   200.7  4062.2  198.66  4308.6  200.38  4489.3  199.24
  4568.1  199.07  4584.8  199.93  4679.1  195.61  4755.6  197.71    4960  198.13
    4977  195.69  4987.4  188.38  4992.7  187.05  4995.4  186.55  4998.7  187.05
  5009.8  190.24  5049.3  196.75  5069.9  196.17  5100.9  200.02  5296.9  196.15
  5441.2   197.1  5658.8  205.11  5848.2  214.87  6140.9  230.75  6233.7  236.56
#Mann= 9 ,-1 , 0
  3161.8      .1       0  4489.3     .05       0  4568.1      .1       0
  4987.4     .12       0  4992.7     .07       0  4998.7     .12       0
  5009.8      .1       0  5848.2     .08       0  6140.9     .05       0
Bank Sta=4992.7,4998.7
XS Rating Curve= 0 ,0
Exp/Cntr=0.3,0.1

Chan Stop Cuts=-1
Use User Specified Reach Order=0
Composite Channel Slope=5