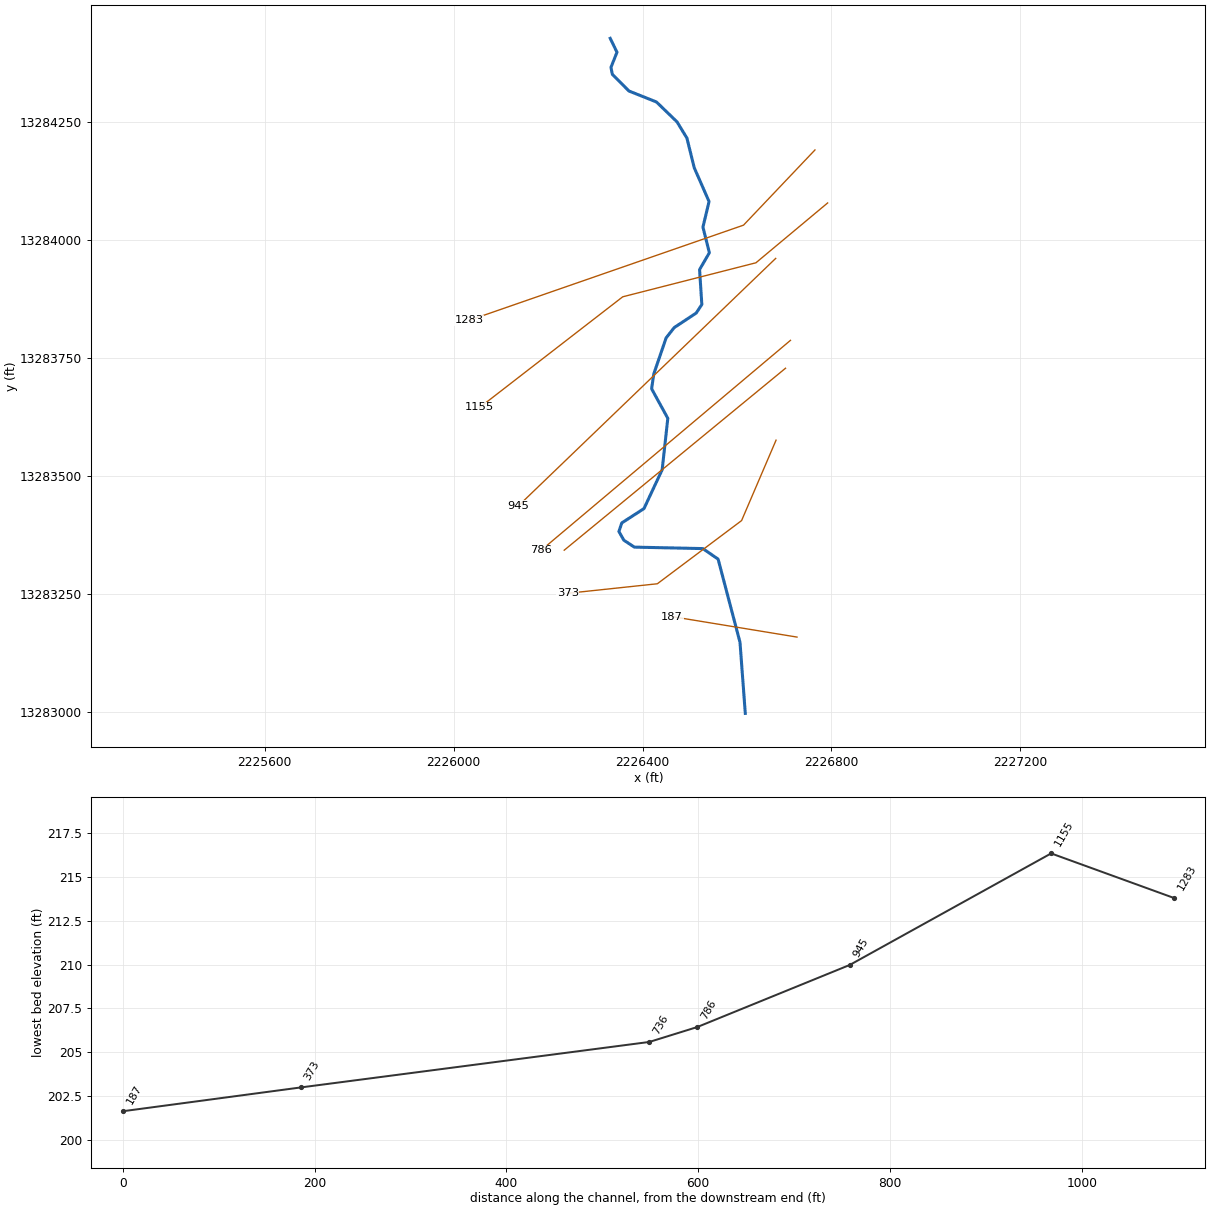
--- UNT015 IN SPCR.prj (project) ---

Proj Title=UNT015 IN SPCR Base Level Engineering
Current Plan=p01
Default Exp/Contr=0.3,0.1
English Units
Geom File=g01
Flow File=f01
Plan File=p01
Y Axis Title=Elevation
X Axis Title(PF)=Main Channel Distance
X Axis Title(XS)=Station
BEGIN DESCRIPTION:
UNT015 IN SPCR
END DESCRIPTION:
DSS Export Rating Curves= 0
DSS Export Rating Curve Sorted= 0
DSS Export Volume Flow Curves= 0
DXF OffsetX= 0
DXF OffsetY= 0
DXF ScaleX= 1
DXF ScaleY= 10

--- UNT015 IN SPCR.p01 (plan) ---

Plan Title=Multiple Run
Short Identifier=Multiple
Geom File=g01
Flow File=f01
Subcritical Flow
K Sum by GR= 0
Std Step Tol= 0.01
Critical Tol= 0.01
Num of Std Step Trials= 20
Max Error Tol= 0.3
Flow Tol Ratio= 0.001
Split Flow NTrial= 30
Split Flow Tol= 0.02
Split Flow Ratio= 0.02
Log Output Level= 0
Friction Slope Method= 1
Unsteady Friction Slope Method= 2
Unsteady Bridges Friction Slope Method= 1
Parabolic Critical Depth
Global Vel Dist=  1 , 1 , 1
Global Log Level= 0
CheckData=True
Encroach Param= -1, 0, 0, 0
BEGIN DESCRIPTION:
Multiple Run
END DESCRIPTION:

--- UNT015 IN SPCR.f01 (steady flow) ---

Flow Title=Multiple
Number of Profiles=7
Profile Names=10-year,25-year,50-year,1pct_min,100-year,1pct_plu,500-year
River Rch & RM= UNT015 IN SPCR,Reach-1,1283
     207     286     352     319     432     584     658
Boundary for River Rch & Prof#=UNT015 IN SPCR,Reach-1,1
Up Type=0
Dn Type=3
Dn Slope=0.005
Boundary for River Rch & Prof#=UNT015 IN SPCR,Reach-1,2
Up Type=0
Dn Type=3
Dn Slope=0.005
Boundary for River Rch & Prof#=UNT015 IN SPCR,Reach-1,3
Up Type=0
Dn Type=3
Dn Slope=0.005
Boundary for River Rch & Prof#=UNT015 IN SPCR,Reach-1,4
Up Type=0
Dn Type=3
Dn Slope=0.005
Boundary for River Rch & Prof#=UNT015 IN SPCR,Reach-1,5
Up Type=0
Dn Type=3
Dn Slope=0.005
Boundary for River Rch & Prof#=UNT015 IN SPCR,Reach-1,6
Up Type=0
Dn Type=3
Dn Slope=0.005
Boundary for River Rch & Prof#=UNT015 IN SPCR,Reach-1,7
Up Type=0
Dn Type=3
Dn Slope=0.005

--- UNT015 IN SPCR.g01 (geometry) ---

Geom Title=Existing Conditions
Program Version=4.10

River Reach=UNT015 IN SPCR  ,Reach-1
Reach XY= 30
      2226331.66      13284426.6      2226345.94     13284397.15
      2226333.18     13284365.08      2226336.12     13284350.33
      2226371.27     13284315.04      2226429.48     13284291.85
      2226473.05     13284249.78      2226494.02     13284215.38
      2226509.56     13284152.56      2226540.96      13284080.9
      2226528.01     13284026.77      2226541.62     13283972.42
      2226520.89     13283936.84      2226525.66     13283862.85
       2226513.8     13283844.79      2226467.22       13283814.
      2226450.03     13283792.12      2226423.99     13283716.08
       2226419.3     13283684.31      2226453.59     13283621.79
      2226441.66     13283512.91      2226403.14     13283430.61
      2226356.16     13283400.24      2226350.04     13283382.08
      2226360.44     13283363.71      2226382.67     13283348.97
      2226527.88     13283345.88      2226560.13     13283323.53
       2226606.5     13283147.35      2226617.72     13282996.86

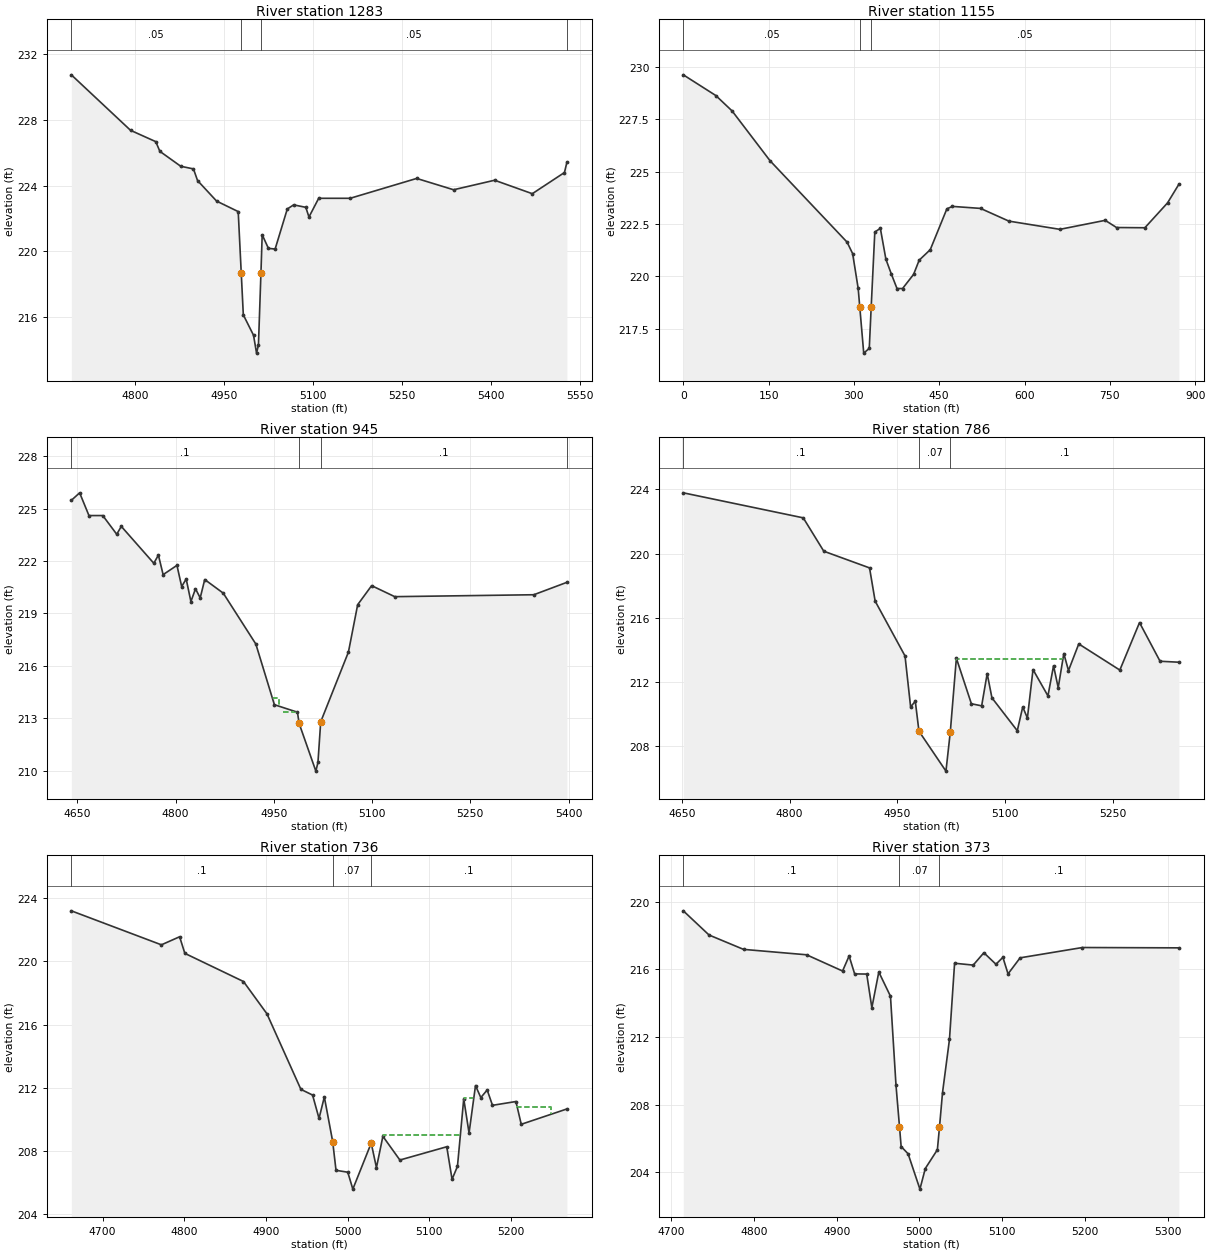
Type RM Length L Ch R = 1 ,1283    ,128,128,128
BEGIN DESCRIPTION:
UNT015 IN SPCR 2.0
END DESCRIPTION:
XS GIS Cut Line= 3
      2226765.27      13284190.2      2226613.95     13284030.92
      2226032.66     13283829.19
#Sta/Elev= 30
  4692.2  230.75    4792  227.37  4834.5  226.68  4841.4  226.09  4876.6  225.18
    4898  225.02  4904.9  224.31    4937  223.06  4973.4  222.42 4978.48   218.7
    4982  216.13  4999.2  214.89  5004.3   213.8  5007.5   214.3 5011.71  218.68
  5013.8  221.01  5024.3  220.18  5035.6  220.14  5056.1  222.58  5066.8  222.83
  5087.3  222.68  5092.6  222.09    5109  223.23    5162  223.23  5274.1  224.44
  5336.3  223.75  5405.4  224.33  5468.9  223.51  5523.1   224.8  5527.2  225.42
#Mann= 4 ,-1 , 0
  4692.2     .05       0 4978.48     .03       0 5011.71     .05       0
  5527.2     .05       0
Bank Sta=4978.48,5011.71
XS Rating Curve= 0 ,0
Exp/Cntr=0.3,0.1

Type RM Length L Ch R = 1 ,1155    ,210,210,210
BEGIN DESCRIPTION:
Mapping XS a0d9e7b3
END DESCRIPTION:
XS GIS Cut Line= 4
     2226792.124    13284077.945     2226640.215    13283951.209
     2226358.097     13283879.16     2226055.145    13283644.785
#Sta/Elev= 30
       0229.619557.22291228.630585.83437227.8953152.5944225.5177288.0143221.6354
297.7626221.0871307.5108219.4239  310.34  218.53 317.259216.3396327.0073216.5656
  330.38  218.54336.7555 222.119346.5038222.2934 356.252220.8192366.0002220.1007
375.7485219.4231385.4967219.4211404.9932220.0987414.7414220.7746434.2379221.2757
463.4826223.2254473.2308223.3412522.6238223.2453572.4514222.6391662.1409222.2463
741.8649222.6763 761.796222.3334811.6235222.3224851.4855223.5088871.4165224.3968
#Mann= 3 , 0 , 0
       0     .05       0  310.34     .03       0  330.38     .05       0
Bank Sta=310.34,330.38
XS Rating Curve= 0 ,0
Exp/Cntr=0.3,0.1

Type RM Length L Ch R = 1 ,945     ,159,159,159
BEGIN DESCRIPTION:
Mapping XS 0e248459
END DESCRIPTION:
XS GIS Cut Line= 2
      2226682.08      13283960.5      2226136.98     13283436.23
#Sta/Elev= 30
    4641  225.47  4653.7   225.9  4667.9   224.6    4689   224.6  4710.3  223.53
  4717.3  223.98  4766.9  221.87  4773.9  222.34  4781.1  221.22  4802.2  221.75
  4809.4  220.54  4816.3  220.97  4823.5  219.68  4830.5  220.41  4837.7  219.89
  4844.6  220.94  4872.9  220.16  4922.6  217.25  4950.9  213.78  4986.1  213.35
 4988.64  212.71  5014.2  209.98  5017.4  210.48  5021.6   212.8  5063.9  216.79
    5078   219.5  5099.3  220.59  5134.6  219.96  5346.8  220.07  5397.3  220.78
#Mann= 4 ,-1 , 0
    4641      .1       0 4988.64     .07       0  5021.6      .1       0
  5397.3     .05       0
#XS Ineff= 2 ,-1
 4947.94 4957.62  214.19 4963.61  4986.2  213.34
Permanent Ineff=
       F       F
Bank Sta=4988.64,5021.6
XS Rating Curve= 0 ,0
Exp/Cntr=0.3,0.1

Type RM Length L Ch R = 1 ,786     ,50,50,50
BEGIN DESCRIPTION:
Mapping XS 869b8790
END DESCRIPTION:
XS GIS Cut Line= 2
      2226713.39     13283786.94       2226185.6     13283342.48
#Sta/Elev= 30
  4651.9  223.79  4818.9  222.23  4847.5  220.15  4911.2  219.11    4919  217.04
  4960.6  213.62  4968.4  210.44  4974.9   210.8    4980  208.93  5017.6  206.44
 5023.64  208.88  5032.1  213.48    5053  210.64  5067.3  210.51    5075  212.52
  5081.6  211.01  5116.9  208.96  5124.5  210.44    5131  209.75  5138.8  212.77
  5159.6  211.13  5167.4  213.01  5173.9  211.64  5181.7  213.77  5188.2  212.71
  5202.5  214.37  5259.7  212.74  5287.1   215.7  5315.7  213.29  5341.9  213.23
#Mann= 3 , 0 , 0
  4651.9      .1       0    4980     .07       0 5023.64      .1       0
#XS Ineff= 1 ,-1
 5031.82 5180.45  213.41
Permanent Ineff=
       F
Bank Sta=4980,5023.64
XS Rating Curve= 0 ,0
Exp/Cntr=0.3,0.1

Type RM Length L Ch R = 1 ,736     ,363,363,363
BEGIN DESCRIPTION:
Mapping XS 02a19d34
END DESCRIPTION:
XS GIS Cut Line= 2
      2226702.91     13283727.86      2226234.21     13283342.48
#Sta/Elev= 30
  4661.8  223.19  4772.1  221.04  4794.4  221.55  4800.8   220.5  4872.6  218.72
  4901.3  216.68  4942.9   211.9  4957.2  211.54  4965.1  210.06  4971.6  211.42
 4981.82   208.6  4985.9  206.78  5000.3  206.66  5006.5  205.59    5029   208.5
  5035.4  206.95  5043.3  208.93  5064.1  207.43  5121.5  208.27    5128  206.21
  5134.6  207.03  5142.3   211.3  5148.8  209.14  5156.7  212.14  5163.2  211.38
    5171  211.86  5177.5  210.89  5206.2  211.13  5212.7  209.69  5268.6  210.66
#Mann= 3 , 0 , 0
  4661.8      .1       0 4981.82     .07       0    5029      .1       0
#XS Ineff= 3 ,-1
 5043.47 5139.72  209.01  5142.1 5155.23  211.38 5205.74 5249.09  210.76
Permanent Ineff=
       F       F       F
Bank Sta=4981.82,5029
XS Rating Curve= 0 ,0
Exp/Cntr=0.3,0.1

Type RM Length L Ch R = 1 ,373     ,186,186,186
BEGIN DESCRIPTION:
Mapping XS d18eb0df
END DESCRIPTION:
XS GIS Cut Line= 4
      2226682.85     13283575.48      2226609.87      13283405.2
      2226431.45     13283271.38      2226241.81      13283251.2
#Sta/Elev= 30
  4714.6  219.46  4745.7  218.03  4787.4  217.18  4863.6  216.86  4907.1   215.9
    4915  216.79  4921.7  215.73  4936.3  215.72  4942.5  213.73  4950.9  215.84
    4965  214.41  4971.7  209.13  4975.9   206.7  4977.9  205.52  4986.3  205.09
  5000.6     203  5007.1  204.22  5021.7  205.33 5024.25  206.66  5027.9   208.7
  5036.3  211.85  5042.5  216.36    5065  216.25  5077.9  216.98  5092.5   216.3
  5100.9  216.71  5107.1  215.73  5121.7  216.68    5197  217.29  5313.6  217.27
#Mann= 3 , 0 , 0
  4714.6      .1       0  4975.9     .07       0 5024.25      .1       0
Bank Sta=4975.9,5024.25
XS Rating Curve= 0 ,0
Exp/Cntr=0.3,0.1

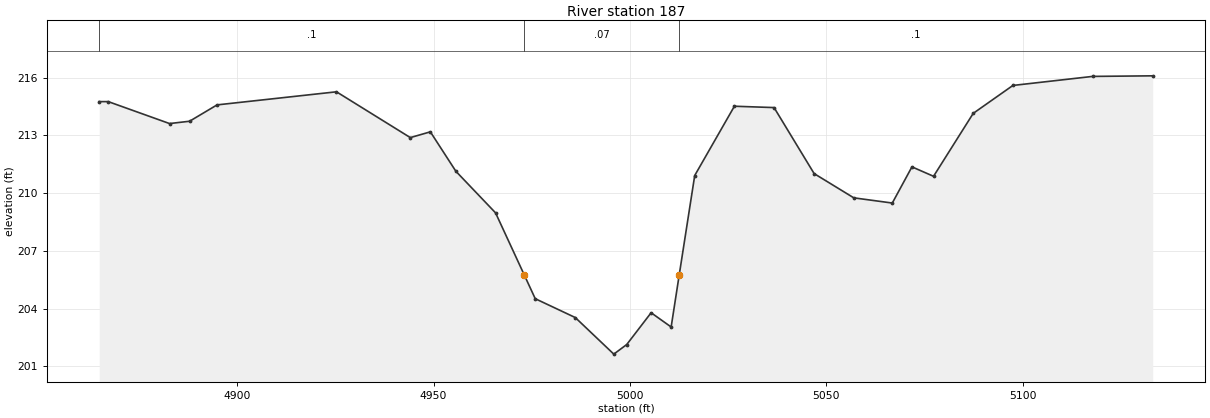
Type RM Length L Ch R = 1 ,187     ,0,0,0
BEGIN DESCRIPTION:
UNT015 IN SPCR 1.0
END DESCRIPTION:
XS GIS Cut Line= 2
      2226727.28     13283158.44      2226462.61     13283201.83
#Sta/Elev= 30
  4864.9  214.76  4867.2  214.76  4882.8  213.62  4887.9  213.74  4894.9  214.59
  4925.3  215.27  4944.1  212.89  4949.2  213.19  4955.7  211.14  4965.8  208.98
 4973.16  205.73  4975.9  204.52  4986.1  203.54  4995.9  201.64  4999.2  202.14
  5005.4  203.79  5010.5  203.05 5012.55  205.75  5016.5  210.92  5026.6  214.52
  5036.7  214.45  5046.9  211.02    5057  209.76  5066.8  209.49  5071.8  211.37
  5077.3  210.88  5087.4  214.15  5097.5   215.6  5117.8  216.07  5133.1   216.1
#Mann= 3 , 0 , 0
  4864.9      .1       0 4973.16     .07       0 5012.55      .1       0
Bank Sta=4973.16,5012.55
XS Rating Curve= 0 ,0
Exp/Cntr=0.3,0.1

Chan Stop Cuts=-1
Use User Specified Reach Order=0
Composite Channel Slope=5