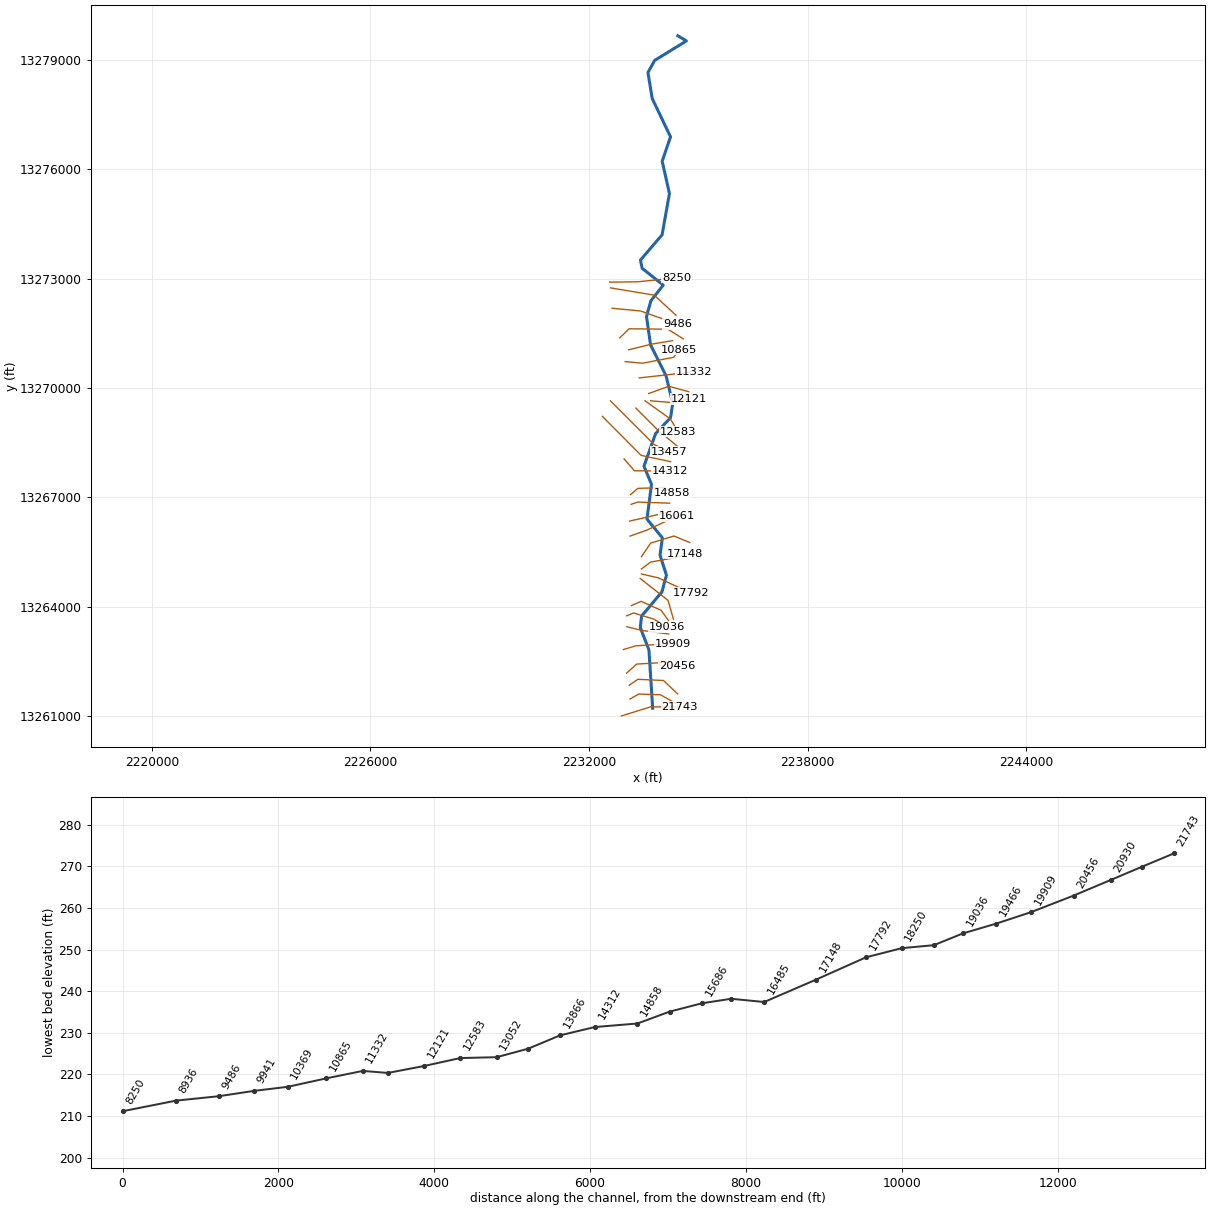
--- UNT016 IN SPCR.prj (project) ---

Proj Title=UNT016 IN SPCR Base Level Engineering
Current Plan=p01
Default Exp/Contr=0.3,0.1
English Units
Geom File=g01
Flow File=f01
Plan File=p01
Y Axis Title=Elevation
X Axis Title(PF)=Main Channel Distance
X Axis Title(XS)=Station
BEGIN DESCRIPTION:
UNT016 IN SPCR
END DESCRIPTION:
DSS Export Rating Curves= 0
DSS Export Rating Curve Sorted= 0
DSS Export Volume Flow Curves= 0
DXF OffsetX= 0
DXF OffsetY= 0
DXF ScaleX= 1
DXF ScaleY= 10

--- UNT016 IN SPCR.p01 (plan) ---

Plan Title=Multiple Run
Short Identifier=Multiple
Geom File=g01
Flow File=f01
Subcritical Flow
K Sum by GR= 0
Std Step Tol= 0.01
Critical Tol= 0.01
Num of Std Step Trials= 20
Max Error Tol= 0.3
Flow Tol Ratio= 0.001
Split Flow NTrial= 30
Split Flow Tol= 0.02
Split Flow Ratio= 0.02
Log Output Level= 0
Friction Slope Method= 1
Unsteady Friction Slope Method= 2
Unsteady Bridges Friction Slope Method= 1
Parabolic Critical Depth
Global Vel Dist=  1 , 1 , 1
Global Log Level= 0
CheckData=True
Encroach Param= -1, 0, 0, 0
BEGIN DESCRIPTION:
Multiple Run
END DESCRIPTION:

--- UNT016 IN SPCR.f01 (steady flow) ---

Flow Title=Multiple
Program Version=4.10
Number of Profiles= 7
Profile Names=10-year,25-year,50-year,1pct_min,100-year,1pct_plu,500-year
River Rch & RM=UNT016 IN SPCR,Reach-1         ,21743
     422     609     769     715     967    1308    1552
River Rch & RM=UNT016 IN SPCR,Reach-1         ,16061
     446     643     813     755    1021    1381    1636
River Rch & RM=UNT016 IN SPCR,Reach-1         ,13866
     809    1198    1542    1457    1970    2664    3264
River Rch & RM=UNT016 IN SPCR,Reach-1         ,13052
     809    1198    1542    1457    1970    2664    3264
River Rch & RM=UNT016 IN SPCR,Reach-1         ,8250
     831    1228    1579    1489    2013    2723    3326
River Rch & RM=UNT016 IN SPCR,Reach-1         ,3666
     869    1285    1652    1557    2106    2848    3478
Boundary for River Rch & Prof#=UNT016 IN SPCR,Reach-1         , 1
Up Type= 0
Dn Type= 3
Dn Slope=0.005
Boundary for River Rch & Prof#=UNT016 IN SPCR,Reach-1         , 2
Up Type= 0
Dn Type= 3
Dn Slope=0.005
Boundary for River Rch & Prof#=UNT016 IN SPCR,Reach-1         , 3
Up Type= 0
Dn Type= 3
Dn Slope=0.005
Boundary for River Rch & Prof#=UNT016 IN SPCR,Reach-1         , 4
Up Type= 0
Dn Type= 3
Dn Slope=0.005
Boundary for River Rch & Prof#=UNT016 IN SPCR,Reach-1         , 5
Up Type= 0
Dn Type= 3
Dn Slope=0.005
Boundary for River Rch & Prof#=UNT016 IN SPCR,Reach-1         , 6
Up Type= 0
Dn Type= 3
Dn Slope=0.005
Boundary for River Rch & Prof#=UNT016 IN SPCR,Reach-1         , 7
Up Type= 0
Dn Type= 3
Dn Slope=0.005
DSS Import GetInterval= 0
DSS Import GetPeak= 0
DSS Import FillOption= 0

--- UNT016 IN SPCR.g01 (geometry) ---

Geom Title=Existing Conditions
Program Version=4.10

River Reach=UNT016 IN SPCR  ,Reach-1
Reach XY= 30
      2233747.72     13261206.86      2233645.29     13262808.76
       2233407.7     13263422.08      2233443.32     13263739.21
       2234002.1     13264404.39      2234125.47     13264862.69
      2233948.42     13265411.65      2234014.16     13265885.18
      2233591.29     13266401.48      2233714.99     13267358.51
      2233508.11     13267851.53      2233827.72     13268746.86
      2234237.69     13269184.58      2234297.75     13269577.05
       2234114.1     13270335.35      2233690.51     13271178.01
       2233578.5     13271960.86      2233698.17     13272391.31
       2234037.5     13272822.56      2233457.17     13273284.38
      2233412.56      13273510.5      2234005.92     13274202.59
      2234207.46     13275336.84      2234008.32     13276221.61
      2234237.18     13276891.67      2233733.25     13277948.76
      2233617.94     13278657.53      2233801.05     13278988.98
      2234672.55     13279524.27      2234437.72     13279666.85

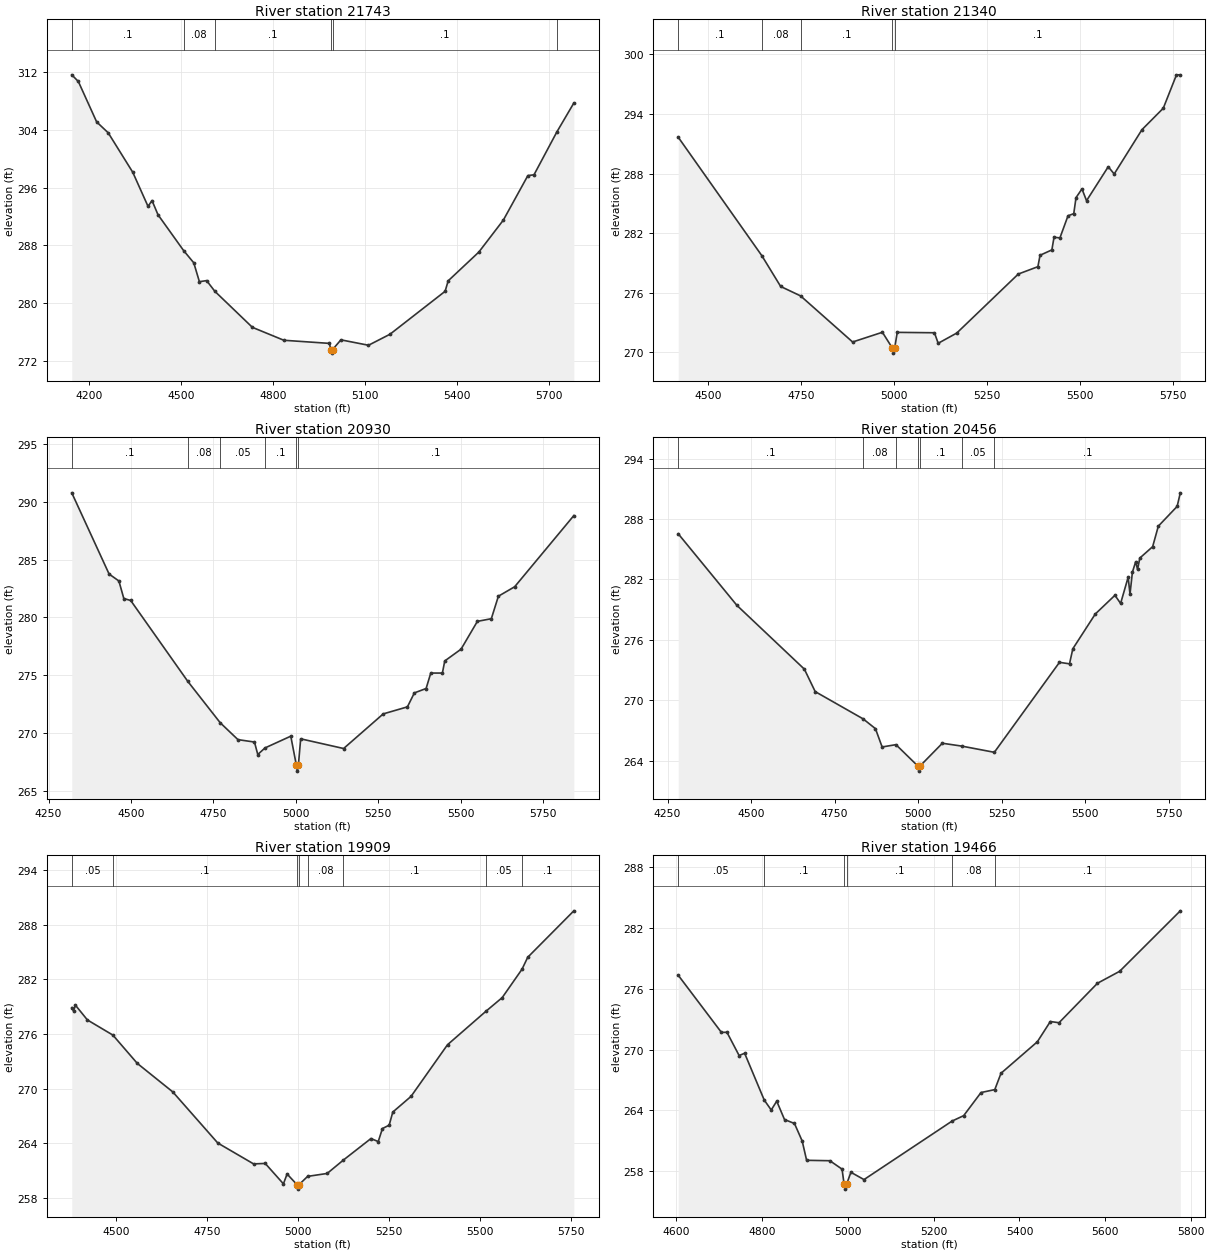
Type RM Length L Ch R = 1 ,21743   ,403,403,403
BEGIN DESCRIPTION:
UNT016 IN SPCR 41.0
END DESCRIPTION:
XS GIS Cut Line= 3
      2232887.76     13260996.87      2233687.72     13261246.85
      2234487.71     13261246.85
#Sta/Elev= 30
  4142.7  311.61  4164.1  310.69  4223.9  305.09  4261.6  303.58  4341.7  298.12
  4391.5   293.4  4404.6   294.2    4424  292.24  4507.6  287.28  4540.8  285.58
  4559.1  282.97  4582.7  283.12  4609.5  281.64    4732  276.65  4834.7  274.86
  4983.3  274.43  4987.8  273.58  4990.6  273.08  4993.8  273.58  5020.8  274.92
  5110.8  274.17  5180.8  275.69  5360.8  281.64  5370.8  283.09  5470.8  287.07
  5550.8   291.5  5630.8  297.66  5650.8  297.77  5725.2  303.69  5780.8  307.71
#Mann= 6 ,-1 , 0
  4142.7      .1       0  4507.6     .08       0  4609.5      .1       0
  4987.8     .07       0  4993.8      .1       0  5725.2     .05       0
Bank Sta=4987.8,4993.8
XS Rating Curve= 0 ,0
Exp/Cntr=0.3,0.1

Type RM Length L Ch R = 1 ,21340   ,410,410,410
BEGIN DESCRIPTION:
UNT016 IN SPCR 40.0
END DESCRIPTION:
XS GIS Cut Line= 4
      2233124.76       13261462.      2233366.16     13261599.02
      2233959.99     13261579.44      2234377.62     13261344.52
#Sta/Elev= 30
    4419  291.66  4643.9  279.74  4694.6  276.64  4748.2  275.69  4888.2  271.05
  4968.3  272.03  4995.3  270.43  4998.1  269.93  5001.3  270.43  5008.3  272.02
  5108.4  271.98  5118.4  270.92  5168.4  271.95    5334  277.89  5386.7  278.63
  5392.5  279.78  5424.3  280.32  5430.1  281.59    5446  281.53  5467.7  283.75
  5483.2  283.97  5489.3  285.58  5505.3  286.46  5517.6  285.27    5576  288.69
    5592  287.96  5666.7  292.42  5724.1  294.58  5759.6  297.94  5769.9  297.94
#Mann= 5 ,-1 , 0
    4419      .1       0  4643.9     .08       0  4748.2      .1       0
  4995.3     .07       0  5001.3      .1       0
Bank Sta=4995.3,5001.3
XS Rating Curve= 0 ,0
Exp/Cntr=0.3,0.1

Type RM Length L Ch R = 1 ,20930   ,474,474,474
BEGIN DESCRIPTION:
UNT016 IN SPCR 39.0
END DESCRIPTION:
XS GIS Cut Line= 4
      2233105.13     13261840.46      2233340.06      13262003.6
      2234044.82     13261970.98      2234429.86     13261605.52
#Sta/Elev= 30
  4320.5   290.8  4433.7  283.76  4463.4  283.16  4478.3  281.64  4499.2  281.47
  4672.3  274.46  4770.7  270.87  4824.4  269.41  4874.5   269.2  4884.5  268.12
  4906.4  268.69  4984.6  269.71  5001.6  267.18  5004.4  266.68  5007.6  267.18
  5014.6  269.48  5144.8  268.64  5264.9  271.64  5338.3  272.25  5359.3  273.46
  5394.9  273.84  5409.1  275.18  5444.3  275.18  5451.5  276.23  5500.9  277.25
  5550.4  279.66  5592.7  279.89  5614.1  281.84  5663.5  282.66  5842.9  288.83
#Mann= 6 ,-1 , 0
  4320.5      .1       0  4672.3     .08       0  4770.7     .05       0
  4906.4      .1       0  5001.6     .07       0  5007.6      .1       0
Bank Sta=5001.6,5007.6
XS Rating Curve= 0 ,0
Exp/Cntr=0.3,0.1

Type RM Length L Ch R = 1 ,20456   ,547,547,547
BEGIN DESCRIPTION:
UNT016 IN SPCR 38.0
END DESCRIPTION:
XS GIS Cut Line= 4
      2233033.35     13262173.27      2233307.43     13262421.24
      2234214.49     13262473.45      2234416.78     13262375.56
#Sta/Elev= 30
  4282.1  286.53  4457.7  279.42  4659.7  273.08  4692.1  270.85  4835.6  268.14
  4872.4  267.17  4892.4  265.35  4933.8  265.58  4999.6  263.45  5002.3  262.95
  5005.6  263.45  5072.7  265.72  5130.2  265.44  5228.3  264.82  5423.3  273.76
  5453.3  273.61  5463.3  275.11  5530.5  278.56  5589.3  280.42  5606.3  279.61
  5628.9  282.22  5634.4  280.53  5641.6  282.72  5651.5  283.76    5657  282.99
  5663.8  284.12  5702.2  285.25  5719.2  287.29  5775.5  289.25    5785   290.6
#Mann= 7 ,-1 , 0
  4282.1      .1       0  4835.6     .08       0  4933.8      .1       0
  4999.6     .07       0  5005.6      .1       0  5130.2     .05       0
  5228.3      .1       0
Bank Sta=4999.6,5005.6
XS Rating Curve= 0 ,0
Exp/Cntr=0.3,0.1

Type RM Length L Ch R = 1 ,19909   ,443,443,443
BEGIN DESCRIPTION:
UNT016 IN SPCR 37.0
END DESCRIPTION:
XS GIS Cut Line= 3
      2232941.96     13262819.29      2233287.85     13262923.71
      2234304.26     13262982.35
#Sta/Elev= 30
  4379.3  278.89  4384.1  278.53  4389.4  279.16  4422.3  277.54  4492.2  275.88
  4559.4  272.77  4656.9  269.64  4780.5  264.03  4878.8  261.74  4910.8  261.79
  4960.8  259.55  4970.9  260.63  4997.9  259.47  5000.7  258.97  5003.9  259.47
  5027.3  260.37    5081  260.69  5125.5  262.16  5201.2  264.52  5221.3  264.19
  5232.8  265.62  5251.3  265.99  5261.3  267.43  5311.4  269.15  5411.6  274.82
  5518.2  278.53  5561.8  279.99  5616.3  283.11    5632  284.42  5758.7  289.52
#Mann= 8 ,-1 , 0
  4379.3     .05       0  4492.2      .1       0  4997.9     .07       0
  5003.9      .1       0  5027.3     .08       0  5125.5      .1       0
  5518.2     .05       0  5616.3      .1       0
Bank Sta=4997.9,5003.9
XS Rating Curve= 0 ,0
Exp/Cntr=0.3,0.1

Type RM Length L Ch R = 1 ,19466   ,430,430,430
BEGIN DESCRIPTION:
UNT016 IN SPCR 36.0
END DESCRIPTION:
XS GIS Cut Line= 3
      2233037.73     13263446.85      2233437.72     13263346.85
      2234187.69     13263246.86
#Sta/Elev= 30
  4605.6  277.32  4706.1  271.69    4719   271.7  4747.3  269.41  4760.2  269.63
  4805.8  265.02  4822.1  264.04  4834.9  264.91    4853   263.1  4876.2  262.71
  4894.2  260.98  4904.5  259.08  4958.6  259.04    4987  258.21  4991.7  256.74
  4994.5  256.24  4997.7  256.74  5007.6   257.9  5038.1  257.18  5243.2  262.95
  5270.1  263.48  5310.5  265.76  5342.6  266.05  5357.1  267.66  5441.6  270.76
  5471.9  272.76  5492.1  272.64  5581.6  276.53  5633.3  277.71  5774.5  283.67
#Mann= 6 ,-1 , 0
  4605.6     .05       0  4805.8      .1       0  4991.7     .07       0
  4997.7      .1       0  5243.2     .08       0  5342.6      .1       0
Bank Sta=4991.7,4997.7
XS Rating Curve= 0 ,0
Exp/Cntr=0.3,0.1

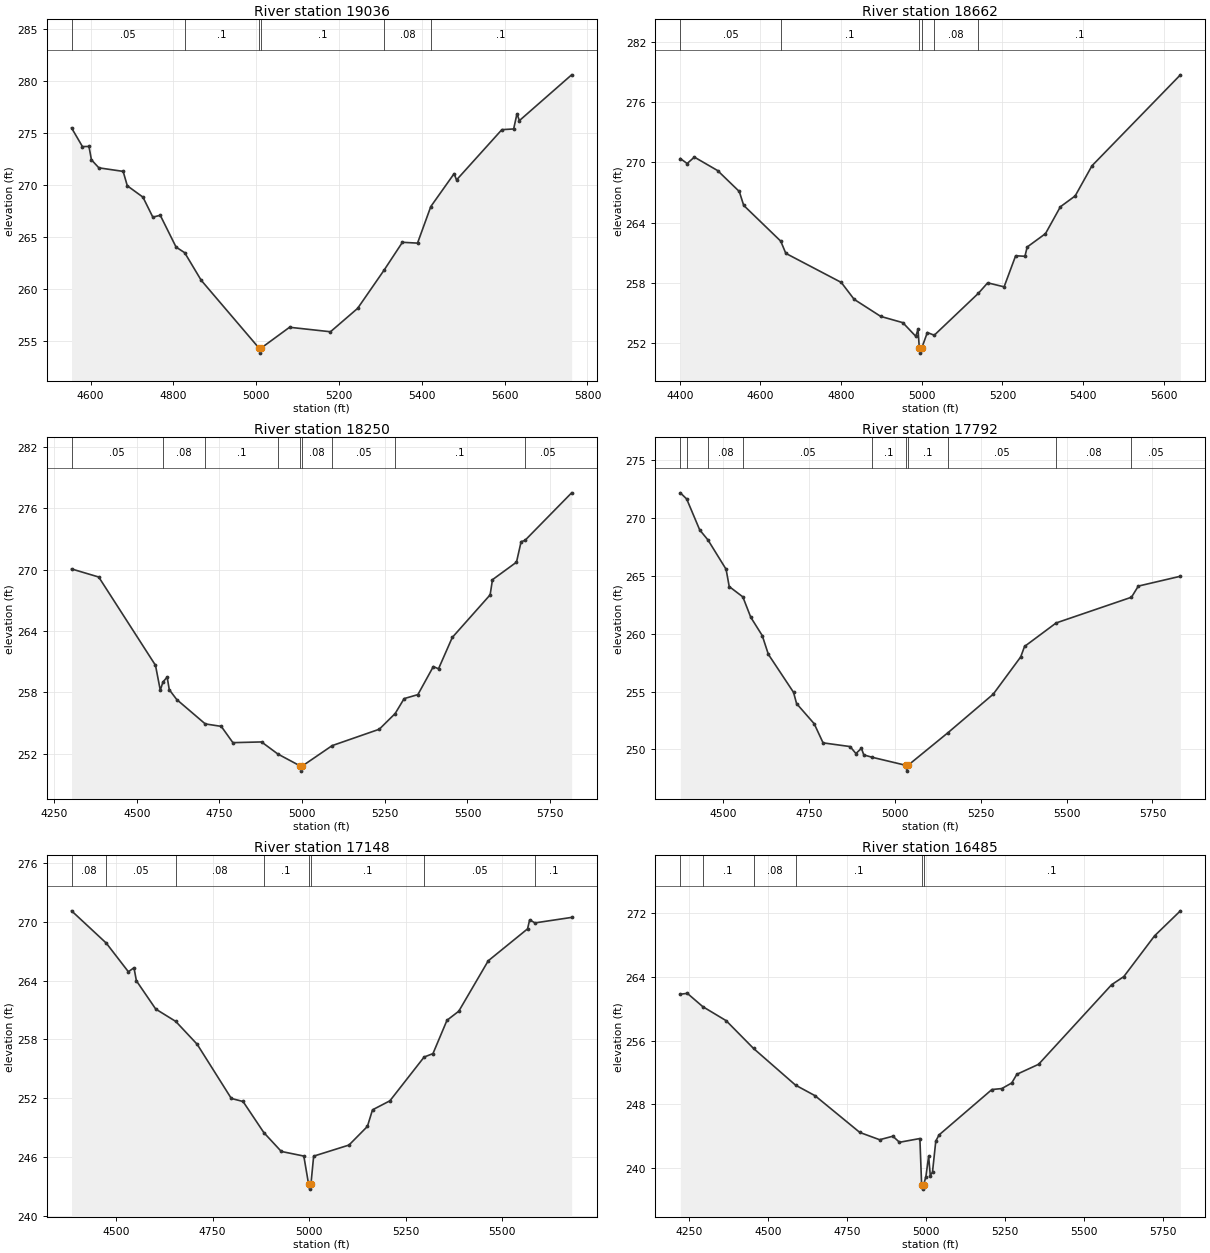
Type RM Length L Ch R = 1 ,19036   ,374,374,374
BEGIN DESCRIPTION:
UNT016 IN SPCR 35.0
END DESCRIPTION:
XS GIS Cut Line= 4
      2233033.39     13263745.95       2233222.6     13263824.25
       2233783.8     13263654.58      2234136.21     13263432.69
#Sta/Elev= 30
  4554.2  275.47  4580.5  273.68  4596.3  273.69  4602.2  272.41  4620.2  271.64
  4678.8   271.3  4688.8  269.92  4726.6  268.83  4750.5  266.91  4768.4  267.09
  4806.6  264.04  4827.4   263.5  4867.2  260.86  5006.5  254.37  5009.2  253.87
  5012.5  254.37  5080.6  256.35  5179.4  255.92  5244.9  258.16  5308.7  261.82
  5353.1   264.5  5389.6  264.42  5421.7  267.93  5477.9  271.08  5483.8  270.48
  5593.2   275.3  5621.7  275.37  5629.7  276.82  5635.6  276.17  5761.7  280.56
#Mann= 6 ,-1 , 0
  4554.2     .05       0  4827.4      .1       0  5006.5     .07       0
  5012.5      .1       0  5308.7     .08       0  5421.7      .1       0
Bank Sta=5006.5,5012.5
XS Rating Curve= 0 ,0
Exp/Cntr=0.3,0.1

Type RM Length L Ch R = 1 ,18662   ,412,412,412
BEGIN DESCRIPTION:
UNT016 IN SPCR 34.0
END DESCRIPTION:
XS GIS Cut Line= 4
      2233163.84     13264026.52      2233431.42       13264144.
      2233979.57     13263896.03      2234181.87     13263615.41
#Sta/Elev= 30
  4401.5  270.39  4418.4  269.89  4436.3  270.53    4494  269.19  4547.7  267.11
  4558.6  265.73  4650.5  262.17    4663  260.96  4800.5  258.07  4832.4  256.39
  4898.4  254.69  4953.1  254.07  4985.3  252.71  4990.8  253.42    4994  251.54
  4996.7  251.04    5000  251.54  5013.9  253.09    5031  252.82  5140.2  256.98
  5163.5  258.03  5204.2  257.63  5232.8  260.72  5255.9  260.67  5261.4  261.59
  5306.8  262.92  5343.7  265.59  5380.4  266.67  5422.1  269.67  5641.3  278.71
#Mann= 6 ,-1 , 0
  4401.5     .05       0  4650.5      .1       0    4994     .07       0
    5000      .1       0    5031     .08       0  5140.2      .1       0
Bank Sta=4994,5000
XS Rating Curve= 0 ,0
Exp/Cntr=0.3,0.1

Type RM Length L Ch R = 1 ,18250   ,458,458,458
BEGIN DESCRIPTION:
UNT016 IN SPCR 33.0
END DESCRIPTION:
XS GIS Cut Line= 4
       2233405.3     13264770.47      2233770.75     13264483.33
      2234168.81      13264170.1      2234318.35     13263649.96
#Sta/Elev= 30
  4302.6  270.06  4384.8  269.27  4556.5  260.65    4571  258.22  4579.2  259.03
  4591.8   259.5  4598.2  258.27  4620.7  257.31    4707  254.93  4755.4  254.69
  4790.6   253.1  4877.3  253.17  4926.6  251.99  4994.5  250.82  4997.3  250.32
  5000.5  250.82  5090.8  252.81  5233.3  254.41  5281.3  255.94  5308.5   257.4
  5350.1  257.79  5396.8  260.53  5412.5  260.31  5454.1  263.37  5568.6  267.53
  5575.7  269.01  5648.3  270.72  5662.3  272.72  5673.8  272.84  5815.1  277.49
#Mann= 9 ,-1 , 0
  4302.6     .05       0  4579.2     .08       0    4707      .1       0
  4926.6     .08       0  4994.5     .07       0  5000.5     .08       0
  5090.8     .05       0  5281.3      .1       0  5673.8     .05       0
Bank Sta=4994.5,5000.5
XS Rating Curve= 0 ,0
Exp/Cntr=0.3,0.1

Type RM Length L Ch R = 1 ,17792   ,644,644,644
BEGIN DESCRIPTION:
UNT016 IN SPCR 32.0
END DESCRIPTION:
XS GIS Cut Line= 3
      2233437.92     13264894.45      2233894.73     13264790.03
       2234788.7     13264372.41
#Sta/Elev= 30
  4376.1  272.15  4394.6  271.62  4432.5  268.95  4456.6  268.08  4509.3  265.55
  4518.4  264.06    4558  263.17  4581.1  261.41  4614.5  259.83  4632.3  258.21
  4705.6  254.93  4714.4  253.96  4765.7  252.22  4791.5  250.57  4870.1  250.25
  4887.1  249.65  4903.2   250.1    4910  249.53  4933.8  249.33  5032.6  248.63
  5035.4  248.13  5038.6  248.63  5155.5  251.46  5286.6  254.77  5366.7  257.99
  5377.8  258.89  5469.8  260.92    5689  263.14  5708.9   264.1  5831.4  264.95
#Mann= 10 ,-1 , 0
  4376.1     .08       0  4394.6     .05       0  4456.6     .08       0
    4558     .05       0  4933.8      .1       0  5032.6     .07       0
  5038.6      .1       0  5155.5     .05       0  5469.8     .08       0
    5689     .05       0
Bank Sta=5032.6,5038.6
XS Rating Curve= 0 ,0
Exp/Cntr=0.3,0.1

Type RM Length L Ch R = 1 ,17148   ,663,663,663
BEGIN DESCRIPTION:
UNT016 IN SPCR 31.0
END DESCRIPTION:
XS GIS Cut Line= 4
       2233437.9     13265031.45      2233692.44     13265220.72
      2234442.88     13265357.76      2234638.67     13265449.12
#Sta/Elev= 30
  4384.3  271.11  4474.3  267.82  4531.6   264.9  4546.1  265.31  4552.4  263.98
  4602.5   261.1  4654.4  259.84  4709.9  257.51  4798.4  251.99  4828.8  251.68
  4882.7  248.51  4927.9  246.59  4986.3  246.12  4998.7  243.25  5001.4  242.75
  5004.7  243.25  5011.8  246.11  5103.3  247.24  5151.1  249.14  5164.3  250.83
  5209.4  251.75  5298.1  256.21    5321  256.56  5357.4  259.96  5387.9  260.88
  5464.3  266.02  5566.1  269.27  5571.6  270.19  5585.4  269.88  5680.4  270.44
#Mann= 8 ,-1 , 0
  4384.3     .08       0  4474.3     .05       0  4654.4     .08       0
  4882.7      .1       0  4998.7     .07       0  5004.7      .1       0
  5298.1     .05       0  5585.4      .1       0
Bank Sta=4998.7,5004.7
XS Rating Curve= 0 ,0
Exp/Cntr=0.3,0.1

Type RM Length L Ch R = 1 ,16485   ,424,424,424
BEGIN DESCRIPTION:
UNT016 IN SPCR 30.0
END DESCRIPTION:
XS GIS Cut Line= 4
      2233441.29     13265371.98      2233693.89     13265743.44
      2234332.85     13265936.61      2234763.23     13265758.53
#Sta/Elev= 30
  4222.4  261.81  4244.6  261.92  4293.6  260.25  4367.3   258.5    4454  255.02
    4587  250.42  4648.6   249.1  4790.5  244.49  4853.2  243.58    4895  244.02
  4915.9  243.26  4980.5  243.73    4986  237.89  4988.8  237.39    4992  237.89
  4999.5  238.96  5008.2  241.52  5013.4  239.09  5020.4  239.53  5030.8  243.41
  5041.1  244.18  5208.4  249.87  5239.7  249.99  5271.1  250.69  5287.4  251.78
  5356.1  253.03  5587.4  263.01  5625.8  264.02  5723.2  269.13  5804.9  272.26
#Mann= 6 ,-1 , 0
  4222.4     .08       0  4293.6      .1       0    4454     .08       0
    4587      .1       0    4986     .07       0    4992      .1       0
Bank Sta=4986,4992
XS Rating Curve= 0 ,0
Exp/Cntr=0.3,0.1

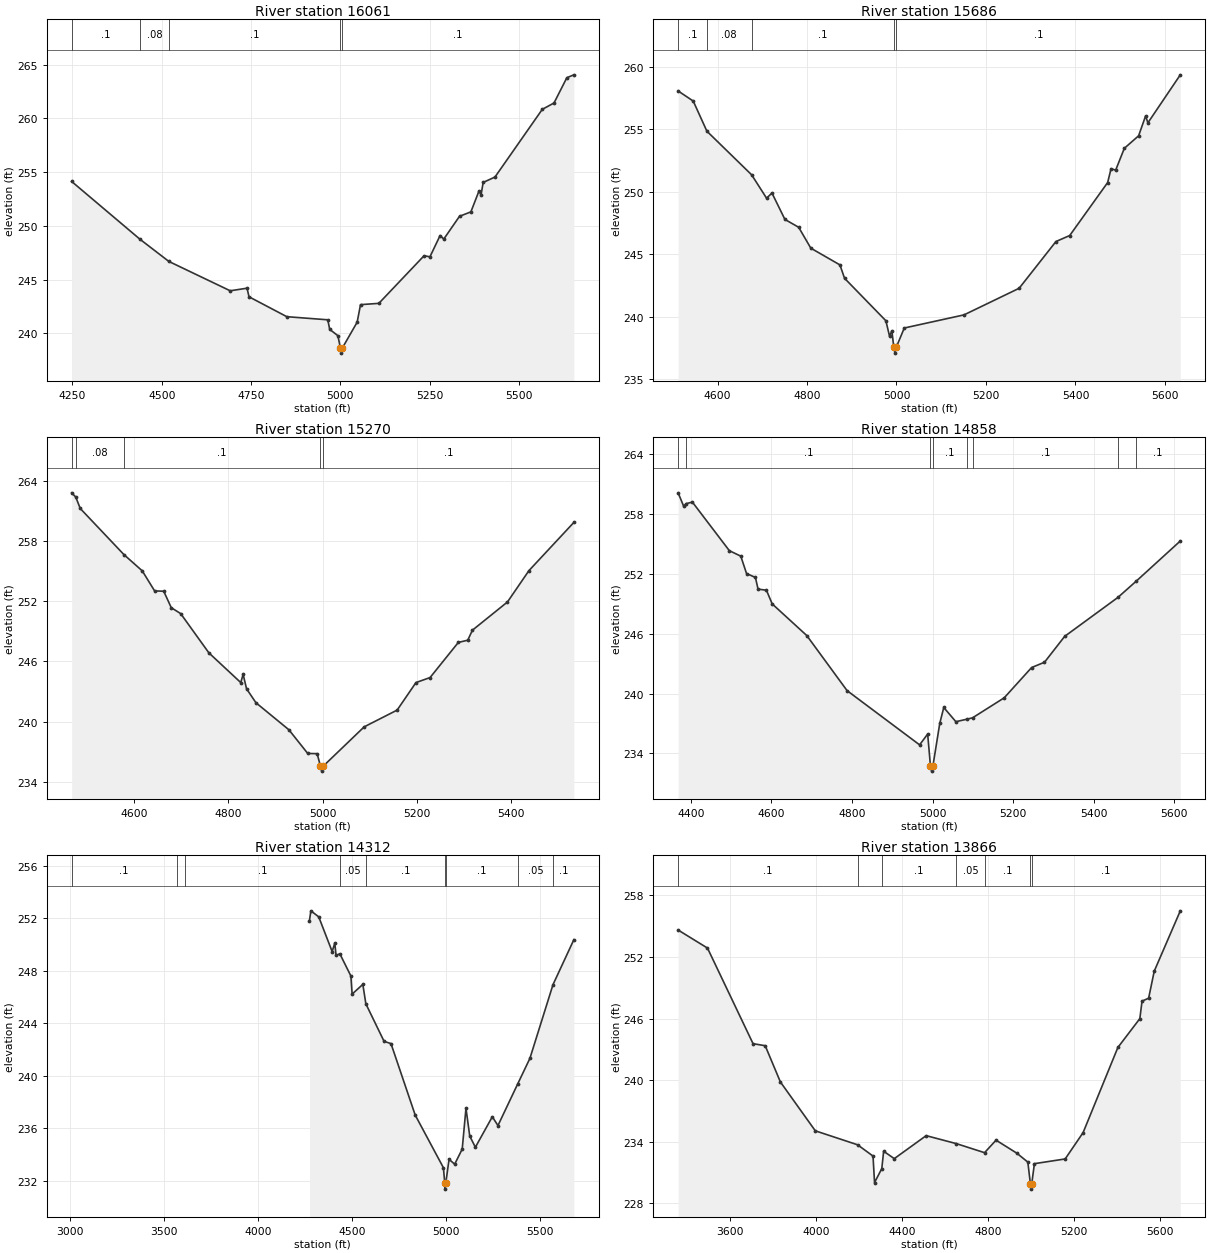
Type RM Length L Ch R = 1 ,16061   ,375,375,375
BEGIN DESCRIPTION:
UNT016 IN SPCR 29.0
END DESCRIPTION:
XS GIS Cut Line= 3
      2233124.69     13265934.33      2233593.44     13266099.26
      2234418.06     13266481.19
#Sta/Elev= 30
  4247.7  254.14  4439.1  248.76  4519.8   246.7  4691.5  243.97  4738.6  244.21
  4744.2  243.41    4850  241.56  4964.6  241.27  4970.1  240.38    4993  239.79
  4999.8  238.67  5002.6  238.17  5005.8  238.67  5046.9  241.05  5056.3  242.68
  5107.6   242.8  5234.2  247.23  5250.6  247.13    5279  249.11  5289.3  248.78
  5333.4   250.9  5365.2  251.31  5388.1  253.27  5393.6  252.87  5399.6  254.05
  5432.6  254.55  5565.1  260.85  5597.9  261.44  5633.8  263.79  5653.4  264.06
#Mann= 5 ,-1 , 0
  4247.7      .1       0  4439.1     .08       0  4519.8      .1       0
  4999.8     .07       0  5005.8      .1       0
Bank Sta=4999.8,5005.8
XS Rating Curve= 0 ,0
Exp/Cntr=0.3,0.1

Type RM Length L Ch R = 1 ,15686   ,416,416,416
BEGIN DESCRIPTION:
UNT016 IN SPCR 28.0
END DESCRIPTION:
XS GIS Cut Line= 3
      2233114.77     13266346.73       2233460.4     13266424.11
      2234208.42     13266599.51
#Sta/Elev= 30
  4511.9  258.07  4545.7  257.26  4576.2  254.85  4676.2  251.36  4709.6  249.49
  4721.7   249.9  4750.6  247.79  4781.4  247.16  4808.5  245.49  4873.6  244.15
  4883.9  243.08  4976.3  239.68  4984.5  238.44  4989.7  238.88  4993.9  237.59
  4996.6  237.09  4999.9  237.59  5017.4   239.1  5150.9  240.15  5274.2  242.28
  5356.4  246.02  5387.2   246.5    5472  250.74  5479.6  251.85  5489.9  251.73
  5509.3  253.48  5541.2  254.48  5556.8  256.07    5562  255.52  5634.4  259.36
#Mann= 5 ,-1 , 0
  4511.9      .1       0  4576.2     .08       0  4676.2      .1       0
  4993.9     .07       0  4999.9      .1       0
Bank Sta=4993.9,4999.9
XS Rating Curve= 0 ,0
Exp/Cntr=0.3,0.1

Type RM Length L Ch R = 1 ,15270   ,412,412,412
BEGIN DESCRIPTION:
UNT016 IN SPCR 27.0
END DESCRIPTION:
XS GIS Cut Line= 3
      2233155.99     13266805.85      2233341.75     13266867.77
      2234213.19     13266836.83
#Sta/Elev= 30
  4466.5  262.79  4475.2  262.37  4484.8  261.23  4577.6  256.64  4616.6  255.02
  4642.9  253.02  4662.3  252.99  4678.3  251.35  4698.3  250.76  4758.3  246.85
  4826.1  243.89  4831.1  244.71  4838.4  243.27  4858.4  241.88  4928.4  239.19
  4968.5  236.83  4988.5  236.81  4995.5  235.57  4998.2  235.07  5001.5  235.57
  5088.5  239.48  5158.6  241.15  5198.6  243.89  5228.6  244.39  5288.7  247.89
  5308.7  248.11  5318.7  249.11  5393.2  251.92  5438.8  255.04  5534.3  259.84
#Mann= 5 ,-1 , 0
  4466.5      .1       0  4475.2     .08       0  4577.6      .1       0
  4995.5     .07       0  5001.5      .1       0
Bank Sta=4995.5,5001.5
XS Rating Curve= 0 ,0
Exp/Cntr=0.3,0.1

Type RM Length L Ch R = 1 ,14858   ,546,546,546
BEGIN DESCRIPTION:
UNT016 IN SPCR 26.0
END DESCRIPTION:
XS GIS Cut Line= 4
       2233140.6     13267074.15      2233341.75     13267244.35
      2234069.13     13267264.99      2234284.24      13267126.7
#Sta/Elev= 30
  4368.3  260.09  4382.2  258.74  4388.3  259.01  4403.8  259.16  4495.5   254.3
  4523.9  253.75  4538.2  252.01  4560.2  251.62  4566.8  250.45  4587.6  250.34
  4601.9  248.97  4687.8   245.8  4787.8  240.29  4967.9  234.86  4987.9  235.94
  4994.9  232.73  4997.7  232.23  5000.9  232.73  5017.9     237  5027.9   238.6
  5057.9  237.18  5086.7  237.44  5099.5  237.57    5178  239.57    5246   242.6
    5278  243.13  5328.1  245.72  5460.3  249.62  5505.3  251.23  5615.2  255.27
#Mann= 8 ,-1 , 0
  4368.3     .08       0  4388.3      .1       0  4994.9     .07       0
  5000.9      .1       0  5086.7     .05       0  5099.5      .1       0
  5460.3     .05       0  5505.3      .1       0
Bank Sta=4994.9,5000.9
XS Rating Curve= 0 ,0
Exp/Cntr=0.3,0.1

Type RM Length L Ch R = 1 ,14312   ,446,446,446
BEGIN DESCRIPTION:
UNT016 IN SPCR 25.0
END DESCRIPTION:
XS GIS Cut Line= 3
  2232963.523322  13268052.79191      2233248.95     13267726.59
      2234221.17     13267719.64
#Sta/Elev= 30
  4275.2  251.83  4282.8  252.57  4324.6  252.11  4395.8  249.47    4410  250.11
  4416.6  249.17  4436.7   249.3  4495.4  247.61  4502.1  246.23    4559  246.97
  4575.1  245.49    4672  242.63  4708.7  242.46  4837.4  237.02  4987.4  233.01
  4994.4  231.88  4997.2  231.38  5000.4  231.88  5017.4  233.65  5047.4  233.28
  5087.4  234.43  5107.4  237.54  5127.4  235.42  5157.4  234.57  5247.4  236.89
  5277.4  236.22  5382.1  239.38  5447.4  241.34  5570.1  246.95  5680.9  250.37
#Mann= 9 ,-1 , 0
  3010.8      .1       0  3569.1     .07       0  3612.4      .1       0
  4436.7     .05       0  4575.1      .1       0  4994.4     .07       0
  5000.4      .1       0  5382.1     .05       0  5570.1      .1       0
Bank Sta=4994.4,5000.4
XS Rating Curve= 0 ,0
Exp/Cntr=0.3,0.1

Type RM Length L Ch R = 1 ,13866   ,409,409,409
BEGIN DESCRIPTION:
UNT016 IN SPCR 24.0
END DESCRIPTION:
XS GIS Cut Line= 3
      2232367.04     13269219.61      2233429.51      13268150.2
      2234241.99     13267976.59
#Sta/Elev= 30
  3357.6  254.63  3494.4  252.87  3706.5  243.56  3763.1  243.36  3833.8  239.83
  3996.4  235.07  4193.2  233.71  4265.1  232.61  4272.2  230.03    4306  231.39
  4314.6  233.08  4364.1  232.36  4512.6   234.6  4653.4  233.82  4784.5  232.94
  4837.9  234.16  4934.8  232.89    4986  232.02    4998  229.89  5000.8  229.39
    5004  229.89  5016.6  231.87  5159.8  232.33  5243.4   234.9  5405.2  243.19
  5507.5     246  5517.7   247.7  5548.4  247.99  5574.5  250.62  5695.9   256.5
#Mann= 7 ,-1 , 0
  3357.6      .1       0  4193.2     .07       0    4306      .1       0
  4653.4     .05       0  4784.5      .1       0    4998     .07       0
    5004      .1       0
Bank Sta=4998,5004
XS Rating Curve= 0 ,0
Exp/Cntr=0.3,0.1

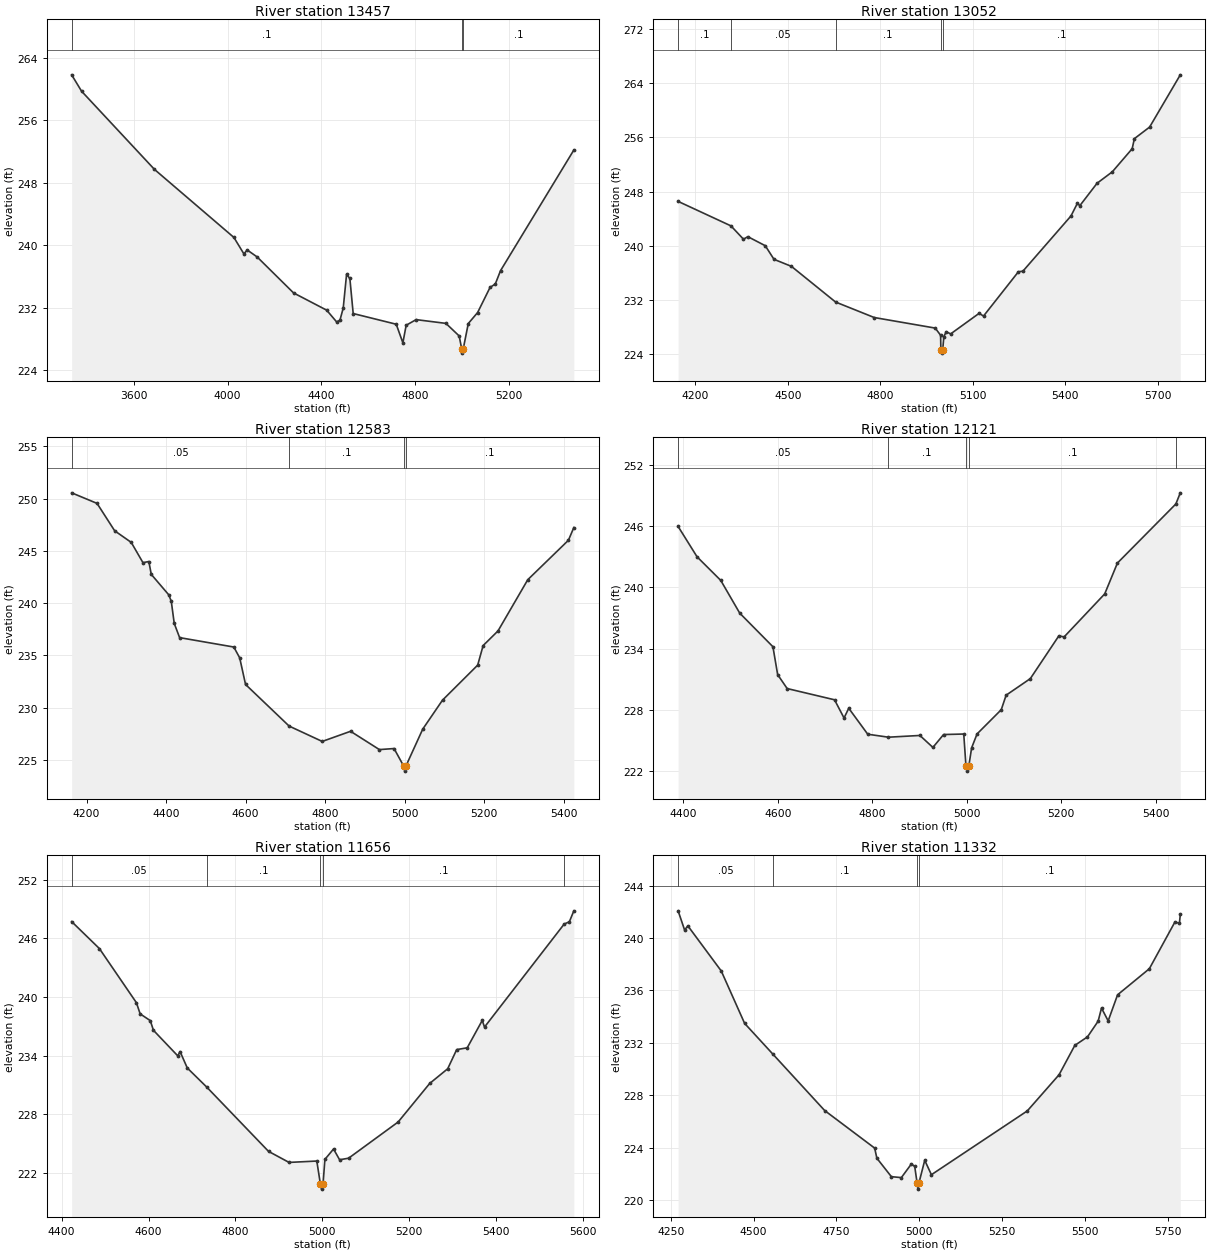
Type RM Length L Ch R = 1 ,13457   ,405,405,405
BEGIN DESCRIPTION:
UNT016 IN SPCR 23.0
END DESCRIPTION:
XS GIS Cut Line= 3
      2232587.74     13269646.84      2233787.72     13268446.85
      2234187.68     13268246.88
#Sta/Elev= 30
  3334.2  261.83  3376.6  259.73  3687.7  249.72  4027.1     241  4069.6   238.9
  4083.7   239.4  4126.1  238.51  4281.7   233.9  4423.1  231.69  4465.5  230.19
  4479.7   230.4  4493.8  231.97    4508  236.27  4522.1  235.75  4536.3  231.26
  4720.1  229.89  4748.4  227.51  4762.5  229.76    4805  230.48  4932.2     230
  4988.8  228.39  4999.9  226.69  5002.7  226.19  5005.9  226.69  5027.7  229.98
  5067.6  231.39  5120.7  234.61    5143  235.04  5165.4  236.75  5478.4   252.2
#Mann= 3 ,-1 , 0
  3334.2      .1       0  4999.9     .07       0  5005.9      .1       0
Bank Sta=4999.9,5005.9
XS Rating Curve= 0 ,0
Exp/Cntr=0.3,0.1

Type RM Length L Ch R = 1 ,13052   ,469,469,469
BEGIN DESCRIPTION:
UNT016 IN SPCR 22.0
END DESCRIPTION:
XS GIS Cut Line= 3
      2233287.75     13269446.82      2233887.72     13268846.85
      2234487.71     13268346.86
#Sta/Elev= 30
  4144.2  246.56  4315.7  242.94  4356.3  240.97  4370.4  241.35    4427  240.01
  4455.3     238  4511.9  236.96  4655.1  231.69  4780.6   229.4  4978.5  227.84
  4995.9  226.78  4996.8  224.64  4999.6  224.14  5002.8  224.64  5006.4  226.57
  5014.2  227.31  5028.5  226.98  5120.9  230.02  5135.2  229.62  5248.5  236.17
  5262.8  236.24    5419  244.41  5439.8  246.28  5447.6  245.92  5503.6  249.24
  5553.1  250.93  5617.5  254.34  5624.7  255.83  5674.1  257.54  5773.7  265.26
#Mann= 5 ,-1 , 0
  4144.2      .1       0  4315.7     .05       0  4655.1      .1       0
  4996.8     .07       0  5002.8      .1       0
Bank Sta=4996.8,5002.8
XS Rating Curve= 0 ,0
Exp/Cntr=0.3,0.1

Type RM Length L Ch R = 1 ,12583   ,462,462,462
BEGIN DESCRIPTION:
UNT016 IN SPCR 21.0
END DESCRIPTION:
XS GIS Cut Line= 3
       2233537.7     13269646.87      2234237.72     13269146.85
      2234437.74     13268796.83
#Sta/Elev= 30
  4162.6  250.55  4226.5  249.54  4270.8  246.92  4312.5  245.81    4342  243.87
  4356.8  243.98  4362.9  242.75  4407.2  240.78  4413.3  240.16  4420.7  238.06
  4434.2   236.7  4570.6   235.8  4585.4  234.76  4600.1  232.22  4709.7  228.24
    4793  226.77  4864.3  227.74  4936.8  225.99  4973.7  226.09  4997.7  224.43
  5000.5  223.93  5003.7  224.43  5045.9  227.95  5095.6  230.72  5184.1  234.07
  5197.8  235.94  5235.2  237.34  5310.1  242.24  5412.3  246.01    5426  247.23
#Mann= 4 ,-1 , 0
  4162.6     .05       0  4709.7      .1       0  4997.7     .07       0
  5003.7      .1       0
Bank Sta=4997.7,5003.7
XS Rating Curve= 0 ,0
Exp/Cntr=0.3,0.1

Type RM Length L Ch R = 1 ,12121   ,465,465,465
BEGIN DESCRIPTION:
UNT016 IN SPCR 20.0
END DESCRIPTION:
XS GIS Cut Line= 3
      2233687.74     13269646.85      2234287.72     13269596.85
      2234737.68     13269696.85
#Sta/Elev= 30
  4389.2  245.97  4429.3     243  4479.5  240.69  4519.6  237.49  4589.9   234.2
  4599.9  231.47    4620  230.11  4720.3  229.01  4740.4  227.23  4750.4  228.18
  4790.6  225.64  4834.4  225.35    4901  225.52  4928.5  224.35  4951.1  225.61
  4993.8  225.66  4998.5  222.53  5001.3  222.03  5004.5  222.53  5010.5  224.31
    5022  225.67  5073.2  228.04  5083.5  229.46  5134.7  231.08  5194.9  235.25
  5206.4  235.17  5292.2  239.37  5319.1  242.39  5442.8  248.17  5452.2  249.26
#Mann= 5 ,-1 , 0
  4389.2     .05       0  4834.4      .1       0  4998.5     .07       0
  5004.5      .1       0  5442.8     .05       0
Bank Sta=4998.5,5004.5
XS Rating Curve= 0 ,0
Exp/Cntr=0.3,0.1

Type RM Length L Ch R = 1 ,11656   ,324,324,324
BEGIN DESCRIPTION:
UNT016 IN SPCR 19.0
END DESCRIPTION:
XS GIS Cut Line= 3
       2233637.7     13269846.85      2234187.72     13270046.85
      2234737.68     13269896.87
#Sta/Elev= 30
  4423.2   247.7  4487.1  244.94  4572.2  239.41  4580.8  238.27  4604.1  237.58
  4611.4  236.59  4667.3  233.98  4672.6  234.42  4689.2  232.74  4733.7   230.8
  4876.1  224.22  4923.3  223.09  4987.2  223.23  4995.5  220.86  4998.2  220.36
  5001.5  220.86  5005.8   223.4  5025.7  224.46  5039.6  223.36  5060.3  223.52
  5174.3  227.22  5246.9  231.16  5288.3  232.66    5309  234.62  5333.2   234.8
  5367.8   237.6    5373  236.92  5556.3  247.45  5568.2  247.68  5578.5   248.8
#Mann= 5 ,-1 , 0
  4423.2     .05       0  4733.7      .1       0  4995.5     .07       0
  5001.5      .1       0  5556.3     .05       0
Bank Sta=4995.5,5001.5
XS Rating Curve= 0 ,0
Exp/Cntr=0.3,0.1

Type RM Length L Ch R = 1 ,11332   ,467,467,467
BEGIN DESCRIPTION:
UNT016 IN SPCR 18.0
END DESCRIPTION:
XS GIS Cut Line= 2
      2233378.37     13270275.78      2234883.99      13270442.3
#Sta/Elev= 30
  4272.6  242.08  4292.1  240.62  4302.1  240.93  4402.7  237.49  4473.2  233.49
  4557.8  231.16  4714.6  226.84  4865.5  223.97  4872.1   223.2  4915.9  221.79
    4946  221.72  4976.2  222.76  4986.3  222.57  4993.3  221.34  4996.1  220.84
  4999.3  221.34  5016.5  223.04  5036.6  221.94  5325.9  226.81  5421.7  229.57
  5469.2  231.81  5507.4  232.46  5539.6  233.66  5549.7  234.66  5569.8  233.68
  5598.2  235.67    5694  237.66    5771  241.22  5784.7  241.14  5787.4   241.8
#Mann= 4 ,-1 , 0
  4272.6     .05       0  4557.8      .1       0  4993.3     .07       0
  4999.3      .1       0
Bank Sta=4993.3,4999.3
XS Rating Curve= 0 ,0
Exp/Cntr=0.3,0.1

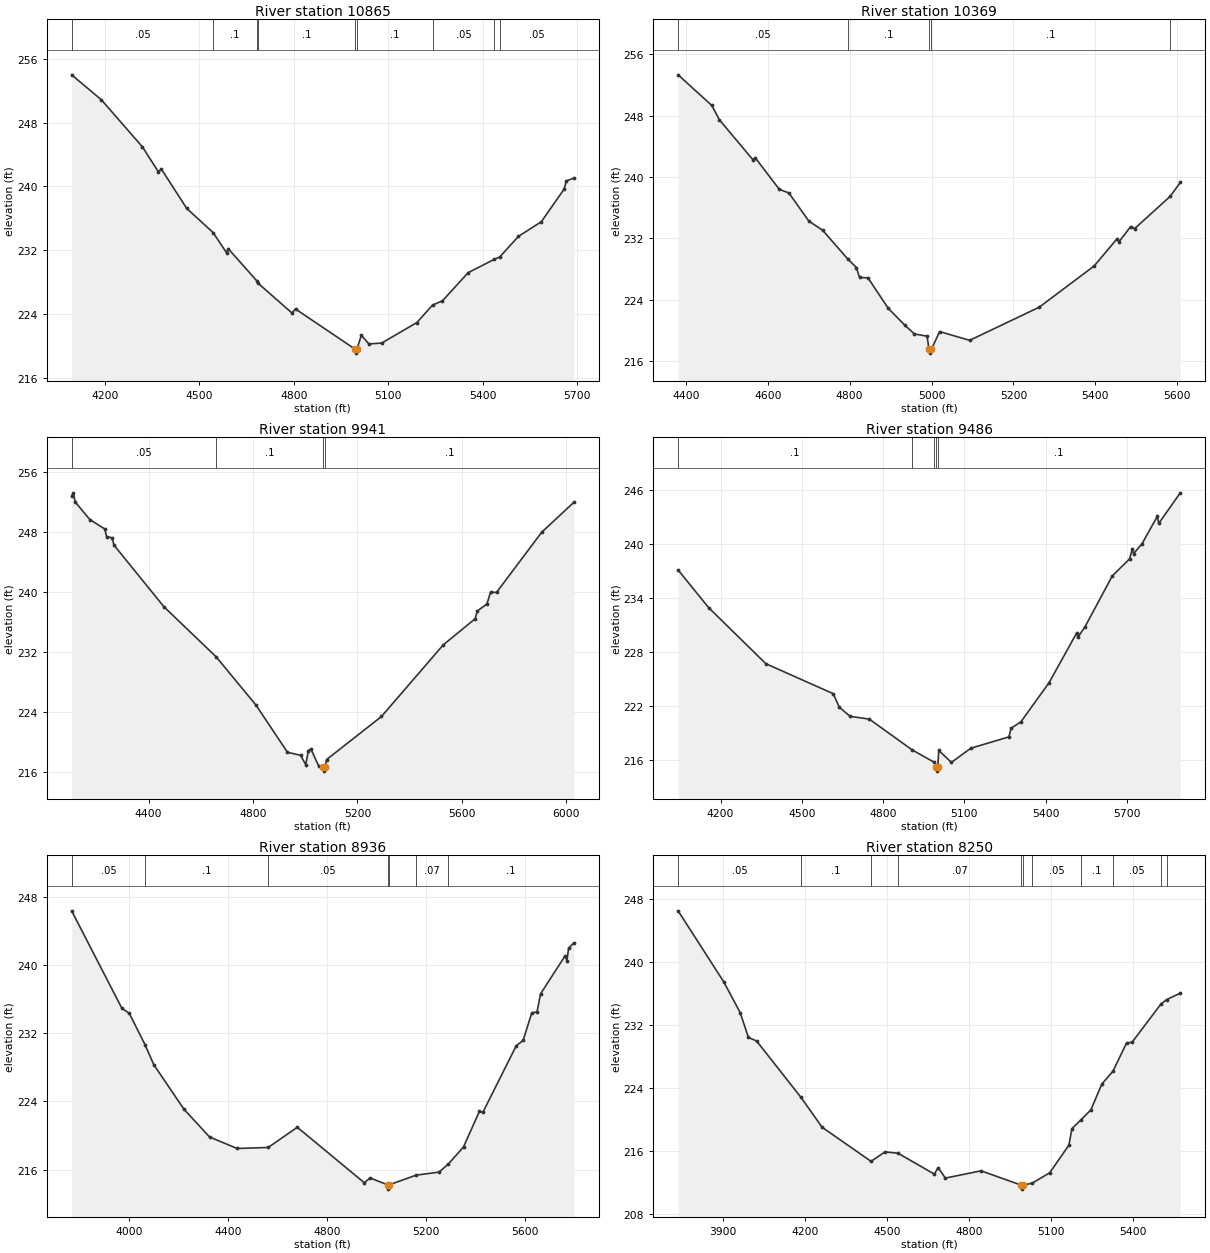
Type RM Length L Ch R = 1 ,10865   ,496,496,496
BEGIN DESCRIPTION:
UNT016 IN SPCR 17.0
END DESCRIPTION:
XS GIS Cut Line= 4
      2232993.54     13270722.67      2233470.98     13270679.26
      2234328.19     13270842.02      2234458.41     13271048.21
#Sta/Elev= 30
  4094.2     254  4188.8  250.86  4319.2  244.95  4369.5  241.84  4379.6  242.15
  4459.9  237.23  4543.9  234.19  4586.5  231.66  4591.6  232.18  4682.1  228.16
    4686  227.86  4794.2   224.1  4805.7   224.6  4994.8  219.56  4997.5  219.06
  5000.8  219.56  5014.7   221.3  5038.5  220.22  5079.2  220.32  5191.2   222.9
  5241.3   225.1  5272.6  225.63  5354.1  229.16  5436.4  230.82  5454.7  231.14
  5513.9  233.72  5586.8  235.56  5659.7  239.69  5665.6  240.67    5690  241.04
#Mann= 9 ,-1 , 0
  4094.2     .05       0  4543.9      .1       0  4682.1     .05       0
    4686      .1       0  4994.8     .07       0  5000.8      .1       0
  5241.3     .05       0  5436.4      .1       0  5454.7     .05       0
Bank Sta=4994.8,5000.8
XS Rating Curve= 0 ,0
Exp/Cntr=0.3,0.1

Type RM Length L Ch R = 1 ,10369   ,428,428,428
BEGIN DESCRIPTION:
UNT016 IN SPCR 16.0
END DESCRIPTION:
XS GIS Cut Line= 3
      2233087.76     13271046.86      2233687.72     13271196.85
      2234287.71     13271296.85
#Sta/Elev= 30
    4381  253.32  4463.4  249.32  4481.5  247.48  4563.9  242.23  4569.1  242.52
  4628.4  238.37  4651.5  237.92  4700.5  234.23    4734  233.05  4795.1  229.32
  4816.5  228.18  4824.2  226.89  4844.8  226.84  4893.8   222.9    4935  220.65
  4958.2  219.52  4989.1  219.23  4993.9  217.52  4996.6  217.02  4999.9  217.52
  5019.7  219.83  5093.2  218.69    5263  223.01  5397.3  228.39  5453.1  231.93
  5458.2  231.56  5486.1  233.51  5496.2  233.27  5582.6  237.45  5607.7  239.28
#Mann= 5 ,-1 , 0
    4381     .05       0  4795.1      .1       0  4993.9     .07       0
  4999.9      .1       0  5582.6     .05       0
Bank Sta=4993.9,4999.9
XS Rating Curve= 0 ,0
Exp/Cntr=0.3,0.1

Type RM Length L Ch R = 1 ,9941    ,455,455,455
BEGIN DESCRIPTION:
UNT016 IN SPCR 15.0
END DESCRIPTION:
XS GIS Cut Line= 4
      2232841.66     13271373.72      2233102.06     13271623.27
      2234165.43     13271612.42      2234587.68     13271346.88
#Sta/Elev= 30
  4105.5  252.79  4112.1  253.28    4119  252.06  4175.6  249.69  4232.2  248.45
  4239.2  247.43  4260.6  247.26  4267.5  246.29  4458.7  238.05    4659  231.34
  4811.8  224.87  4931.9  218.58  4981.9  218.18  5001.9  216.93  5011.9   218.8
  5021.9  218.99  5051.9  216.72  5068.9  216.56  5071.6  216.06  5074.9  216.56
  5081.9  217.61  5291.9  223.37  5528.2  232.94  5650.4  236.44  5659.2  237.49
  5695.7  238.42  5709.5     240  5732.3  239.96  5905.4  248.01  6028.4  252.01
#Mann= 4 ,-1 , 0
  4105.5     .05       0    4659      .1       0  5068.9     .07       0
  5074.9      .1       0
Bank Sta=5068.9,5074.9
XS Rating Curve= 0 ,0
Exp/Cntr=0.3,0.1

Type RM Length L Ch R = 1 ,9486    ,550,550,550
BEGIN DESCRIPTION:
UNT016 IN SPCR 14.0
END DESCRIPTION:
XS GIS Cut Line= 3
      2232635.43     13272187.51      2233416.73     13272111.55
       2234424.3     13271754.03
#Sta/Elev= 30
  4043.1   237.1  4155.9  232.92  4366.9   226.7  4615.7  223.37  4638.2  221.87
  4678.4  220.85  4748.7  220.55  4907.1  217.13  4988.8  215.75  4995.9  215.27
  4998.7  214.77  5001.9  215.27  5005.4  217.07    5052  215.74  5123.6  217.31
  5264.2  218.57  5272.6  219.53  5308.8  220.25  5412.7  224.59  5514.2  230.09
  5519.6  229.66  5545.1  230.78  5646.2  236.45  5709.8  238.33  5719.7  239.39
    5725  238.93  5755.9  240.02  5812.3  243.06  5817.6  242.28  5897.2  245.67
#Mann= 5 ,-1 , 0
  4043.1      .1       0  4907.1     .07       0  4988.8      .1       0
  4995.9     .07       0  5001.9      .1       0
Bank Sta=4995.9,5001.9
XS Rating Curve= 0 ,0
Exp/Cntr=0.3,0.1

Type RM Length L Ch R = 1 ,8936    ,686,686,686
BEGIN DESCRIPTION:
UNT016 IN SPCR 13.0
END DESCRIPTION:
XS GIS Cut Line= 3
      2232587.71     13272746.86      2233787.72     13272546.85
      2234387.71     13271996.86
#Sta/Elev= 30
  3766.7  246.37  3969.5  234.95  3999.9  234.33  4063.4  230.66  4098.7  228.32
  4220.4   223.1  4324.3  219.83  4435.8  218.48  4561.4   218.6  4679.1  220.97
  4950.3  214.45  4973.1  215.03  5044.1  214.21  5046.8  213.71  5050.1  214.21
  5159.5  215.35  5252.4  215.71  5289.9  216.66  5351.1  218.66  5415.2  222.83
  5429.4  222.72  5563.8  230.51  5592.2  231.17  5627.3  234.41  5648.3  234.49
  5662.5  236.62  5761.8  241.09  5769.2  240.54  5775.9  241.96  5797.2  242.61
#Mann= 7 ,-1 , 0
  3766.7     .05       0  4063.4      .1       0  4561.4     .05       0
  5044.1    .033       0  5050.1     .05       0  5159.5     .07       0
  5289.9      .1       0
Bank Sta=5044.1,5050.1
XS Rating Curve= 0 ,0
Exp/Cntr=0.3,0.1

Type RM Length L Ch R = 1 ,8250    ,491,491,491
BEGIN DESCRIPTION:
UNT016 IN SPCR 12.0
END DESCRIPTION:
XS GIS Cut Line= 3
      2232570.38     13272903.65      2233351.62      13272914.5
      2234403.43     13273022.94
#Sta/Elev= 30
    3735  246.44  3902.4  237.42  3962.4  233.52  3992.4  230.39  4022.4  229.94
  4184.9  222.79  4262.4     219  4441.4  214.68  4492.4  215.88  4539.6  215.72
  4673.2  213.06  4686.9  213.88  4713.5  212.56  4844.1  213.48  4991.9  211.66
  4994.7  211.16  4997.9  211.66  5031.6  211.92  5095.5  213.23  5165.8  216.73
    5177  218.83  5210.8  219.97  5246.3  221.21  5286.5  224.49  5326.8  226.09
  5376.9  229.69  5397.1  229.78  5502.5  234.61  5523.6  235.19  5573.7     236
#Mann= 11 ,-1 , 0
    3735     .05       0  4184.9      .1       0  4441.4     .05       0
  4539.6     .07       0  4991.9     .07       0  4997.9     .07       0
  5031.6     .05       0  5210.8      .1       0  5326.8     .05       0
  5502.5     .08       0  5523.6     .05       0
Bank Sta=4991.9,4997.9
XS Rating Curve= 0 ,0
Exp/Cntr=0.3,0.1