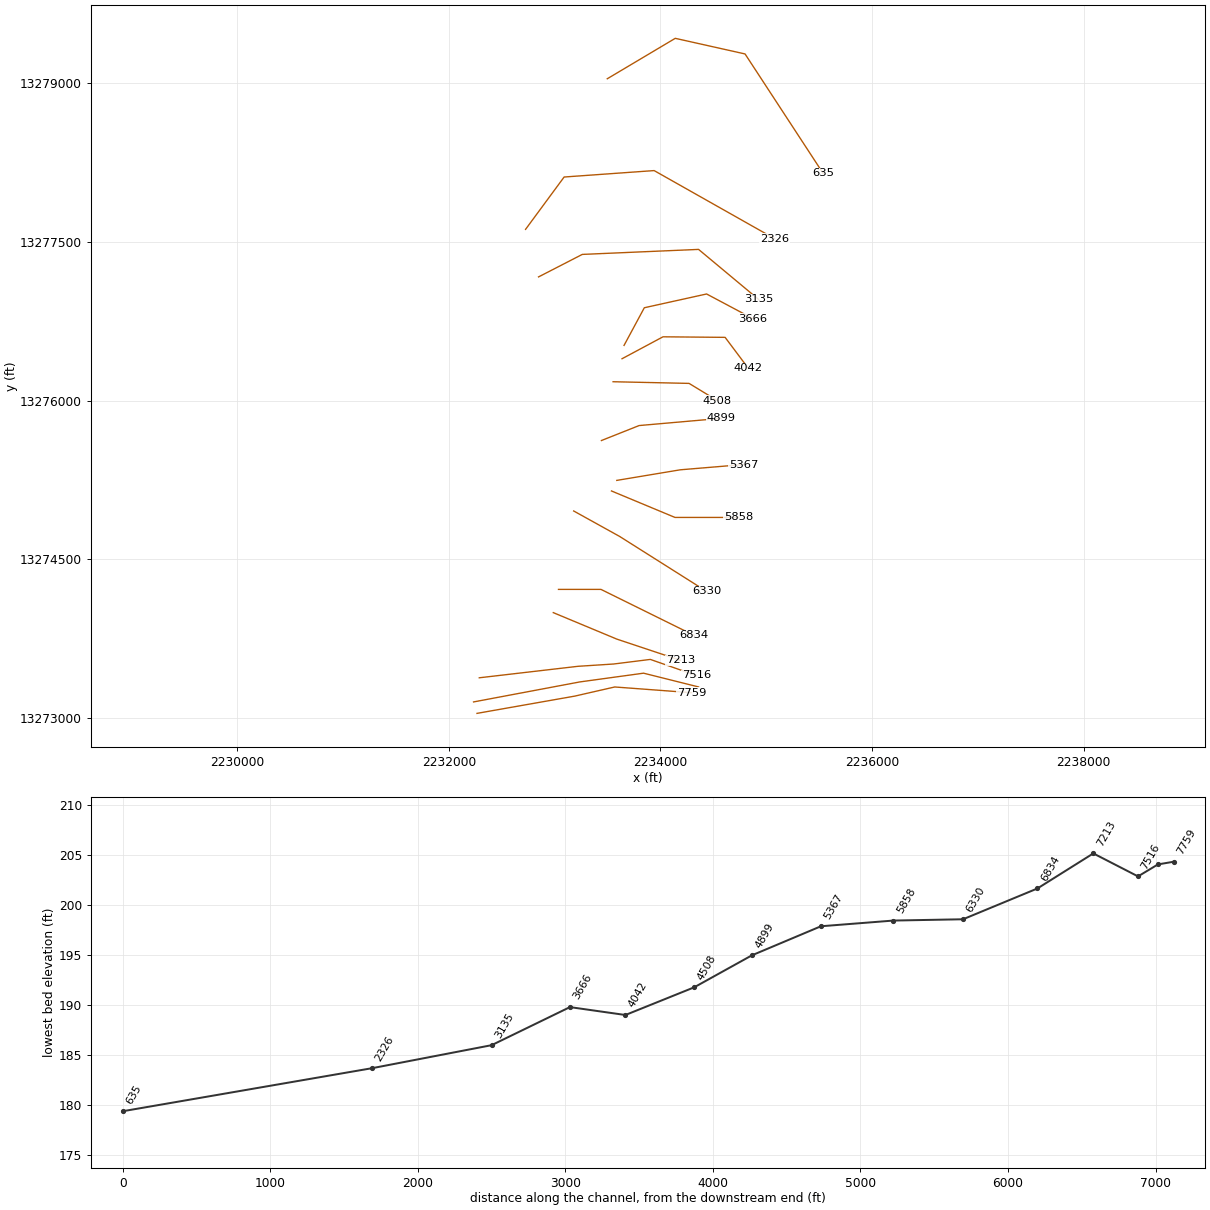
HEC-RAS study UNT016 IN SPCR.prj: UNT016 IN SPCR Base Level Engineering

--- UNT016 IN SPCR.g01 (geometry) --- (continued)

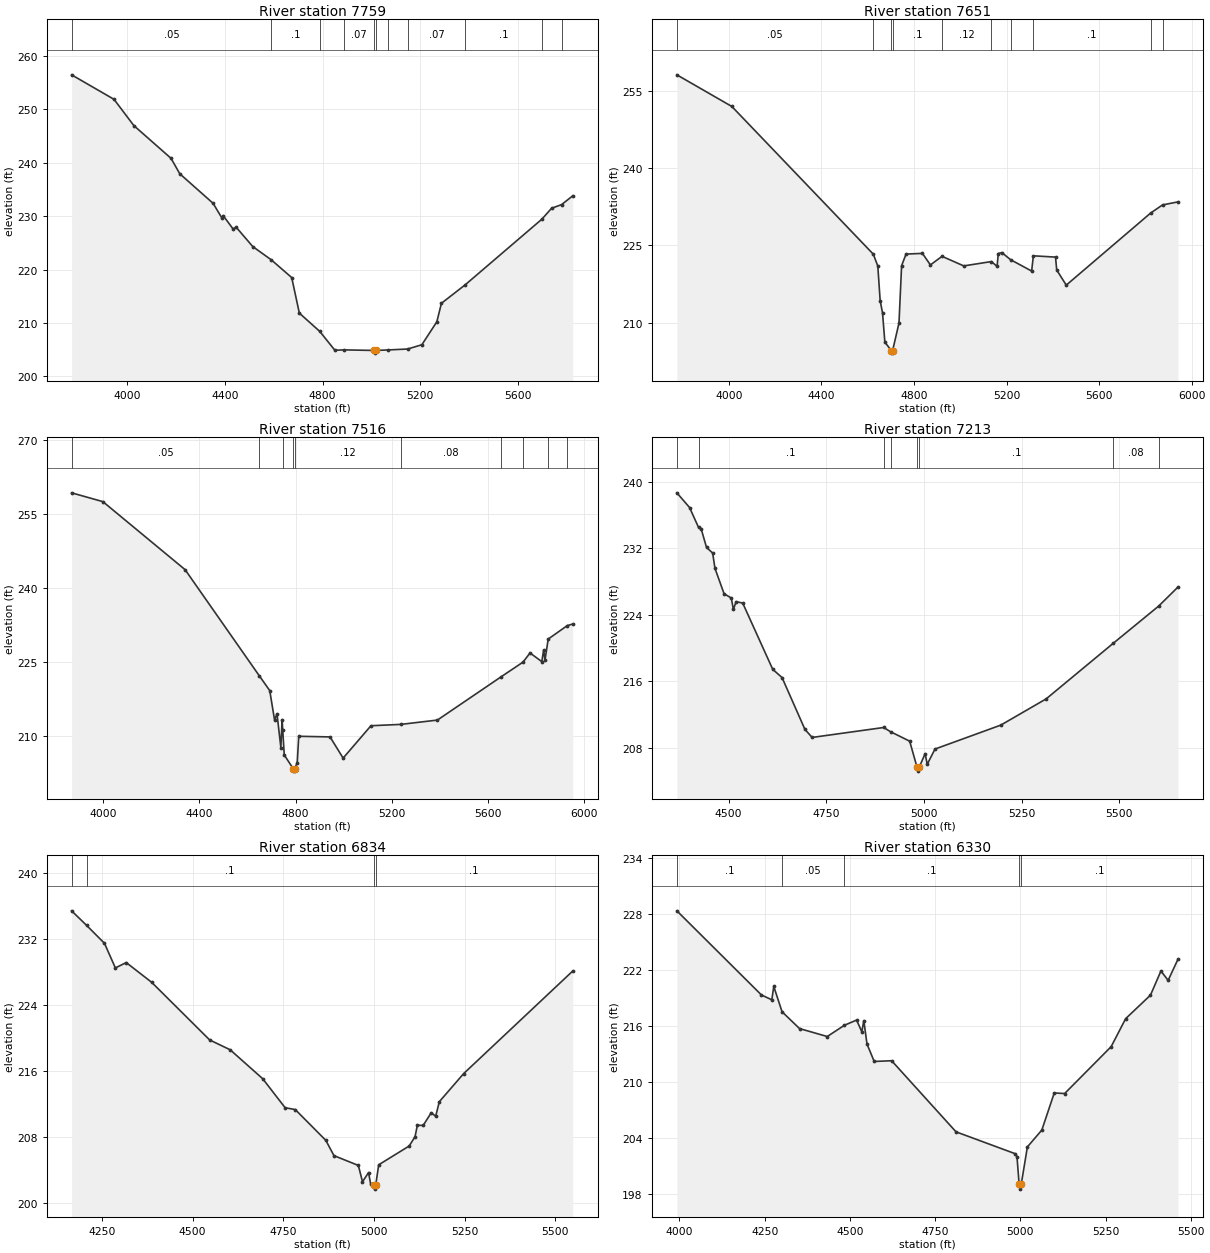
Type RM Length L Ch R = 1 ,7759    ,108,108,108
BEGIN DESCRIPTION:
Mapping XS 75612766
END DESCRIPTION:
XS GIS Cut Line= 4
      2232266.55     13273044.71      2233188.86     13273207.47
      2233568.64     13273294.28      2234294.19     13273240.13
#Sta/Elev= 30
    3771  256.48  3944.8  251.89  4026.1  246.97  4178.4  240.84  4214.4  237.94
    4351   232.4    4387  229.65  4392.1  230.11  4432.2  227.63  4446.3  227.88
  4513.5   224.3  4589.1  221.82  4673.1  218.49  4704.4  211.83  4788.1   208.4
    4850  204.87  4888.2  204.94  5011.1  204.83  5013.9  204.33  5017.1  204.83
  5069.5  204.93  5148.2   205.1  5206.5   205.9  5267.9   210.2  5286.7  213.67
  5384.4  217.14  5698.9  229.45    5738  231.47  5779.1  232.16  5824.7   233.8
#Mann= 11 ,-1 , 0
    3771     .05       0  4589.1      .1       0  4788.1     .12       0
  4888.2     .07       0  5011.1     .07       0  5017.1     .07       0
  5069.5     .12       0  5148.2     .07       0  5384.4      .1       0
  5698.9     .08       0  5779.1     .05       0
Bank Sta=5011.1,5017.1
XS Rating Curve= 0 ,0
Exp/Cntr=0.3,0.1

Type RM Length L Ch R = 1 ,7651    ,135,135,135
BEGIN DESCRIPTION:
UNT016 IN SPCR 11.0
END DESCRIPTION:
XS GIS Cut Line= 4
      2232234.09     13273152.89      2233238.41     13273341.93
        2233841.     13273424.64      2234360.91     13273294.67
#Sta/Elev= 30
  3774.9  258.14  4012.6  251.99    4624  223.29  4643.5  220.99  4653.7  214.25
  4663.9   211.9    4674  206.21  4701.6  204.56  4704.3  204.06  4707.6  204.56
  4735.1  209.91  4746.4  221.05  4765.6  223.31  4836.5  223.44  4870.8   221.2
  4921.2  222.87    5015  221.01  5134.4  221.85  5159.2  220.92  5164.3  223.41
  5179.7   223.6  5217.3  222.22  5308.5  220.01    5316  222.97  5411.7  222.72
  5416.9  220.22  5458.1  217.27  5822.9  231.28  5874.3  232.86    5941  233.45
#Mann= 10 ,-1 , 0
  3774.9     .05       0    4624      .1       0  4701.6     .07       0
  4707.6      .1       0  4921.2     .12       0  5134.4     .08       0
  5217.3     .12       0    5316      .1       0  5822.9     .08       0
  5874.3     .05       0
Bank Sta=4701.6,4707.6
XS Rating Curve= 0 ,0
Exp/Cntr=0.3,0.1

Type RM Length L Ch R = 1 ,7516    ,303,303,303
BEGIN DESCRIPTION:
Mapping XS cd4a050f
END DESCRIPTION:
XS GIS Cut Line= 5
      2232288.29     13273381.09      2233221.41     13273489.59
      2233557.79     13273511.29      2233905.01      13273554.7
      2234339.08     13273402.77
#Sta/Elev= 30
  3867.5  259.32  3997.8  257.53  4340.1  243.73  4648.4  222.24  4692.5   219.2
  4712.6  213.22  4722.7  214.49  4738.8  207.64  4743.9   213.3  4746.6  211.15
  4752.9  206.14  4790.1  203.36  4792.9  202.86  4796.1  203.36  4806.9  204.54
  4813.2  209.93  4943.5   209.8    4998   205.5  5113.9  212.07  5238.2  212.34
  5390.6  213.22  5655.9     222  5746.8  224.97  5776.2  226.83  5825.2  225.08
    5833  227.48  5838.3  225.34  5851.9  229.66  5931.2  232.38  5953.8   232.7
#Mann= 10 ,-1 , 0
  3867.5     .05       0  4648.4     .08       0  4746.6     .12       0
  4790.1     .07       0  4796.1     .12       0  5238.2     .08       0
  5655.9      .1       0  5746.8     .08       0  5851.9      .1       0
  5931.2     .08       0
Bank Sta=4790.1,4796.1
XS Rating Curve= 0 ,0
Exp/Cntr=0.3,0.1

Type RM Length L Ch R = 1 ,7213    ,379,379,379
BEGIN DESCRIPTION:
UNT016 IN SPCR 10.0
END DESCRIPTION:
XS GIS Cut Line= 3
      2232987.69     13273996.87      2233587.72     13273746.85
      2234187.73     13273546.85
#Sta/Elev= 30
  4367.5  238.71    4400  236.94  4422.9  234.55  4429.8  234.35  4443.4  232.13
  4459.1  231.45    4465  229.61  4488.3  226.55  4506.7  226.03  4512.2  224.66
  4519.2  225.59    4536  225.42  4612.9  217.43  4636.7  216.44  4695.2   210.2
  4713.7  209.22  4896.8  210.42  4914.4  209.91  4963.4  208.77    4982  205.66
  4984.8  205.16    4988  205.66  5002.9  207.26  5008.3  205.98  5028.1  207.82
  5196.7  210.71  5312.7  213.87  5484.6  220.58  5600.7  225.06    5650  227.35
#Mann= 8 ,-1 , 0
  4367.5     .08       0  4422.9      .1       0  4896.8     .12       0
  4914.4      .1       0    4982     .07       0    4988      .1       0
  5484.6     .08       0  5600.7      .1       0
Bank Sta=4982,4988
XS Rating Curve= 0 ,0
Exp/Cntr=0.3,0.1

Type RM Length L Ch R = 1 ,6834    ,504,504,504
BEGIN DESCRIPTION:
UNT016 IN SPCR 9.0
END DESCRIPTION:
XS GIS Cut Line= 3
        2233037.     13274216.59      2233438.43     13274216.59
      2234317.37     13273782.54
#Sta/Elev= 30
  4166.6  235.38  4207.9  233.62  4257.3  231.44  4287.3  228.46  4317.3  229.11
  4387.3  226.72  4547.3  219.73  4603.8  218.54  4693.6  215.03  4755.3  211.52
  4783.4  211.29  4867.6  207.56    4890  205.71  4957.3  204.52  4968.7  202.54
  4985.4  203.66    4991  202.32  4999.2  202.15    5002  201.65  5005.2  202.15
  5013.4   204.6  5097.6  206.88  5113.7  208.02    5120  209.39    5136  209.37
  5158.3  210.91  5170.5  210.48  5180.6  212.25  5247.6  215.65  5548.3  228.08
#Mann= 4 ,-1 , 0
  4166.6     .08       0  4207.9      .1       0  4999.2     .07       0
  5005.2      .1       0
Bank Sta=4999.2,5005.2
XS Rating Curve= 0 ,0
Exp/Cntr=0.3,0.1

Type RM Length L Ch R = 1 ,6330    ,472,472,472
BEGIN DESCRIPTION:
UNT016 IN SPCR 8.0
END DESCRIPTION:
XS GIS Cut Line= 3
      2233180.52     13274957.74      2233615.65     13274716.59
      2234437.74     13274196.84
#Sta/Elev= 30
  3992.3  228.35  4240.6  219.34  4270.9  218.83  4276.6  220.26  4300.9  217.55
  4352.2  215.75  4433.5   214.9  4484.1  216.11  4519.6  216.66  4534.9  215.41
  4540.8   216.6  4550.1   214.1  4571.3  212.23  4622.4  212.31  4811.3   204.7
  4984.2  202.37  4990.1  202.06  4996.5  199.07  4999.2  198.57  5002.5  199.07
  5020.7  203.09    5063  204.89  5099.5  208.86    5130   208.8  5266.5  213.82
  5308.9  216.81  5381.8  219.33  5412.4  221.91  5433.6  220.91  5462.4  223.17
#Mann= 5 ,-1 , 0
  3992.3      .1       0  4300.9     .05       0  4484.1      .1       0
  4996.5     .07       0  5002.5      .1       0
Bank Sta=4996.5,5002.5
XS Rating Curve= 0 ,0
Exp/Cntr=0.3,0.1

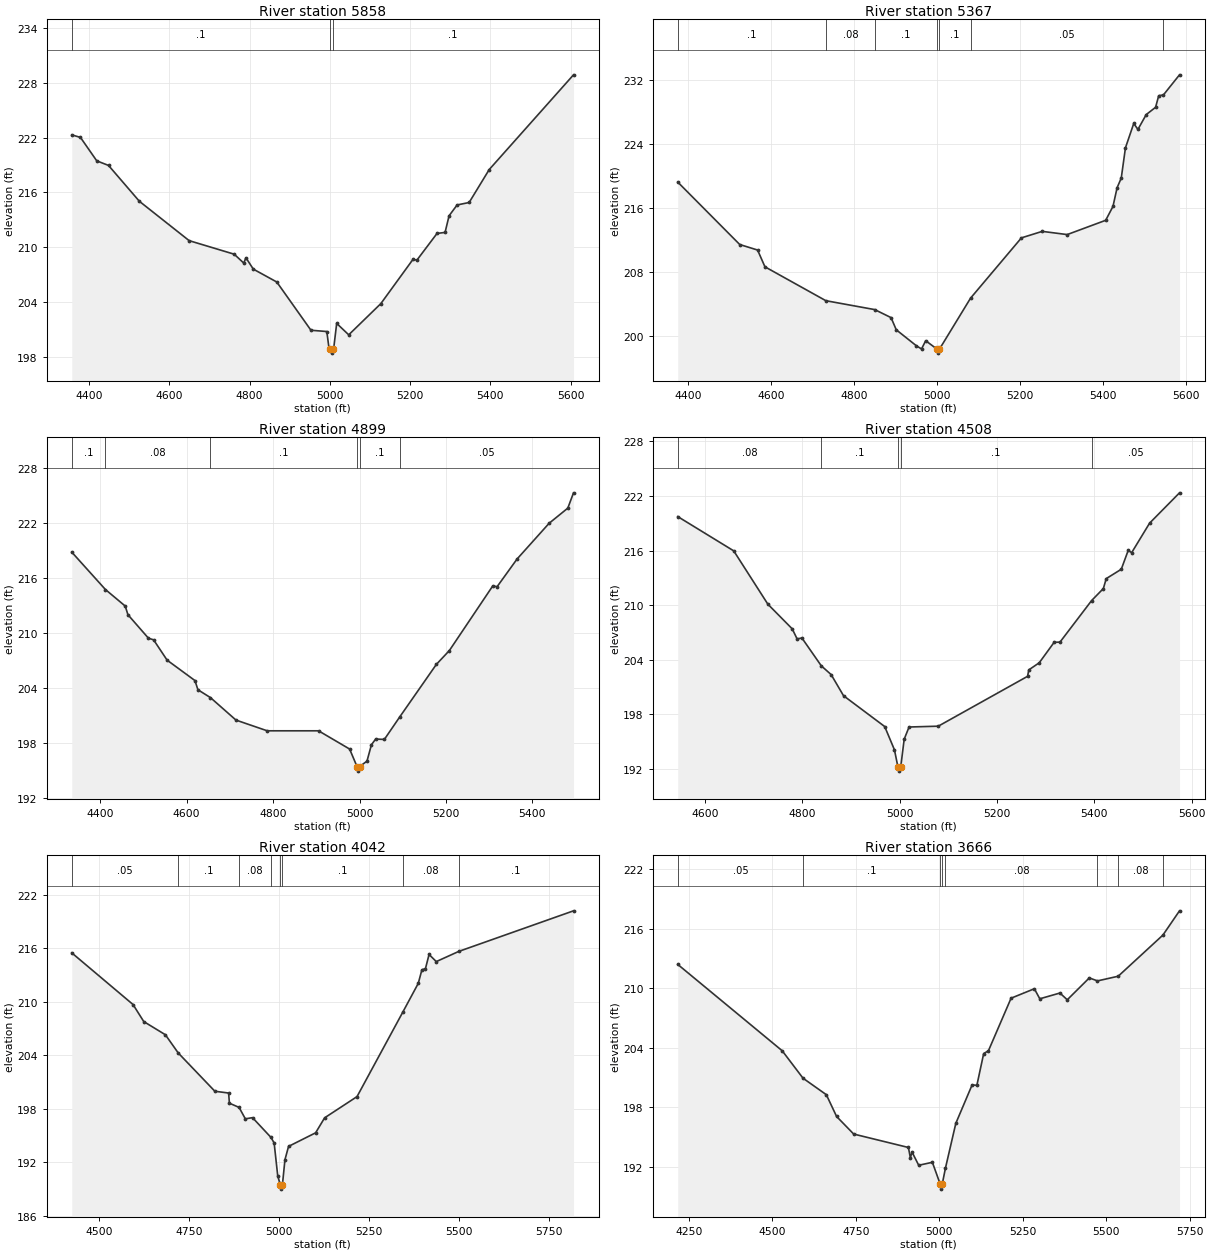
Type RM Length L Ch R = 1 ,5858    ,491,491,491
BEGIN DESCRIPTION:
UNT016 IN SPCR 7.0
END DESCRIPTION:
XS GIS Cut Line= 3
      2233537.69     13275146.87      2234137.72     13274896.85
      2234737.69     13274896.85
#Sta/Elev= 30
    4357  222.29  4378.7  222.01  4419.3  219.45  4448.6  218.95  4525.5  215.03
  4649.5  210.73  4761.7  209.25  4785.5  208.28  4790.9  208.86  4809.3  207.62
  4867.8  206.21  4952.9  200.94  4992.4   200.8  4997.8     199  5001.3  198.94
  5004.1  198.44  5007.3  198.94  5009.5  198.94    5017  201.69    5047  200.44
    5127  203.85    5207  208.68    5217  208.61    5267  211.52    5287  211.63
    5297  213.45    5317  214.63    5347   214.9    5397   218.5    5607  228.85
#Mann= 3 ,-1 , 0
    4357      .1       0  5001.3     .07       0  5007.3      .1       0
Bank Sta=5001.3,5007.3
XS Rating Curve= 0 ,0
Exp/Cntr=0.3,0.1

Type RM Length L Ch R = 1 ,5367    ,468,468,468
BEGIN DESCRIPTION:
UNT016 IN SPCR 6.0
END DESCRIPTION:
XS GIS Cut Line= 3
      2233587.77     13275246.86      2234187.72     13275346.85
      2234787.71     13275396.85
#Sta/Elev= 30
  4374.1  219.21  4523.6  211.42  4566.7  210.73  4584.4  208.64  4731.4  204.41
  4849.3   203.3  4888.6   202.3  4901.2  200.78  4949.4   198.8  4962.1  198.39
  4972.2  199.42  4999.4  198.37  5002.2  197.87  5005.4  198.37  5080.4  204.73
  5203.1  212.25  5253.3  213.06  5313.5  212.66  5406.3  214.44  5423.9  216.17
  5433.9  218.51  5443.9  219.71    5454  223.48    5474  226.52  5484.1  225.78
  5504.1  227.63  5526.7  228.54  5534.2  229.98  5545.7  230.09  5584.4  232.59
#Mann= 7 ,-1 , 0
  4374.1      .1       0  4731.4     .08       0  4849.3      .1       0
  4999.4     .07       0  5005.4      .1       0  5080.4     .05       0
  5545.7      .1       0
Bank Sta=4999.4,5005.4
XS Rating Curve= 0 ,0
Exp/Cntr=0.3,0.1

Type RM Length L Ch R = 1 ,4899    ,391,391,391
BEGIN DESCRIPTION:
UNT016 IN SPCR 5.0
END DESCRIPTION:
XS GIS Cut Line= 3
      2233442.64     13275623.59      2233799.14     13275765.14
      2234573.89     13275833.19
#Sta/Elev= 30
    4334  218.86  4411.9  214.78  4457.8  212.97    4464  212.03  4511.6  209.46
  4523.4  209.29  4554.7  207.07  4619.2  204.84    4626  203.84  4655.1  202.98
  4714.1  200.53  4786.4  199.36  4905.2  199.36  4977.1  197.37  4994.2  195.46
    4997  194.96  5000.2  195.46  5017.3  196.05  5027.6  197.84  5037.4  198.46
  5057.5  198.42  5092.6  200.84  5177.9  206.61    5208  208.12  5308.4  215.17
  5318.5  215.09  5364.7  218.11  5438.9  222.01  5482.1  223.66  5495.3  225.33
#Mann= 6 ,-1 , 0
    4334      .1       0  4411.9     .08       0  4655.1      .1       0
  4994.2     .07       0  5000.2      .1       0  5092.6     .05       0
Bank Sta=4994.2,5000.2
XS Rating Curve= 0 ,0
Exp/Cntr=0.3,0.1

Type RM Length L Ch R = 1 ,4508    ,466,466,466
BEGIN DESCRIPTION:
UNT016 IN SPCR 4.0
END DESCRIPTION:
XS GIS Cut Line= 3
      2233552.71     13276179.32      2234270.99     13276163.59
      2234537.73     13276001.46
#Sta/Elev= 30
  4544.5  219.74  4659.5  215.97  4729.6  210.11  4779.6   207.4  4789.6   206.3
  4799.6  206.39  4839.4  203.33  4859.6  202.37    4885  200.05  4969.6  196.66
  4989.6   194.1  4996.6  192.26  4999.4  191.76  5002.6  192.26  5009.6  195.27
  5019.6  196.61  5079.6   196.7    5263  202.18  5265.6  202.89    5287  203.67
  5317.6  205.92  5329.6  205.94  5394.6  210.51  5418.7  211.83  5424.6  212.92
  5455.5  213.95  5469.8  216.03  5476.8  215.77  5513.7  219.02  5575.1  222.35
#Mann= 5 ,-1 , 0
  4544.5     .08       0  4839.4      .1       0  4996.6     .07       0
  5002.6      .1       0  5394.6     .05       0
Bank Sta=4996.6,5002.6
XS Rating Curve= 0 ,0
Exp/Cntr=0.3,0.1

Type RM Length L Ch R = 1 ,4042    ,376,376,376
BEGIN DESCRIPTION:
UNT016 IN SPCR 3.0
END DESCRIPTION:
XS GIS Cut Line= 4
      2233637.74     13276396.86      2234024.58     13276603.98
      2234611.77     13276598.74      2234831.96     13276305.15
#Sta/Elev= 30
  4424.5  215.47  4594.6  209.68  4624.4  207.77  4684.5  206.29  4720.1  204.25
  4821.8  199.96    4860  199.76  4862.2  198.62    4889  198.15  4906.4  196.87
  4926.4     197  4977.7  194.78  4986.4  194.16  4996.4  190.45  5003.4  189.49
  5006.2  188.99  5009.4  189.49  5016.4  192.29  5026.4  193.78  5101.5   195.3
  5126.5  196.98  5216.5  199.36    5344  208.86  5386.5  212.05  5396.5  213.56
  5406.5  213.71  5416.5  215.29  5436.5  214.49  5498.8  215.63  5817.5  220.18
#Mann= 8 ,-1 , 0
  4424.5     .05       0  4720.1      .1       0    4889     .08       0
  4977.7      .1       0  5003.4     .07       0  5009.4      .1       0
    5344     .08       0  5498.8      .1       0
Bank Sta=5003.4,5009.4
XS Rating Curve= 0 ,0
Exp/Cntr=0.3,0.1

Type RM Length L Ch R = 1 ,3666    ,531,531,531
BEGIN DESCRIPTION:
UNT016 IN SPCR 2.0
END DESCRIPTION:
XS GIS Cut Line= 4
      2233656.52     13276522.77      2233848.19     13276878.72
      2234436.88     13277008.78      2234873.88     13276776.62
#Sta/Elev= 30
  4217.2  212.39  4529.9   203.7  4592.2  200.94    4662  199.28  4692.7  197.09
  4743.9  195.32  4907.7  193.97  4913.5  192.94  4918.6  193.51  4938.5  192.18
  4979.4  192.48  5002.9  190.28  5005.7  189.78  5008.9  190.28  5018.6   191.9
  5049.6   196.4  5098.4  200.27  5112.6  200.22    5133  203.42  5147.2   203.7
    5215  208.99  5284.7  209.94    5301  208.93  5361.2  209.51  5383.2  208.83
  5449.2  211.03  5473.7  210.73  5535.7   211.2  5669.5  215.34  5719.2  217.78
#Mann= 8 ,-1 , 0
  4217.2     .05       0  4592.2      .1       0  5002.9     .07       0
  5008.9      .1       0  5018.6     .08       0  5473.7      .1       0
  5535.7     .08       0  5669.5     .05       0
Bank Sta=5002.9,5008.9
XS Rating Curve= 0 ,0
Exp/Cntr=0.3,0.1

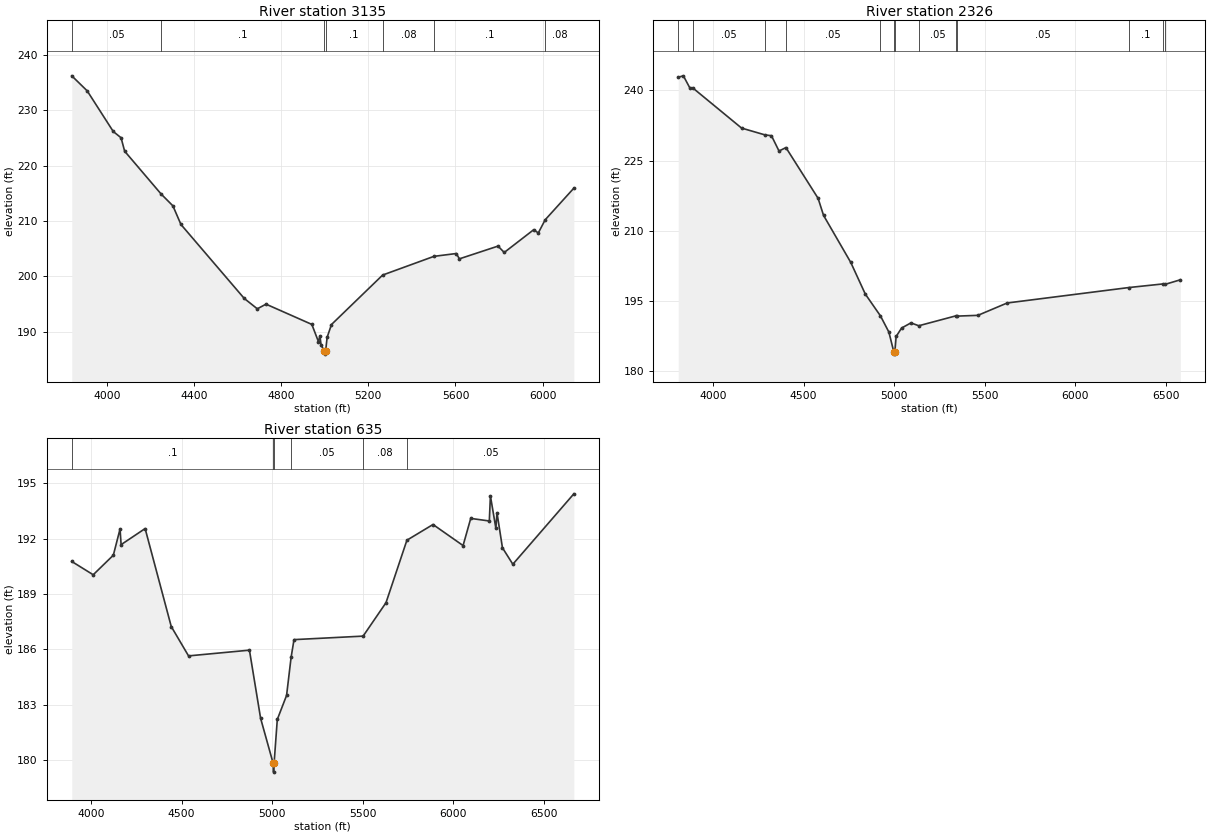
Type RM Length L Ch R = 1 ,3135    ,809,809,809
BEGIN DESCRIPTION:
Mapping XS 5ef7407e
END DESCRIPTION:
XS GIS Cut Line= 4
      2232848.47     13277170.13      2233262.04     13277382.83
      2234360.88     13277430.09      2234928.05     13276957.45
#Sta/Elev= 30
  3839.7  236.26  3910.5  233.54    4030   226.2  4065.8  225.07  4082.3  222.64
  4249.4  214.91  4303.7  212.76  4340.5   209.4  4630.7  196.04  4690.8  194.16
  4730.8     195    4941  191.34  4971.1  188.24  4978.2  189.27  4983.2  187.67
  4998.1  186.47  5000.8  185.97  5004.1  186.47  5011.1     189  5031.1  191.32
  5265.8  200.26  5501.3  203.64  5603.6  204.15  5617.9  203.19    5795  205.49
  5823.6  204.34    5959  208.46  5979.8  207.86  6011.3  210.24  6142.9  215.96
#Mann= 7 ,-1 , 0
  3839.7     .05       0  4249.4      .1       0  4998.1     .07       0
  5004.1      .1       0  5265.8     .08       0  5501.3      .1       0
  6011.3     .08       0
Bank Sta=4998.1,5004.1
XS Rating Curve= 0 ,0
Exp/Cntr=0.3,0.1

Type RM Length L Ch R = 1 ,2326    ,1691,1691,1691
BEGIN DESCRIPTION:
Mapping XS 3cbf2d4e
END DESCRIPTION:
XS GIS Cut Line= 4
      2232725.55     13277619.49      2233090.16     13278114.32
      2233940.85     13278175.08      2235077.96     13277532.75
#Sta/Elev= 30
  3807.8   242.8  3836.2   243.1  3871.7  240.53  3886.8  240.56  4157.8  231.94
  4286.6  230.49  4322.8  230.31  4364.5  227.04  4402.7  227.78  4580.4  216.94
  4610.5   213.3  4760.9  203.25  4841.1   196.5  4924.8  191.84  4971.4  188.38
  4998.5  184.17  5001.2  183.67  5004.5  184.17  5011.5  187.44  5041.6  189.24
  5093.2  190.34  5136.6  189.73    5344  191.87  5348.5  191.79    5463  191.95
  5624.8  194.59  6297.2  197.89  6487.9  198.67  6495.5  198.55  6581.3  199.54
#Mann= 13 ,-1 , 0
  3807.8     .08       0  3886.8     .05       0  4286.6     .08       0
  4402.7     .05       0  4924.8      .1       0  4998.5     .07       0
  5004.5      .1       0  5136.6     .05       0    5344     .08       0
  5348.5     .05       0  6297.2      .1       0  6487.9     .05       0
  6495.5      .1       0
Bank Sta=4998.5,5004.5
XS Rating Curve= 0 ,0
Exp/Cntr=0.3,0.1

Type RM Length L Ch R = 1 ,635     ,0,0,0
BEGIN DESCRIPTION:
UNT016 IN SPCR 1.0
END DESCRIPTION:
XS GIS Cut Line= 4
      2233498.12     13279043.13       2234140.5     13279425.08
      2234800.23     13279277.51      2235537.16     13278150.43
#Sta/Elev= 30
  3894.2  190.76  4012.5  190.04  4123.6   191.1  4160.6  192.52  4166.4  191.67
  4298.9  192.54    4443  187.24  4538.4  185.65  4874.4  185.96  4936.1  182.27
  5004.6  179.86  5007.4  179.36  5010.6  179.86  5028.1  182.21  5079.3  183.51
  5104.3  185.57  5120.3  186.53  5501.6  186.72  5627.9  188.53  5743.2  191.91
  5887.2  192.76  6053.1  191.62  6095.3  193.09  6197.9  192.95  6203.9  194.31
  6234.1  192.55  6240.1   193.4  6270.3   191.5  6327.6  190.61  6664.2  194.42
#Mann= 6 ,-1 , 0
  3894.2      .1       0  5004.6     .07       0  5010.6      .1       0
  5104.3     .05       0  5501.6     .08       0  5743.2     .05       0
Bank Sta=5004.6,5010.6
XS Rating Curve= 0 ,0
Exp/Cntr=0.3,0.1

Chan Stop Cuts=-1
Use User Specified Reach Order=0
Composite Channel Slope=5