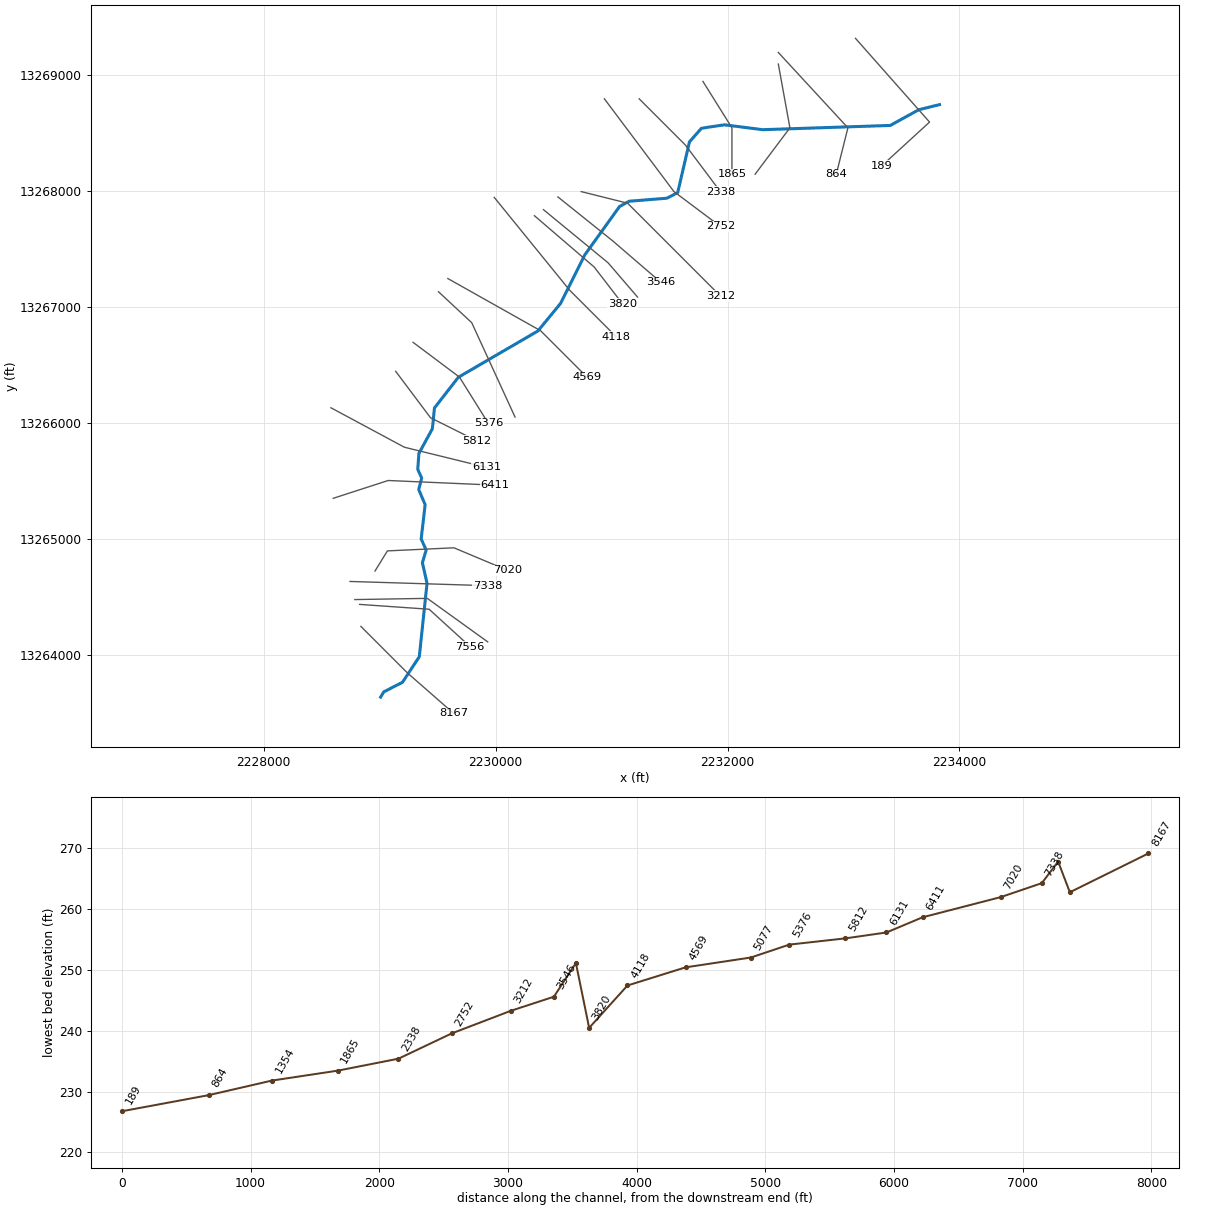
--- UNT017 IN SPCR.prj (project) ---

Proj Title=UNT017 IN SPCR Base Level Engineering
Current Plan=p01
Default Exp/Contr=0.3,0.1
English Units
Geom File=g01
Flow File=f01
Plan File=p01
BEGIN DESCRIPTION:
UNT017 IN SPCR
END DESCRIPTION:

--- UNT017 IN SPCR.p01 (plan) ---

Plan Title=Multiple Run
Short Identifier=Multiple
Geom File=g01
Flow File=f01
Subcritical Flow
K Sum by GR= 0
Std Step Tol= 0.01
Critical Tol= 0.01
Num of Std Step Trials= 20
Max Error Tol= 0.3
Flow Tol Ratio= 0.001
Split Flow NTrial= 30
Split Flow Tol= 0.02
Split Flow Ratio= 0.02
Log Output Level= 0
Friction Slope Method= 1
Unsteady Friction Slope Method= 2
Unsteady Bridges Friction Slope Method= 1
Parabolic Critical Depth
Global Vel Dist=  1 , 1 , 1
Global Log Level= 0
CheckData=True
Encroach Param= -1, 0, 0, 0
BEGIN DESCRIPTION:
Multiple Run
END DESCRIPTION:

--- UNT017 IN SPCR.f01 (steady flow) ---

Flow Title=Multiple
Number of Profiles=7
Profile Names=10-year,25-year,50-year,1pct_min,100-year,1pct_plu,500-year
River Rch & RM= UNT017 IN SPCR,Reach-1,8167
     396     569     717     664     898    1215    1433
Boundary for River Rch & Prof#=UNT017 IN SPCR,Reach-1,1
Up Type=0
Dn Type=3
Dn Slope=0.005
Boundary for River Rch & Prof#=UNT017 IN SPCR,Reach-1,2
Up Type=0
Dn Type=3
Dn Slope=0.005
Boundary for River Rch & Prof#=UNT017 IN SPCR,Reach-1,3
Up Type=0
Dn Type=3
Dn Slope=0.005
Boundary for River Rch & Prof#=UNT017 IN SPCR,Reach-1,4
Up Type=0
Dn Type=3
Dn Slope=0.005
Boundary for River Rch & Prof#=UNT017 IN SPCR,Reach-1,5
Up Type=0
Dn Type=3
Dn Slope=0.005
Boundary for River Rch & Prof#=UNT017 IN SPCR,Reach-1,6
Up Type=0
Dn Type=3
Dn Slope=0.005
Boundary for River Rch & Prof#=UNT017 IN SPCR,Reach-1,7
Up Type=0
Dn Type=3
Dn Slope=0.005

--- UNT017 IN SPCR.g01 (geometry) ---

Geom Title=Existing Conditions

River Reach=UNT017 IN SPCR,Reach-1
Reach XY= 30
      2229007.72     13263636.86      2229034.99     13263682.24
      2229196.67     13263765.48      2229341.36     13263985.13
      2229408.03     13264619.50      2229368.00     13264795.75
      2229400.73     13264906.65      2229357.54     13265000.41
      2229391.74     13265296.81      2229336.58     13265426.57
      2229362.02     13265526.74      2229328.22     13265600.84
      2229337.69     13265737.99      2229453.69     13265950.78
      2229472.26     13266131.05      2229678.71     13266395.95
      2230364.42     13266794.82      2230560.60     13267033.54
      2230768.93     13267451.50      2231068.85     13267868.61
      2231151.75     13267913.74      2231476.37     13267939.80
      2231569.96     13267988.16      2231671.19     13268425.44
      2231774.89     13268543.10      2231972.78     13268572.90
      2232302.67     13268530.79      2233403.05     13268567.40
      2233649.29     13268703.04      2233827.72     13268746.86

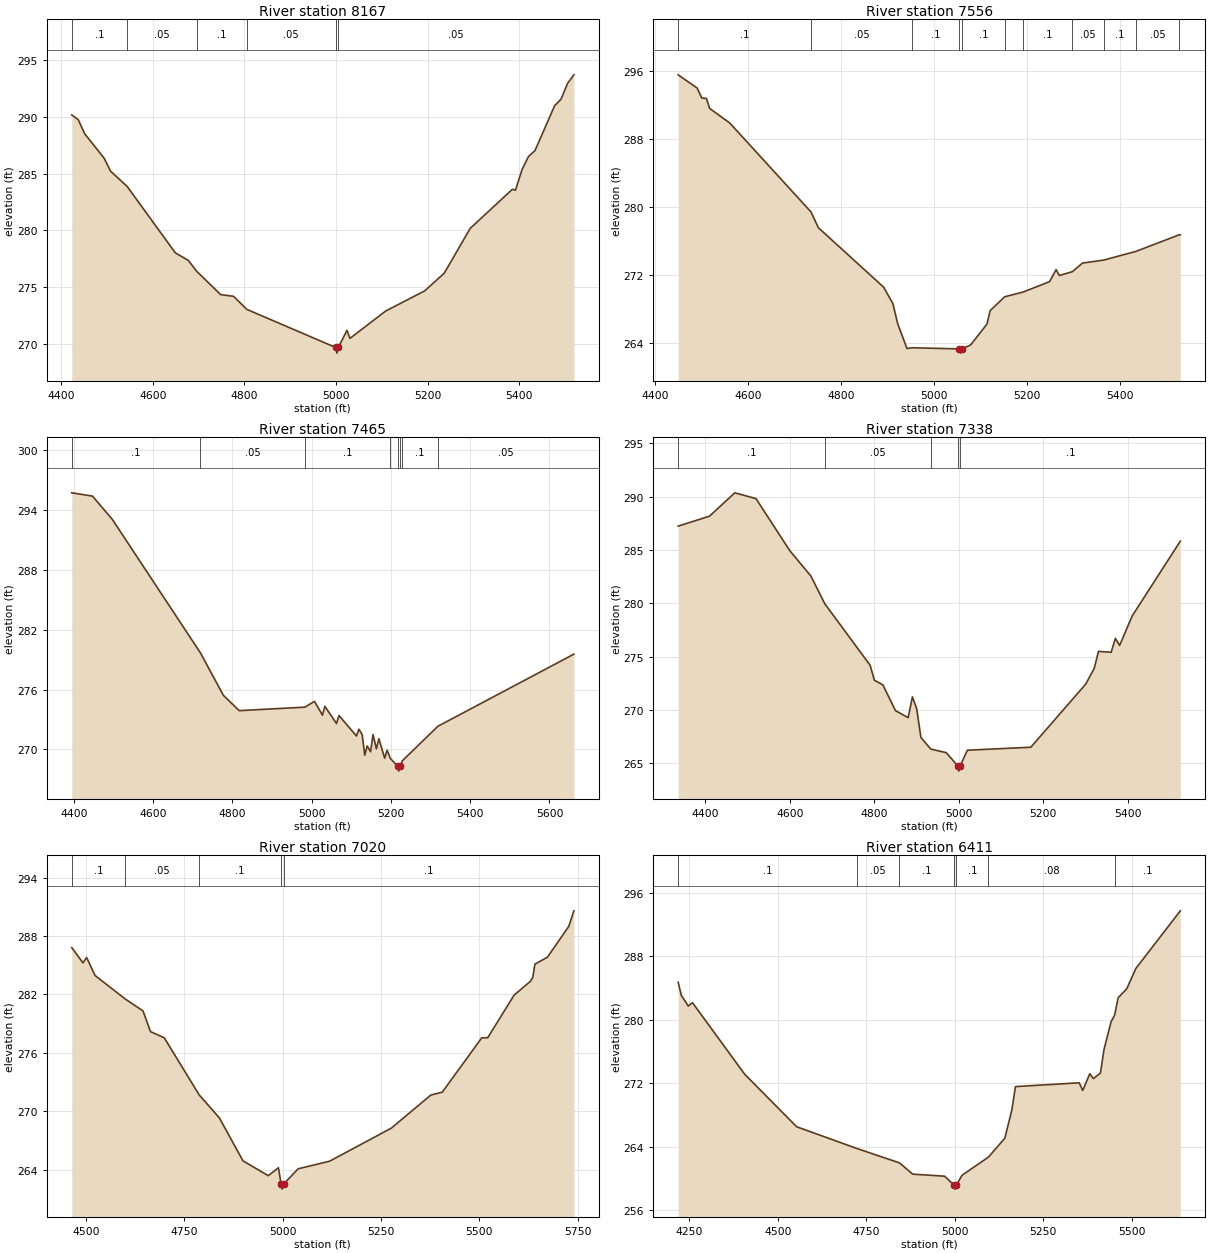
Type RM Length L Ch R = 1,8167,611,611,611
BEGIN DESCRIPTION:
UNT017 IN SPCR 18.0
END DESCRIPTION:
XS GIS Cut Line= 3
      2228837.72     13264246.86      2229237.72     13263846.85
      2229637.72     13263496.85
#Sta/Elev= 30
  4422.6  290.17  4436.7  289.76  4450.9  288.51  4493.3  286.36  4507.5  285.21
  4543.6  283.87  4648.9  278.01  4677.2  277.35  4695.3  276.40  4747.9  274.33
  4776.2  274.18  4805.0  273.03  4999.1  269.67  5001.8  269.17  5005.1  269.67
  5023.9  271.18  5030.5  270.47  5108.4  272.88  5193.8  274.66  5236.5  276.22
  5293.4  280.18  5385.5  283.62  5392.1  283.54  5406.4  285.34  5420.6  286.51
  5434.8  287.03  5477.6  290.98  5491.8  291.57  5506.0  292.96  5519.8  293.71
#Mann=6,-1,0
  4422.6     0.1       0  4543.6    0.05       0  4695.3     0.1       0
  4805.0    0.05       0  4999.1    0.03       0  5005.1    0.05       0
Bank Sta=4999.1,5005.1
Exp/Cntr=0.3,0.1

Type RM Length L Ch R = 1,7556,91,91,91
BEGIN DESCRIPTION:
Mapping XS adde3cb5
END DESCRIPTION:
XS GIS Cut Line= 3
      2228827.03     13264436.66      2229426.04     13264394.99
      2229780.18     13264072.10
#Sta/Elev= 30
  4449.6  295.57  4490.4  294.01  4500.4  292.83  4510.4  292.79  4517.1  291.62
  4560.6  289.89  4735.3  279.41  4751.0  277.56  4891.4  270.55  4911.4  268.60
  4921.4  266.28  4941.5  263.33  4953.4  263.41  5053.9  263.28  5056.7  262.78
  5059.9  263.28  5078.5  263.75  5113.7  266.21  5120.4  267.79  5151.7  269.42
  5191.5  269.98  5248.1  271.20  5262.3  272.62  5269.1  271.93  5297.0  272.37
  5319.0  273.39  5364.2  273.74  5433.6  274.76  5526.9  276.72  5529.3  276.72
#Mann=11,-1,0
  4449.6     0.1       0  4735.3    0.05       0  4953.4     0.1       0
  5053.9    0.07       0  5059.9     0.1       0  5151.7    0.05       0
  5191.5     0.1       0  5297.0    0.05       0  5364.2     0.1       0
  5433.6    0.05       0  5526.9     0.1       0
Bank Sta=5053.9,5059.9
Exp/Cntr=0.3,0.1

Type RM Length L Ch R = 1,7465,127,127,127
BEGIN DESCRIPTION:
Mapping XS 87dd5b61
END DESCRIPTION:
XS GIS Cut Line= 3
      2228785.40     13264478.32      2229410.41     13264488.74
      2229931.25     13264113.73
#Sta/Elev= 30
  4394.7  295.71  4447.0  295.38  4497.0  293.05  4719.4  279.67  4777.1  275.43
  4817.1  273.89  4982.9  274.24  5007.1  274.82  5027.1  273.44  5033.3  274.32
  5062.7  272.60  5068.9  273.40  5113.0  271.35  5119.2  272.03  5127.4  271.49
  5133.9  269.42  5140.1  270.35  5148.6  269.77  5154.8  271.50  5163.3  270.06
  5169.5  271.08  5184.2  269.12  5190.4  269.93  5198.4  269.11  5216.8  268.33
  5219.6  267.83  5222.8  268.33  5229.1  268.88  5318.3  272.32  5661.6  279.55
#Mann=8,-1,0
  4394.7     0.1       0  4719.4    0.05       0  4982.9     0.1       0
  5198.4    0.05       0  5216.8    0.07       0  5222.8    0.05       0
  5229.1     0.1       0  5318.3    0.05       0
Bank Sta=5216.8,5222.8
Exp/Cntr=0.3,0.1

Type RM Length L Ch R = 1,7338,318,318,318
BEGIN DESCRIPTION:
Mapping XS 7f2a1258
END DESCRIPTION:
XS GIS Cut Line= 2
      2228743.74     13264634.57      2229931.28     13264598.11
#Sta/Elev= 30
  4336.1  287.24  4410.1  288.17  4470.1  290.36  4520.2  289.82  4600.2  284.94
  4650.2  282.56  4683.1  279.96  4790.3  274.20  4800.3  272.80  4820.3  272.37
  4850.3  269.95  4880.3  269.29  4890.3  271.24  4900.4  270.14  4910.4  267.44
  4933.6  266.35  4970.4  266.01  4997.4  264.78  5000.1  264.28  5003.4  264.78
  5020.4  266.24  5170.5  266.52  5300.5  272.44  5320.5  273.91  5330.6  275.50
  5360.6  275.42  5370.6  276.72  5380.6  276.06  5410.6  278.84  5524.2  285.83
#Mann=5,-1,0
  4336.1     0.1       0  4683.1    0.05       0  4933.6     0.1       0
  4997.4    0.07       0  5003.4     0.1       0
Bank Sta=4997.4,5003.4
Exp/Cntr=0.3,0.1

Type RM Length L Ch R = 1,7020,609,609,609
BEGIN DESCRIPTION:
UNT017 IN SPCR 15.0
END DESCRIPTION:
XS GIS Cut Line= 4
      2228959.60     13264724.70      2229066.33     13264898.14
      2229640.09     13264924.82      2230099.82     13264731.60
#Sta/Elev= 30
  4463.8  286.82  4492.3  285.25  4501.6  285.80  4523.1  283.95  4599.7  281.54
  4644.9  280.31  4664.0  278.18  4698.9  277.55  4787.9  271.67  4839.0  269.32
  4899.1  264.90  4963.4  263.37  4989.2  264.19  4996.2  262.49  4998.9  261.99
  5002.2  262.49  5039.2  264.08  5119.3  264.86  5276.3  268.26  5376.7  271.66
  5405.9  271.96  5506.3  277.55  5521.3  277.55  5588.4  281.93  5629.8  283.35
  5635.9  283.74  5641.3  285.12  5673.1  285.83  5727.4  289.00  5740.5  290.60
#Mann=5,-1,0
  4463.8     0.1       0  4599.7    0.05       0  4787.9     0.1       0
  4996.2    0.07       0  5002.2     0.1       0
Bank Sta=4996.2,5002.2
Exp/Cntr=0.3,0.1

Type RM Length L Ch R = 1,6411,280,280,280
BEGIN DESCRIPTION:
UNT017 IN SPCR 14.0
END DESCRIPTION:
XS GIS Cut Line= 3
      2228599.28     13265351.80      2229073.00     13265505.25
      2229993.18     13265465.25
#Sta/Elev= 30
  4218.6  284.76  4227.5  283.10  4247.2  281.75  4259.0  282.18  4406.2  273.17
  4553.3  266.53  4722.7  263.80  4844.0  261.97  4881.4  260.55  4971.5  260.29
  4998.5  259.16  5001.3  258.66  5004.5  259.16  5020.8  260.41  5095.4  262.70
  5141.7  265.08  5161.7  268.67  5171.7  271.59  5351.9  272.07  5361.9  271.11
  5381.9  273.22  5391.9  272.60  5411.9  273.30  5421.9  276.26  5442.0  279.77
  5452.0  280.61  5462.0  282.80  5486.2  283.92  5512.0  286.49  5637.6  293.76
#Mann=7,-1,0
  4218.6     0.1       0  4722.7    0.05       0  4844.0     0.1       0
  4998.5    0.07       0  5004.5     0.1       0  5095.4    0.08       0
  5452.0     0.1       0
Bank Sta=4998.5,5004.5
Exp/Cntr=0.3,0.1

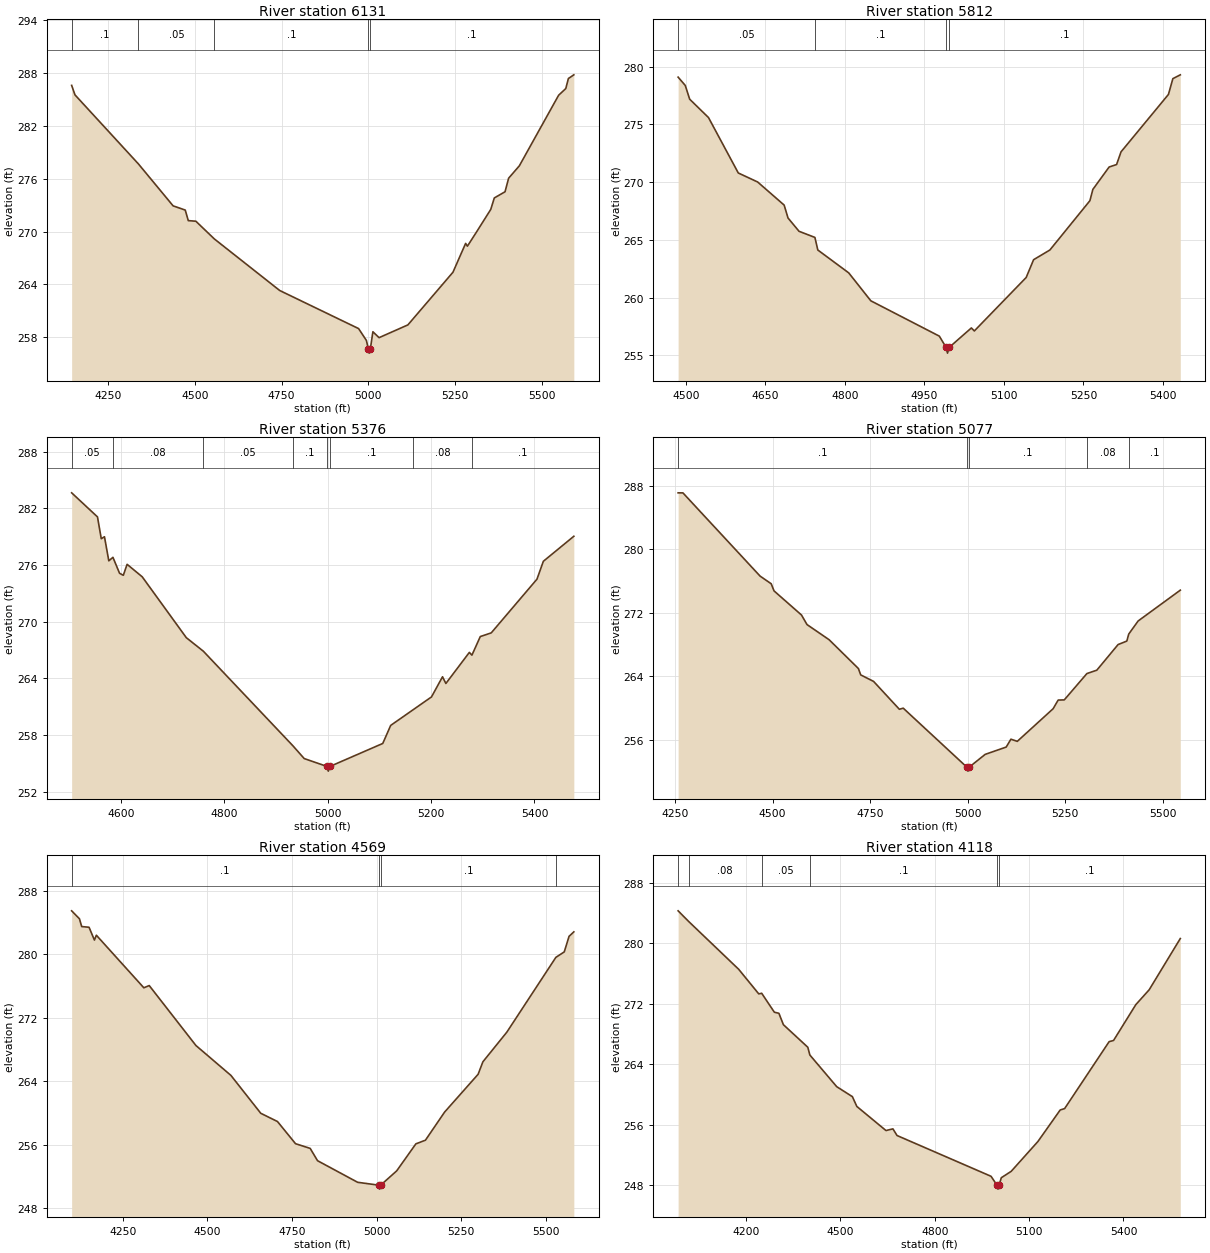
Type RM Length L Ch R = 1,6131,319,319,319
BEGIN DESCRIPTION:
Mapping XS 0d7f6529
END DESCRIPTION:
XS GIS Cut Line= 3
      2228579.29     13266132.39      2229213.11     13265792.13
      2229920.27     13265618.68
#Sta/Elev= 30
  4144.8  286.62  4154.4  285.54  4337.2  277.69  4437.2  272.92  4472.2  272.44
  4481.0  271.24  4502.9  271.17  4556.0  269.16  4744.6  263.29  4971.9  258.96
  4994.4  257.61  4999.8  256.67  5002.5  256.17  5005.8  256.67  5013.1  258.60
  5030.9  257.93  5114.0  259.38  5243.9  265.37  5280.4  268.65  5285.5  268.33
  5311.7  269.94  5352.9  272.52  5363.1  273.82  5394.0  274.52  5404.3  276.06
  5435.2  277.47  5548.5  285.50  5569.1  286.26  5576.6  287.40  5592.3  287.82
#Mann=5,-1,0
  4144.8     0.1       0  4337.2    0.05       0  4556.0     0.1       0
  4999.8    0.07       0  5005.8     0.1       0
Bank Sta=4999.8,5005.8
Exp/Cntr=0.3,0.1

Type RM Length L Ch R = 1,5812,436,436,436
BEGIN DESCRIPTION:
UNT017 IN SPCR 13.0
END DESCRIPTION:
XS GIS Cut Line= 3
      2229137.74     13266446.83      2229437.72     13266046.85
      2229837.73     13265846.85
#Sta/Elev= 30
  4485.5  279.10  4499.0  278.38  4507.3  277.19  4542.8  275.60  4599.0  270.80
  4635.5  270.02  4685.5  268.02  4692.8  266.90  4713.6  265.75  4743.5  265.22
  4749.0  264.13  4807.3  262.15  4849.0  259.73  4978.2  256.67  4990.9  255.70
  4993.6  255.20  4996.9  255.70  5038.6  257.38  5044.2  257.12  5142.0  261.75
  5156.0  263.29  5186.7  264.13  5262.2  268.40  5267.8  269.38  5298.5  271.32
  5312.5  271.53  5320.9  272.63  5410.3  277.60  5418.7  278.97  5432.7  279.30
#Mann=4,-1,0
  4485.5    0.05       0  4743.5     0.1       0  4990.9    0.07       0
  4996.9     0.1       0
Bank Sta=4990.9,4996.9
Exp/Cntr=0.3,0.1

Type RM Length L Ch R = 1,5376,299,299,299
BEGIN DESCRIPTION:
UNT017 IN SPCR 12.0
END DESCRIPTION:
XS GIS Cut Line= 3
      2229287.72     13266696.85      2229687.72     13266396.85
      2229937.72     13265996.85
#Sta/Elev= 30
  4504.5  283.64  4554.5  281.09  4561.8  278.78  4568.0  278.99  4576.4  276.44
  4584.4  276.81  4597.2  275.12  4604.5  274.91  4611.8  276.07  4641.0  274.75
  4726.4  268.30  4759.3  266.87  4932.5  256.86  4954.5  255.50  4998.4  254.67
  5001.1  254.17  5004.4  254.67  5106.5  257.10  5121.8  259.01  5164.7  260.65
  5200.8  262.03  5222.1  264.16  5228.6  263.45  5274.0  266.74  5279.0  266.45
  5295.2  268.42  5316.4  268.81  5404.9  274.50  5417.2  276.39  5476.2  279.04
#Mann=8,-1,0
  4504.5    0.05       0  4584.4    0.08       0  4759.3    0.05       0
  4932.5     0.1       0  4998.4    0.07       0  5004.4     0.1       0
  5164.7    0.08       0  5279.0     0.1       0
Bank Sta=4998.4,5004.4
Exp/Cntr=0.3,0.1

Type RM Length L Ch R = 1,5077,508,508,508
BEGIN DESCRIPTION:
UNT017 IN SPCR 11.0
END DESCRIPTION:
XS GIS Cut Line= 3
      2229506.69     13267133.10      2229793.54     13266866.27
      2230167.17     13266052.28
#Sta/Elev= 30
  4257.8  287.10  4270.2  287.09  4468.0  276.61  4496.4  275.65  4503.7  274.75
  4574.1  271.71  4588.2  270.51  4644.9  268.60  4720.0  264.97  4725.9  264.17
  4758.9  263.35  4825.0  259.84  4834.9  259.98  4998.0  252.55  5000.8  252.05
  5004.0  252.55  5045.0  254.16  5098.8  255.08  5111.0  256.07  5127.3  255.80
  5219.2  259.91  5232.1  261.00  5247.7  261.02  5305.8  264.34  5331.1  264.76
  5385.7  267.99  5408.1  268.43  5413.0  269.31  5437.1  270.96  5545.2  274.84
#Mann=5,-1,0
  4257.8     0.1       0  4998.0    0.07       0  5004.0     0.1       0
  5305.8    0.08       0  5413.0     0.1       0
Bank Sta=4998,5004
Exp/Cntr=0.3,0.1

Type RM Length L Ch R = 1,4569,451,451,451
BEGIN DESCRIPTION:
UNT017 IN SPCR 10.0
END DESCRIPTION:
XS GIS Cut Line= 3
      2229587.69     13267246.87      2230387.72     13266796.85
      2230787.72     13266396.86
#Sta/Elev= 30
  4099.1  285.47  4122.1  284.47  4128.8  283.49  4150.5  283.40  4166.4  281.79
  4172.1  282.40  4312.4  275.78  4328.3  276.06  4466.3  268.51  4569.6  264.75
  4657.8  259.98  4707.2  258.94  4760.5  256.15  4803.8  255.56  4825.5  254.01
  4944.0  251.29  5006.1  250.93  5008.8  250.43  5012.1  250.93  5059.4  252.73
  5116.0  256.13  5144.3  256.59  5200.9  260.13  5299.9  264.89  5314.0  266.46
  5384.7  270.19  5529.6  279.61  5554.4  280.30  5568.6  282.26  5582.7  282.82
#Mann=4,-1,0
  4099.1     0.1       0  5006.1    0.07       0  5012.1     0.1       0
  5529.6    0.08       0
Bank Sta=5006.1,5012.1
Exp/Cntr=0.3,0.1

Type RM Length L Ch R = 1,4118,298,298,298
BEGIN DESCRIPTION:
UNT017 IN SPCR 9.0
END DESCRIPTION:
XS GIS Cut Line= 3
      2229987.73     13267946.85      2230637.72     13267146.85
      2231037.76     13266746.82
#Sta/Elev= 30
  3984.1  284.31  4017.9  282.89  4176.6  276.57  4240.5  273.31  4249.8  273.39
  4290.1  270.88  4304.5  270.74  4318.8  269.23  4396.4  266.24  4403.0  265.21
  4488.3  261.02  4538.1  259.70  4552.3  258.40  4644.9  255.21  4667.0  255.43
  4680.1  254.55  4978.9  249.15  4998.2  247.95  5001.0  247.45  5004.2  247.95
  5011.6  248.96  5043.1  249.81  5128.0  253.76  5198.7  257.93  5212.9  258.12
  5354.3  266.98  5368.4  267.14  5439.1  271.88  5481.6  273.85  5580.6  280.64
#Mann=6,-1,0
  3984.1    0.05       0  4017.9    0.08       0  4249.8    0.05       0
  4403.0     0.1       0  4998.2    0.07       0  5004.2     0.1       0
Bank Sta=4998.2,5004.2
Exp/Cntr=0.3,0.1

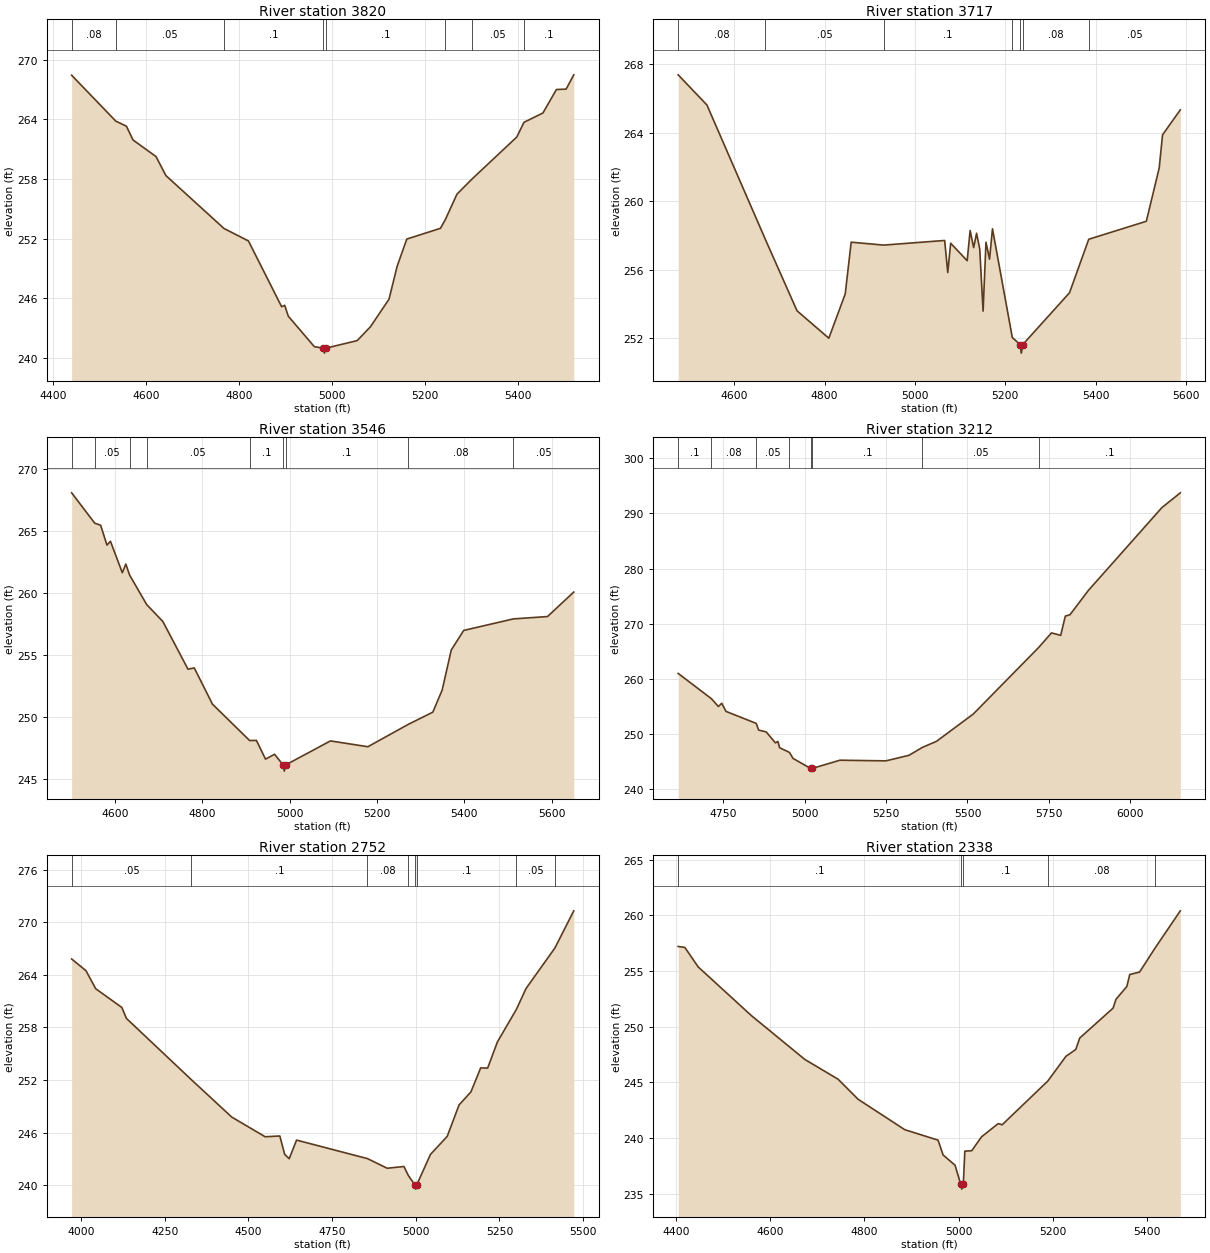
Type RM Length L Ch R = 1,3820,103,103,103
BEGIN DESCRIPTION:
Mapping XS a1ce01ad
END DESCRIPTION:
XS GIS Cut Line= 3
      2230334.04     13267789.07      2230849.65     13267346.38
      2231093.55     13267029.82
#Sta/Elev= 30
  4440.4  268.45  4535.3  263.83  4558.1  263.32  4572.4  261.93  4621.8  260.26
  4643.0  258.35  4767.7  253.03  4820.4  251.77  4891.7  245.15  4898.3  245.29
  4906.0  244.20  4962.0  241.13  4980.9  240.98  4983.7  240.48  4986.9  240.98
  5054.1  241.74  5082.7  243.14  5122.5  245.91  5139.9  249.21  5160.7  251.96
  5233.0  253.04  5243.6  253.92  5268.5  256.48  5301.3  258.02  5397.1  262.23
  5412.6  263.71  5453.3  264.65  5482.3  267.01  5503.1  267.05  5519.6  268.49
#Mann=8,-1,0
  4440.4    0.08       0  4535.3    0.05       0  4767.7     0.1       0
  4980.9    0.07       0  4986.9     0.1       0  5243.6    0.08       0
  5301.3    0.05       0  5412.6     0.1       0
Bank Sta=4980.9,4986.9
Exp/Cntr=0.3,0.1

Type RM Length L Ch R = 1,3717,171,171,171
BEGIN DESCRIPTION:
Mapping XS 29d702bb
END DESCRIPTION:
XS GIS Cut Line= 3
      2230412.13     13267841.19      2230969.44     13267382.84
      2231223.69     13267087.08
#Sta/Elev= 30
  4475.7  267.37  4539.4  265.61  4668.1  257.81  4738.8  253.61  4809.2  252.01
  4845.5  254.59  4858.7  257.61  4930.4  257.44  5065.6  257.71  5072.5  255.84
  5078.9  257.55  5115.5  256.53  5122.0  258.29  5129.8  257.29  5136.3  258.13
  5143.3  257.21  5150.7  253.59  5157.1  257.61  5165.0  256.62  5171.5  258.39
  5215.4  252.05  5232.6  251.64  5235.3  251.14  5238.6  251.64  5342.0  254.66
  5384.6  257.78  5512.1  258.83  5540.6  261.94  5548.0  263.87  5587.3  265.33
#Mann=7,-1,0
  4475.7    0.08       0  4668.1    0.05       0  4930.4     0.1       0
  5215.4    0.08       0  5232.6    0.07       0  5238.6    0.08       0
  5384.6    0.05       0
Bank Sta=5232.6,5238.6
Exp/Cntr=0.3,0.1

Type RM Length L Ch R = 1,3546,334,334,334
BEGIN DESCRIPTION:
UNT017 IN SPCR 8.0
END DESCRIPTION:
XS GIS Cut Line= 3
      2230537.15     13267950.54      2231011.11     13267570.34
      2231422.56     13267216.17
#Sta/Elev= 30
  4500.3  268.07  4553.2  265.62  4566.8  265.45  4581.2  263.85  4589.2  264.16
  4616.4  261.62  4624.4  262.32  4633.1  261.43  4672.2  259.05  4709.3  257.68
  4766.9  253.83  4781.3  253.93  4822.9  251.01  4908.1  248.07  4923.7  248.08
  4944.5  246.57  4965.3  246.96  4984.7  246.10  4987.5  245.60  4990.7  246.10
  5093.3  248.04  5179.1  247.57  5271.3  249.37  5327.8  250.36  5349.2  252.14
  5370.1  255.38  5398.6  256.96  5512.3  257.89  5590.6  258.08  5650.8  260.06
#Mann=9,-1,0
  4500.3     0.1       0  4553.2    0.05       0  4633.1    0.08       0
  4672.2    0.05       0  4908.1     0.1       0  4984.7    0.07       0
  4990.7     0.1       0  5271.3    0.08       0  5512.3    0.05       0
Bank Sta=4984.7,4990.7
Exp/Cntr=0.3,0.1

Type RM Length L Ch R = 1,3212,460,460,460
BEGIN DESCRIPTION:
UNT017 IN SPCR 7.0
END DESCRIPTION:
XS GIS Cut Line= 3
      2230737.70     13267996.86      2231137.72     13267896.85
      2231937.72     13267096.86
#Sta/Elev= 30
  4610.7  261.00  4712.8  256.42  4734.4  255.00  4744.7  255.59  4757.6  254.12
  4850.7  251.94  4858.1  250.73  4881.3  250.40  4909.6  248.42  4917.4  248.67
  4922.5  247.53  4952.7  246.69  4963.8  245.60  5017.5  243.79  5020.2  243.29
  5023.5  243.79  5107.9  245.27  5249.3  245.15  5320.0  246.15  5361.8  247.60
  5404.9  248.69  5518.0  253.64  5719.1  265.71  5758.4  268.34  5786.7  267.90
  5800.9  271.39  5815.0  271.62  5871.6  276.03  6097.8  291.05  6154.4  293.73
#Mann=8,-1,0
  4610.7     0.1       0  4712.8    0.08       0  4850.7    0.05       0
  4952.7     0.1       0  5017.5    0.07       0  5023.5     0.1       0
  5361.8    0.05       0  5719.1     0.1       0
Bank Sta=5017.5,5023.5
Exp/Cntr=0.3,0.1

Type RM Length L Ch R = 1,2752,414,414,414
BEGIN DESCRIPTION:
UNT017 IN SPCR 6.0
END DESCRIPTION:
XS GIS Cut Line= 3
      2230937.73     13268796.84      2231537.72     13267996.85
      2231937.74     13267696.84
#Sta/Elev= 30
  3971.9  265.81  4014.6  264.48  4043.8  262.42  4121.9  260.28  4135.4  259.04
  4328.9  252.07  4450.0  247.79  4550.0  245.54  4593.8  245.63  4608.3  243.53
  4621.9  243.04  4643.8  245.16  4855.6  243.05  4914.6  241.95  4964.6  242.15
  4977.7  241.12  4997.0  240.07  4999.8  239.57  5003.0  240.07  5043.8  243.53
  5093.8  245.58  5129.2  249.17  5164.6  250.65  5193.8  253.39  5214.6  253.37
  5243.8  256.35  5300.4  260.06  5329.2  262.44  5415.5  267.06  5471.9  271.30
#Mann=8,-1,0
  3971.9    0.05       0  4328.9     0.1       0  4855.6    0.08       0
  4977.7     0.1       0  4997.0    0.07       0  5003.0     0.1       0
  5300.4    0.05       0  5415.5     0.1       0
Bank Sta=4997,5003
Exp/Cntr=0.3,0.1

Type RM Length L Ch R = 1,2338,473,473,473
BEGIN DESCRIPTION:
UNT017 IN SPCR 5.0
END DESCRIPTION:
XS GIS Cut Line= 3
      2231237.69     13268796.89      2231637.72     13268396.85
      2231937.70     13267996.88
#Sta/Elev= 30
  4404.8  257.21  4419.0  257.12  4447.3  255.37  4560.4  250.99  4673.6  247.06
  4744.3  245.28  4786.7  243.48  4885.7  240.75  4956.4  239.81  4967.0  238.48
  4992.4  237.56  5004.0  235.91  5006.7  235.41  5010.0  235.91  5013.2  238.82
  5027.8  238.86  5048.7  240.11  5084.1  241.30  5092.4  241.19  5189.3  245.12
  5227.8  247.34  5248.7  247.96  5257.0  248.98  5327.8  251.67  5334.1  252.47
  5357.0  253.61  5363.2  254.69  5384.1  254.91  5417.3  257.09  5470.5  260.41
#Mann=5,-1,0
  4404.8     0.1       0  5004.0    0.07       0  5010.0     0.1       0
  5189.3    0.08       0  5417.3     0.1       0
Bank Sta=5004,5010
Exp/Cntr=0.3,0.1

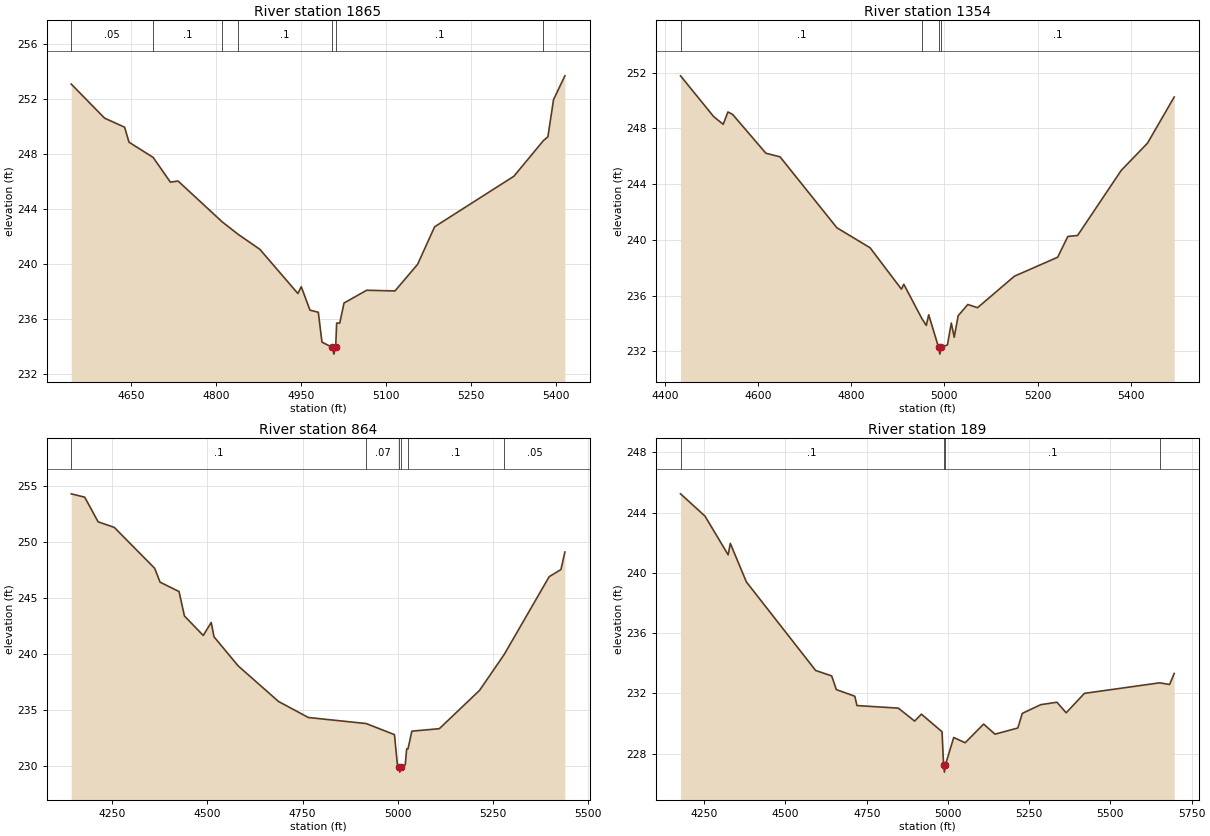
Type RM Length L Ch R = 1,1865,511,511,511
BEGIN DESCRIPTION:
UNT017 IN SPCR 4.0
END DESCRIPTION:
XS GIS Cut Line= 3
      2231787.73     13268946.84      2232037.72     13268546.85
      2232037.72     13268146.83
#Sta/Elev= 30
  4544.5  253.10  4603.4  250.62  4638.8  249.96  4646.5  248.87  4689.2  247.76
  4719.6  245.96  4733.2  246.04  4811.1  243.07  4839.3  242.16  4877.6  241.07
  4944.8  237.85  4950.7  238.35  4966.1  236.64  4980.8  236.49  4987.3  234.31
  5005.5  233.94  5008.3  233.44  5011.5  233.94  5013.2  235.70  5018.7  235.70
  5026.2  237.16  5066.2  238.09  5116.2  238.04  5156.2  239.98  5186.2  242.71
  5326.2  246.39  5378.4  248.99  5386.2  249.26  5396.2  251.97  5416.2  253.70
#Mann=7,-1,0
  4544.5    0.05       0  4689.2     0.1       0  4811.1    0.05       0
  4839.3     0.1       0  5005.5    0.07       0  5011.5     0.1       0
  5378.4    0.08       0
Bank Sta=5005.5,5011.5
Exp/Cntr=0.3,0.1

Type RM Length L Ch R = 1,1354,490,490,490
BEGIN DESCRIPTION:
UNT017 IN SPCR 3.0
END DESCRIPTION:
XS GIS Cut Line= 3
      2232437.71     13269096.90      2232537.72     13268546.85
      2232237.70     13268146.82
#Sta/Elev= 30
  4434.0  251.77  4505.2  248.84  4525.5  248.29  4535.7  249.18  4545.8  249.00
  4617.0  246.22  4647.5  245.96  4769.5  240.87  4840.6  239.44  4907.9  236.47
  4913.0  236.82  4952.1  234.34  4961.3  233.87  4966.4  234.63  4987.5  232.31
  4990.3  231.81  4993.5  232.31  5006.6  232.47  5014.9  234.04  5021.2  233.02
  5029.5  234.56  5050.3  235.37  5071.2  235.14  5150.3  237.40  5243.1  238.76
  5264.9  240.25  5285.8  240.32  5379.5  244.99  5435.8  246.94  5493.1  250.25
#Mann=4,-1,0
  4434.0     0.1       0  4952.1    0.07       0  4987.5    0.07       0
  4993.5     0.1       0
Bank Sta=4987.5,4993.5
Exp/Cntr=0.3,0.1

Type RM Length L Ch R = 1,864,675,675,675
BEGIN DESCRIPTION:
UNT017 IN SPCR 2.0
END DESCRIPTION:
XS GIS Cut Line= 3
      2232437.70     13269196.88      2233037.72     13268546.85
      2232937.73     13268146.88
#Sta/Elev= 30
  4142.2  254.28  4177.7  253.98  4212.8  251.78  4255.4  251.28  4361.4  247.63
  4375.6  246.39  4425.5  245.55  4439.6  243.37  4489.0  241.63  4510.0  242.79
  4517.3  241.51  4580.8  238.91  4686.9  235.73  4765.1  234.30  4917.0  233.76
  4991.4  232.77  4998.8  230.18  5002.6  229.92  5005.3  229.42  5008.6  229.92
  5019.7  230.06  5023.4  231.49  5026.9  231.49  5037.1  233.08  5109.3  233.30
  5214.9  236.72  5279.9  239.94  5397.9  246.88  5428.8  247.52  5439.1  249.08
#Mann=6,-1,0
  4142.2     0.1       0  4917.0    0.07       0  5002.6    0.07       0
  5008.6    0.07       0  5026.9     0.1       0  5279.9    0.05       0
Bank Sta=5002.6,5008.6
Exp/Cntr=0.3,0.1

Type RM Length L Ch R = 1,189,0,0,0
BEGIN DESCRIPTION:
UNT017 IN SPCR 1.0
END DESCRIPTION:
XS GIS Cut Line= 3
      2233103.10     13269318.62      2233742.01     13268596.38
      2233332.74     13268221.79
#Sta/Elev= 30
  4177.2  245.25  4252.5  243.77  4323.7  241.20  4330.3  241.96  4379.8  239.40
  4593.0  233.52  4642.3  233.16  4656.6  232.25  4713.4  231.81  4720.1  231.19
  4847.3  231.02  4897.5  230.16  4918.4  230.62  4981.9  229.45  4986.5  227.27
  4989.2  226.77  4992.5  227.27  5017.9  229.07  5053.0  228.72  5109.9  229.96
  5144.8  229.29  5215.1  229.70  5228.8  230.67  5285.6  231.25  5335.5  231.41
  5363.9  230.71  5420.0  232.00  5651.4  232.70  5682.1  232.59  5696.3  233.32
#Mann=4,-1,0
  4177.2     0.1       0  4986.5    0.07       0  4992.5     0.1       0
  5651.4    0.05       0
Bank Sta=4986.5,4992.5
Exp/Cntr=0.3,0.1

Chan Stop Cuts=-1