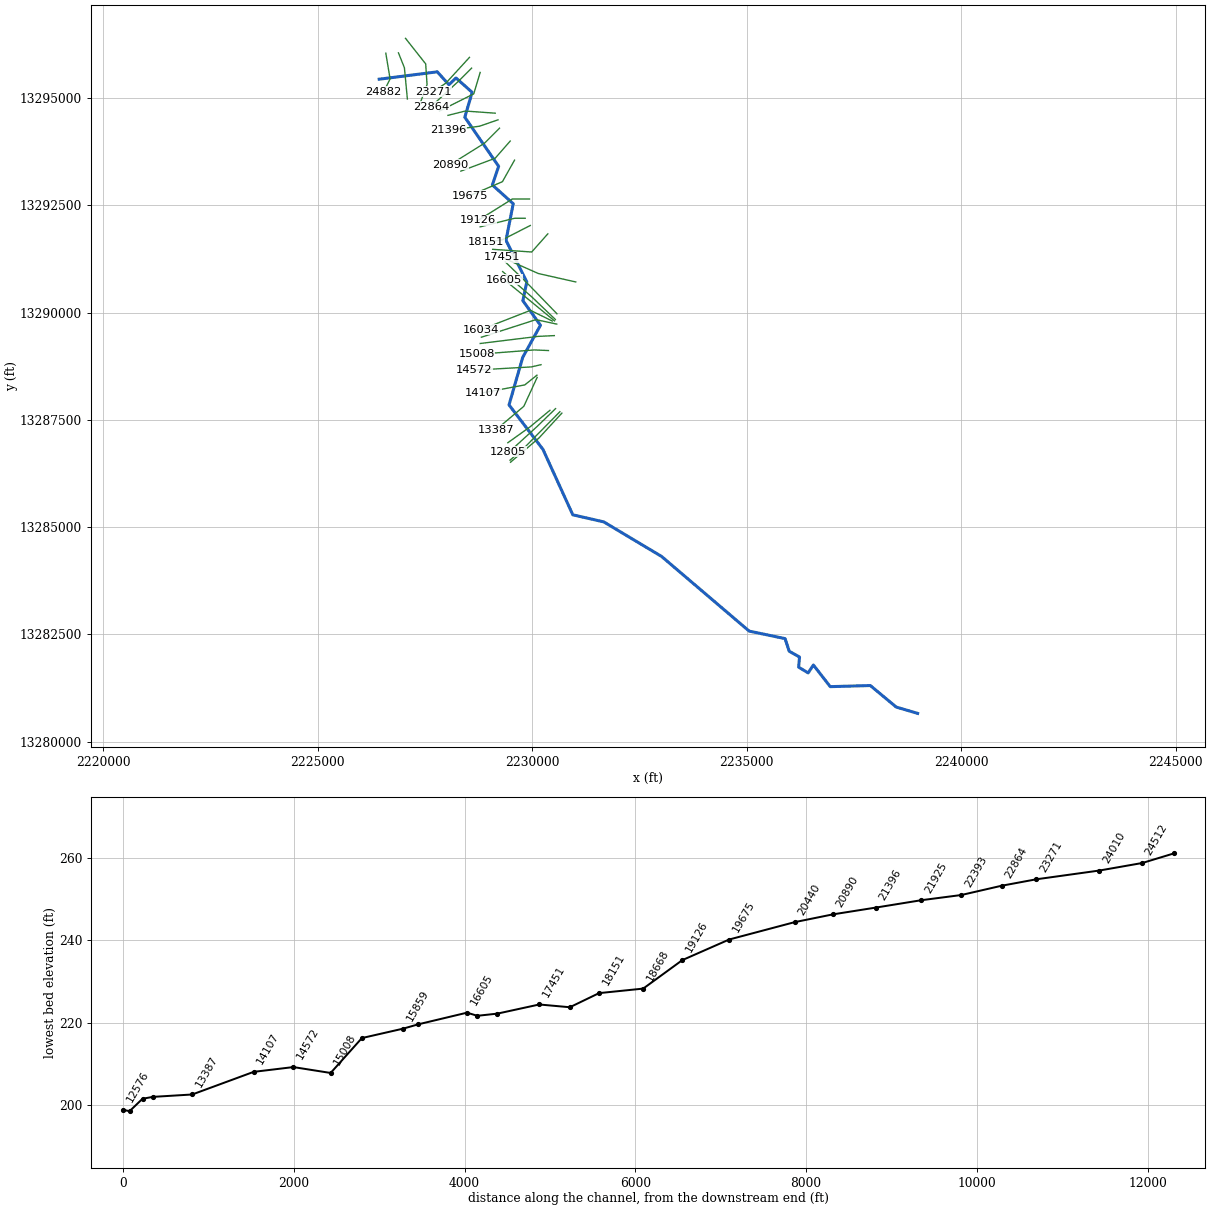
--- UNT018 IN SPCR.prj (project) ---

Proj Title=UNT018 IN SPCR Base Level Engineering
Current Plan=p01
Default Exp/Contr=0.3,0.1
English Units
Geom File=g01
Flow File=f01
Plan File=p01
Y Axis Title=Elevation
X Axis Title(PF)=Main Channel Distance
X Axis Title(XS)=Station
BEGIN DESCRIPTION:
dUNT018 IN SPCR
END DESCRIPTION:
DSS Export Rating Curves= 0
DSS Export Rating Curve Sorted= 0
DSS Export Volume Flow Curves= 0
DXF OffsetX= 0
DXF OffsetY= 0
DXF ScaleX= 1
DXF ScaleY= 10

--- UNT018 IN SPCR.p01 (plan) ---

Plan Title=Multiple Run
Short Identifier=Multiple
Geom File=g01
Flow File=f01
Subcritical Flow
K Sum by GR= 0
Std Step Tol= 0.01
Critical Tol= 0.01
Num of Std Step Trials= 20
Max Error Tol= 0.3
Flow Tol Ratio= 0.001
Split Flow NTrial= 30
Split Flow Tol= 0.02
Split Flow Ratio= 0.02
Log Output Level= 0
Friction Slope Method= 1
Unsteady Friction Slope Method= 2
Unsteady Bridges Friction Slope Method= 1
Parabolic Critical Depth
Global Vel Dist=  1 , 1 , 1
Global Log Level= 0
CheckData=True
Encroach Param= -1, 0, 0, 0
BEGIN DESCRIPTION:
Multiple Run
END DESCRIPTION:

--- UNT018 IN SPCR.f01 (steady flow) ---

Flow Title=Multiple
Program Version=4.10
Number of Profiles= 7
Profile Names=10-year,25-year,50-year,1pct_min,100-year,1pct_plu,500-year
River Rch & RM=UNT018 IN SPCR,Reach-1         ,24882
     251     350     432     393     532     719     817
River Rch & RM=UNT018 IN SPCR,Reach-1         ,22864
     288     404     501     457     618     836     955
River Rch & RM=UNT018 IN SPCR,Reach-1         ,19126
     394     561     702     646     874    1182    1374
River Rch & RM=UNT018 IN SPCR,Reach-1         ,16034
     717    1053    1347    1265    1710    2313    2801
River Rch & RM=UNT018 IN SPCR,Reach-1         ,15374
     717    1053    1347    1265    1710    2313    2801
River Rch & RM=UNT018 IN SPCR,Reach-1         ,12653
     745    1091    1393    1304    1764    2385    2874
River Rch & RM=UNT018 IN SPCR,Reach-1         ,6801
     795    1162    1482    1386    1875    2535    3046
Boundary for River Rch & Prof#=UNT018 IN SPCR,Reach-1         , 1
Up Type= 0
Dn Type= 3
Dn Slope=0.005
Boundary for River Rch & Prof#=UNT018 IN SPCR,Reach-1         , 2
Up Type= 0
Dn Type= 3
Dn Slope=0.005
Boundary for River Rch & Prof#=UNT018 IN SPCR,Reach-1         , 3
Up Type= 0
Dn Type= 3
Dn Slope=0.005
Boundary for River Rch & Prof#=UNT018 IN SPCR,Reach-1         , 4
Up Type= 0
Dn Type= 3
Dn Slope=0.005
Boundary for River Rch & Prof#=UNT018 IN SPCR,Reach-1         , 5
Up Type= 0
Dn Type= 3
Dn Slope=0.005
Boundary for River Rch & Prof#=UNT018 IN SPCR,Reach-1         , 6
Up Type= 0
Dn Type= 3
Dn Slope=0.005
Boundary for River Rch & Prof#=UNT018 IN SPCR,Reach-1         , 7
Up Type= 0
Dn Type= 3
Dn Slope=0.005
DSS Import GetInterval= 0
DSS Import GetPeak= 0
DSS Import FillOption= 0

--- UNT018 IN SPCR.g01 (geometry) ---

Geom Title=Existing Conditions

River Reach=UNT018 IN SPCR,Reach-1
Reach XY= 30
      2226433.77     13295438.93      2227787.64     13295610.86
      2228059.16     13295310.17      2228224.27     13295467.37
      2228600.33     13295133.38      2228429.78     13294552.43
      2229218.37     13293408.17      2229071.51     13292973.63
      2229557.72     13292536.86      2229389.49     13291682.38
      2229874.85     13290715.67      2229782.95     13290275.53
      2230193.27     13289703.47      2229779.74     13288955.53
      2229460.12     13287846.85      2230252.14     13286807.74
      2230947.02     13285284.31      2231668.81     13285119.38
      2233016.63     13284314.23      2235058.16     13282573.43
      2235894.41     13282398.50      2235992.07     13282103.78
      2236232.35     13281969.43      2236211.17     13281733.43
      2236432.68     13281598.93      2236555.52     13281783.41
      2236948.04     13281278.89      2237882.54     13281304.66
      2238486.78     13280802.72      2238985.28     13280655.89

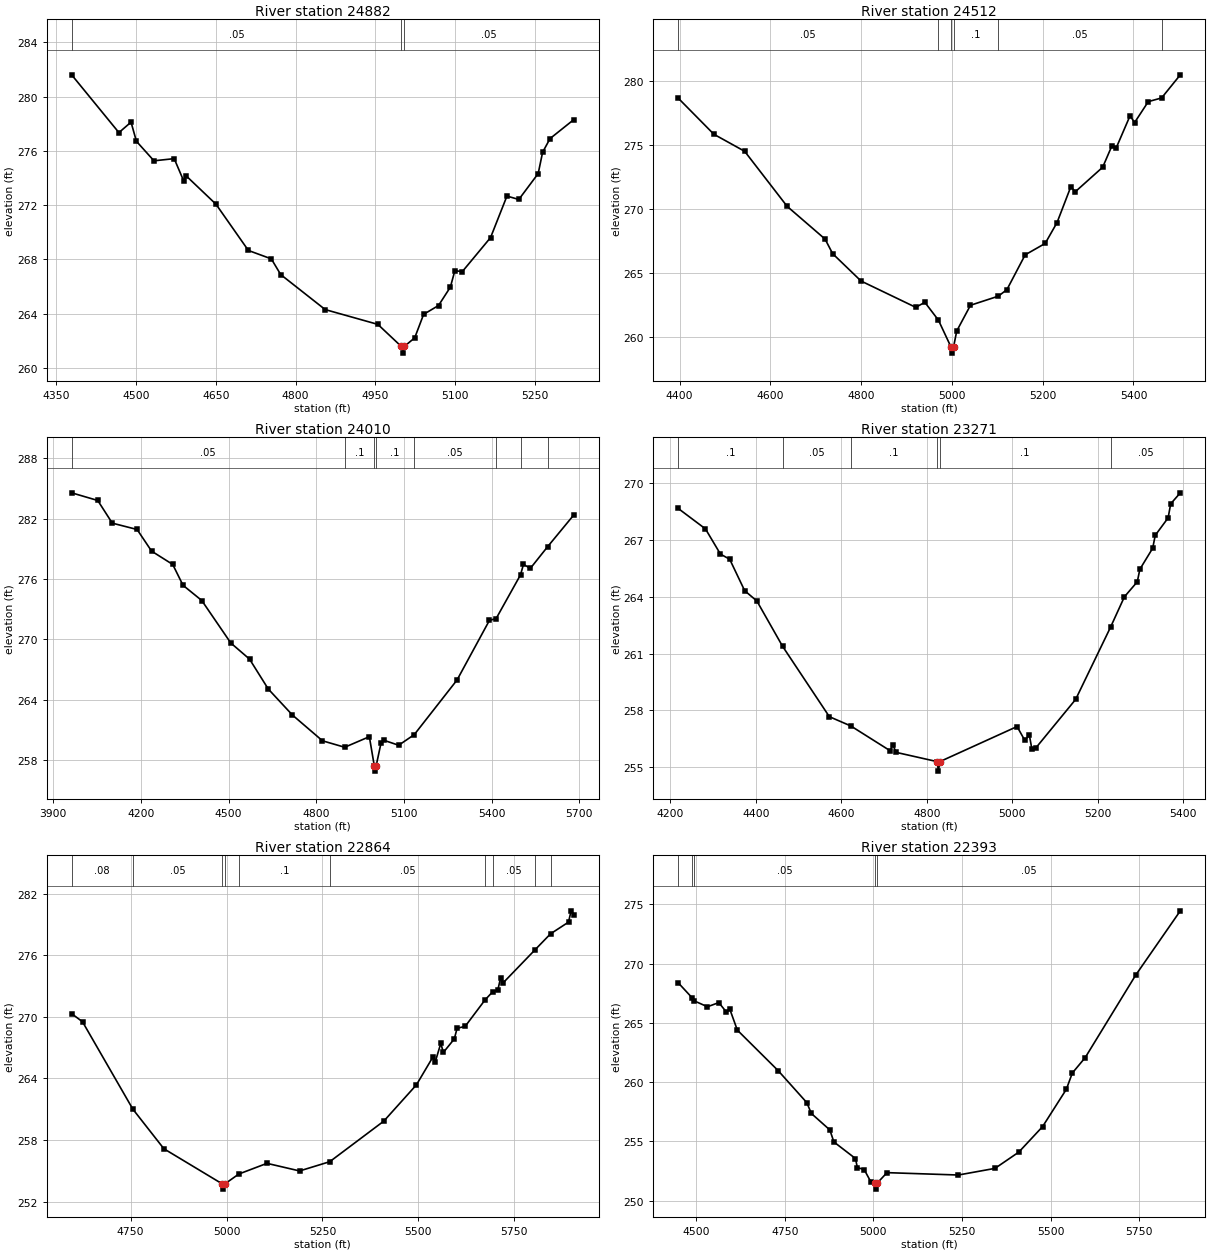
Type RM Length L Ch R = 1,24882,370,370,370
BEGIN DESCRIPTION:
UNT018 IN SPCR 42.0
END DESCRIPTION:
XS GIS Cut Line= 3
      2226587.71     13296046.90      2226687.72     13295446.85
      2226537.74     13295146.89
#Sta/Elev= 30
  4379.3  281.61  4468.1  277.35  4490.9  278.12  4501.0  276.71  4534.0  275.27
  4572.0  275.43  4589.7  273.80  4594.8  274.15  4650.5  272.07  4711.4  268.66
  4754.5  268.04  4772.2  266.88  4855.8  264.30  4954.7  263.21  4998.6  261.59
  5001.3  261.09  5004.6  261.59  5024.0  262.22  5040.7  263.95  5068.7  264.60
  5091.0  265.96  5099.4  267.17  5113.4  267.10  5166.5  269.61  5197.3  272.67
  5219.6  272.42  5256.0  274.33  5264.3  275.90  5278.3  276.91  5323.0  278.31
#Mann=3,-1,0
  4379.3    0.05       0  4998.6    0.03       0  5004.6    0.05       0
Bank Sta=4998.6,5004.6
Exp/Cntr=0.3,0.1

Type RM Length L Ch R = 1,24512,502,502,502
BEGIN DESCRIPTION:
UNT018 IN SPCR 41.0
END DESCRIPTION:
XS GIS Cut Line= 3
      2226882.72     13296052.96      2227021.61     13295705.72
      2227091.05     13294976.61
#Sta/Elev= 30
  4396.8  278.64  4475.5  275.82  4543.4  274.49  4637.0  270.20  4720.5  267.65
  4737.3  266.51  4799.8  264.38  4920.3  262.33  4940.4  262.72  4970.3  261.33
  4997.7  259.26  5000.4  258.76  5003.7  259.26  5010.7  260.49  5040.9  262.49
  5102.3  263.20  5121.2  263.71  5161.4  266.42  5205.5  267.31  5231.7  268.94
  5261.9  271.72  5271.9  271.34  5332.2  273.25  5352.3  274.90  5362.3  274.78
  5392.5  277.26  5402.5  276.73  5432.6  278.36  5462.0  278.65  5503.2  280.45
#Mann=6,-1,0
  4396.8    0.05       0  4970.3     0.1       0  4997.7    0.07       0
  5003.7     0.1       0  5102.3    0.05       0  5462.0     0.1       0
Bank Sta=4997.7,5003.7
Exp/Cntr=0.3,0.1

Type RM Length L Ch R = 1,24010,739,739,739
BEGIN DESCRIPTION:
UNT018 IN SPCR 40.0
END DESCRIPTION:
XS GIS Cut Line= 4
      2227047.15     13296391.61      2227517.66     13295795.54
      2227549.20     13295313.63      2227383.93     13294867.29
#Sta/Elev= 30
  3962.7  284.56  4052.0  283.80  4101.7  281.55  4186.6  280.92  4236.3  278.77
  4308.5  277.45  4343.8  275.38  4407.9  273.87  4507.3  269.65  4571.4  268.05
  4635.5  265.08  4718.1  262.50  4821.0  259.94  4897.0  259.30  4981.3  260.35
  4998.4  257.43  5001.1  256.93  5004.4  257.43  5021.4  259.74  5031.4  259.99
  5081.6  259.50  5134.9  260.55  5281.4  265.98  5392.4  271.91  5414.8  272.06
  5498.6  276.42  5508.6  277.46  5532.2  277.06  5591.5  279.22  5681.0  282.37
#Mann=8,-1,0
  3962.7    0.05       0  4897.0     0.1       0  4998.4    0.07       0
  5004.4     0.1       0  5134.9    0.05       0  5414.8     0.1       0
  5498.6    0.05       0  5591.5     0.1       0
Bank Sta=4998.4,5004.4
Exp/Cntr=0.3,0.1

Type RM Length L Ch R = 1,23271,407,407,407
BEGIN DESCRIPTION:
UNT018 IN SPCR 39.0
END DESCRIPTION:
XS GIS Cut Line= 3
      2228537.75     13295946.88      2227987.72     13295346.85
      2227687.75     13295146.88
#Sta/Elev= 30
  4218.4  268.65  4282.3  267.57  4317.4  266.24  4339.0  265.97  4374.1  264.31
  4402.5  263.77  4462.7  261.38  4572.1  257.67  4622.4  257.18  4713.9  255.88
  4720.7  256.18  4728.1  255.79  4824.4  255.30  4827.1  254.80  4830.4  255.30
  5011.1  257.15  5029.0  256.43  5039.9  256.69  5045.9  255.95  5054.9  256.02
  5148.1  258.58  5229.8  262.39  5262.2  263.99  5292.3  264.78  5298.3  265.44
  5328.3  266.55  5334.3  267.23  5364.4  268.15  5370.4  268.89  5392.9  269.47
#Mann=6,-1,0
  4218.4     0.1       0  4462.7    0.05       0  4622.4     0.1       0
  4824.4    0.07       0  4830.4     0.1       0  5229.8    0.05       0
Bank Sta=4824.4,4830.4
Exp/Cntr=0.3,0.1

Type RM Length L Ch R = 1,22864,471,471,471
BEGIN DESCRIPTION:
UNT018 IN SPCR 38.0
END DESCRIPTION:
XS GIS Cut Line= 3
      2228587.73     13295696.87      2228287.72     13295396.85
      2227637.70     13294796.83
#Sta/Elev= 30
  4596.2  270.31  4624.5  269.52  4755.8  261.01  4836.6  257.16  4989.2  253.73
  4991.9  253.23  4995.2  253.73  5031.9  254.70  5105.3  255.74  5190.3  255.00
  5268.9  255.90  5409.8  259.85  5494.8  263.38  5537.3  266.06  5544.1  265.65
  5558.3  267.41  5565.1  266.54  5593.5  267.85  5600.9  268.89  5621.8  269.07
  5673.7  271.65  5693.8  272.45  5706.9  272.60  5714.3  273.81  5721.1  273.32
  5803.8  276.52  5844.3  278.08  5891.2  279.22  5898.0  280.32  5905.1  279.96
#Mann=10,-1,0
  4596.2    0.08       0  4755.8    0.05       0  4989.2   0.035       0
  4995.2    0.05       0  5031.9     0.1       0  5268.9    0.05       0
  5673.7    0.08       0  5693.8    0.05       0  5803.8    0.08       0
  5844.3    0.05       0
Bank Sta=4989.2,4995.2
Exp/Cntr=0.3,0.1

Type RM Length L Ch R = 1,22393,468,468,468
BEGIN DESCRIPTION:
UNT018 IN SPCR 37.0
END DESCRIPTION:
XS GIS Cut Line= 3
      2228787.71     13295596.83      2228637.72     13295096.85
      2227837.73     13294696.86
#Sta/Elev= 30
  4449.4  268.39  4489.4  267.10  4495.4  266.85  4532.0  266.36  4564.2  266.71
  4585.1  265.93  4595.5  266.13  4616.4  264.39  4731.3  260.98  4812.2  258.28
  4825.2  257.36  4877.4  255.97  4888.7  254.96  4949.6  253.56  4954.9  252.80
  4974.2  252.63  4993.7  251.55  5004.7  251.48  5007.5  250.98  5010.7  251.48
  5038.5  252.37  5239.7  252.17  5343.1  252.73  5410.2  254.10  5477.3  256.25
  5544.4  259.40  5561.2  260.77  5597.5  262.07  5740.0  269.03  5865.8  274.45
#Mann=5,-1,0
  4449.4    0.05       0  4489.4    0.08       0  4495.4    0.05       0
  5004.7   0.035       0  5010.7    0.05       0
Bank Sta=5004.7,5010.7
Exp/Cntr=0.3,0.1

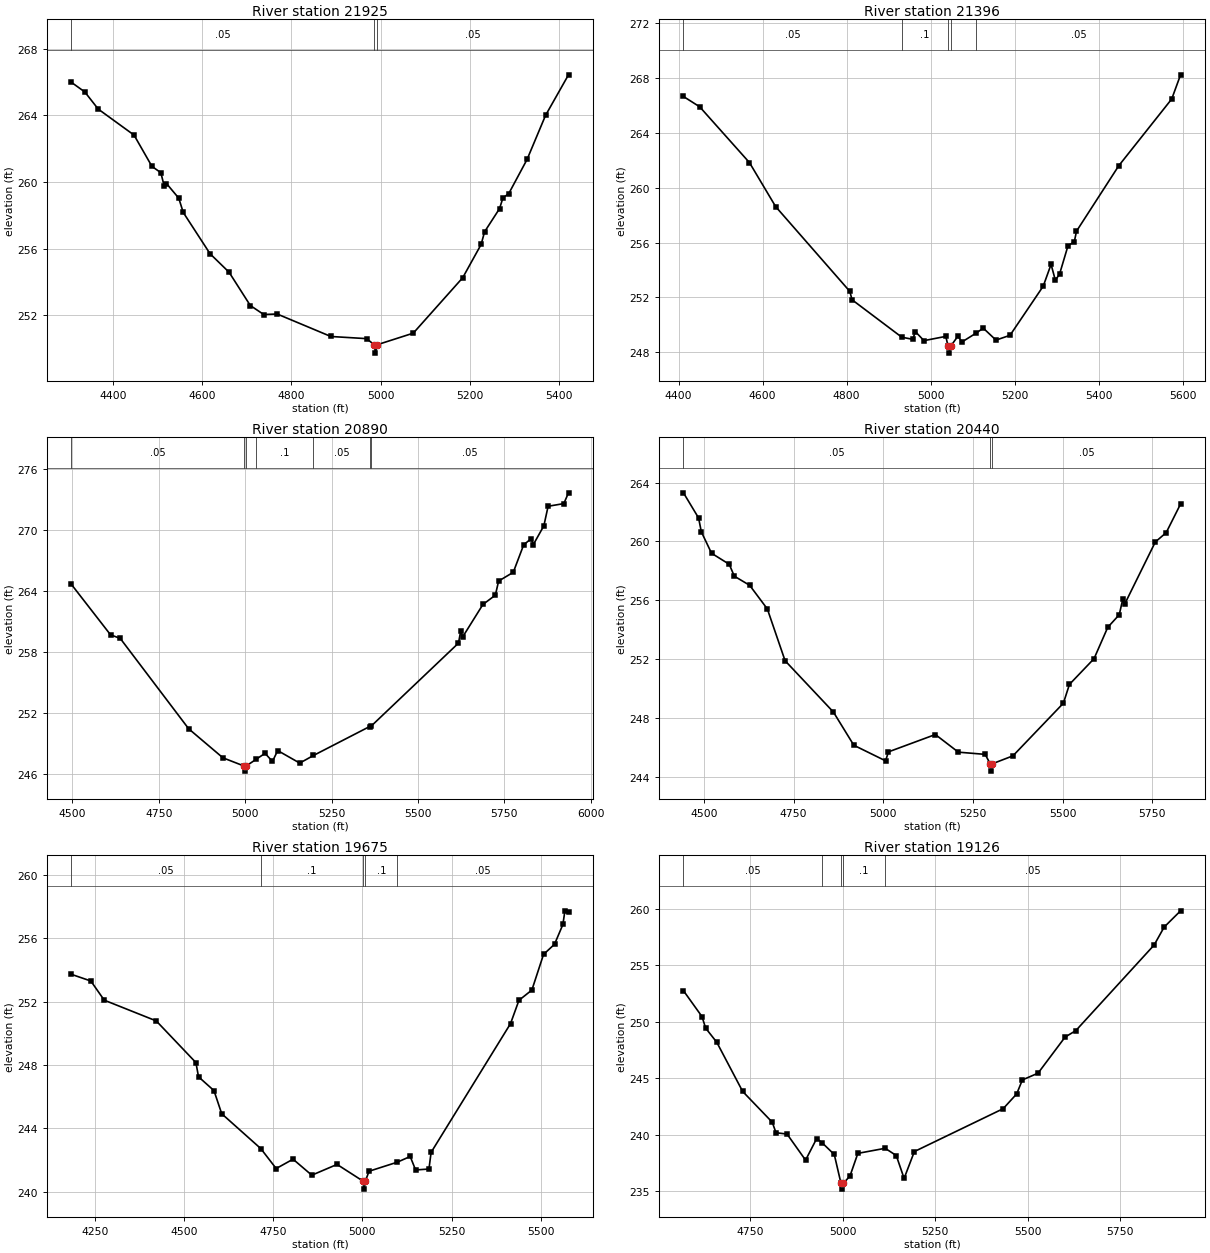
Type RM Length L Ch R = 1,21925,529,529,529
BEGIN DESCRIPTION:
UNT018 IN SPCR 36.0
END DESCRIPTION:
XS GIS Cut Line= 3
      2229137.75     13294646.85      2228437.72     13294696.85
      2228037.74     13294596.86
#Sta/Elev= 30
  4306.9  265.99  4337.0  265.41  4367.1  264.38  4447.3  262.82  4487.4  260.94
  4507.4  260.56  4515.0  259.74  4520.0  259.91  4547.5  259.03  4557.6  258.17
  4617.7  255.69  4660.3  254.58  4707.9  252.58  4738.0  252.04  4768.1  252.07
  4888.4  250.72  4968.6  250.59  4985.7  250.22  4988.4  249.72  4991.7  250.22
  5073.1  250.92  5183.9  254.25  5225.2  256.25  5232.9  257.01  5266.4  258.40
  5274.1  259.05  5287.0  259.30  5328.2  261.36  5369.5  264.00  5421.0  266.44
#Mann=3,-1,0
  4306.9    0.05       0  4985.7   0.035       0  4991.7    0.05       0
Bank Sta=4985.7,4991.7
Exp/Cntr=0.3,0.1

Type RM Length L Ch R = 1,21396,506,506,506
BEGIN DESCRIPTION:
UNT018 IN SPCR 35.0
END DESCRIPTION:
XS GIS Cut Line= 3
      2229204.16     13294492.13      2228772.89     13294343.14
      2228052.08     13294249.12
#Sta/Elev= 30
  4411.5  266.65  4450.1  265.90  4568.6  261.83  4631.0  258.62  4807.5  252.44
  4812.8  251.83  4931.2  249.10  4956.9  248.95  4963.8  249.50  4983.9  248.85
  5035.9  249.16  5041.4  248.44  5044.2  247.94  5047.4  248.44  5064.6  249.17
  5074.7  248.76  5108.1  249.40  5125.1  249.76  5155.4  248.89  5188.8  249.24
  5267.8  252.82  5286.5  254.41  5296.6  253.26  5306.6  253.69  5326.8  255.77
  5341.8  256.06  5347.0  256.83  5447.8  261.61  5573.7  266.47  5594.7  268.23
#Mann=5,-1,0
  4411.5    0.05       0  4931.2     0.1       0  5041.4    0.07       0
  5047.4     0.1       0  5108.1    0.05       0
Bank Sta=5041.4,5047.4
Exp/Cntr=0.3,0.1

Type RM Length L Ch R = 1,20890,450,450,450
BEGIN DESCRIPTION:
UNT018 IN SPCR 34.0
END DESCRIPTION:
XS GIS Cut Line= 3
      2229237.74     13294296.87      2228887.72     13293946.85
      2228087.72     13293446.85
#Sta/Elev= 30
  4497.1  264.63  4610.3  259.68  4638.5  259.32  4836.5  250.44  4935.5  247.59
  4996.8  246.78  4999.5  246.28  5002.8  246.78  5031.5  247.44  5057.5  248.03
  5078.8  247.23  5094.1  248.30  5157.8  247.07  5197.6  247.82  5360.0  250.66
  5363.5  250.67  5617.1  258.86  5623.6  260.04  5629.5  259.48  5687.9  262.66
  5723.8  263.57  5733.3  264.96  5775.7  265.82  5805.8  268.52  5827.6  269.13
  5833.5  268.53  5864.2  270.39  5876.5  272.31  5921.9  272.57  5935.5  273.63
#Mann=7,-1,0
  4497.1    0.05       0  4996.8   0.035       0  5002.8    0.05       0
  5031.5     0.1       0  5197.6    0.05       0  5360.0     0.1       0
  5363.5    0.05       0
Bank Sta=4996.8,5002.8
Exp/Cntr=0.3,0.1

Type RM Length L Ch R = 1,20440,765,765,765
BEGIN DESCRIPTION:
UNT018 IN SPCR 33.0
END DESCRIPTION:
XS GIS Cut Line= 3
      2229487.69     13293996.82      2229137.72     13293596.85
      2228337.68     13293296.84
#Sta/Elev= 30
  4443.0  263.31  4485.2  261.60  4492.8  260.66  4521.3  259.20  4570.6  258.45
  4584.8  257.64  4627.6  257.02  4676.9  255.41  4726.3  251.89  4861.0  248.40
  4918.0  246.14  5006.5  245.08  5014.5  245.69  5145.3  246.87  5209.4  245.67
  5284.2  245.52  5298.1  244.88  5300.8  244.38  5304.1  244.88  5361.6  245.42
  5502.2  249.00  5519.1  250.28  5587.7  252.03  5625.9  254.16  5658.0  255.02
  5667.8  256.08  5673.1  255.74  5758.6  259.97  5788.8  260.60  5828.9  262.55
#Mann=3,-1,0
  4443.0    0.05       0  5298.1   0.035       0  5304.1    0.05       0
Bank Sta=5298.1,5304.1
Exp/Cntr=0.3,0.1

Type RM Length L Ch R = 1,19675,549,549,549
BEGIN DESCRIPTION:
UNT018 IN SPCR 32.0
END DESCRIPTION:
XS GIS Cut Line= 3
      2229588.34     13293551.23      2229306.06     13293049.40
      2228553.31     13292727.92
#Sta/Elev= 30
  4183.7  253.73  4238.2  253.31  4275.8  252.10  4421.7  250.79  4532.9  248.16
  4540.3  247.26  4583.6  246.39  4605.3  244.93  4714.9  242.73  4758.1  241.47
  4805.4  242.06  4858.0  241.05  4928.8  241.73  5002.1  240.67  5004.8  240.17
  5008.1  240.67  5018.6  241.30  5097.6  241.87  5134.0  242.23  5149.1  241.38
  5186.6  241.44  5192.6  242.49  5415.4  250.62  5439.0  252.09  5475.3  252.74
  5508.0  254.99  5538.8  255.63  5562.3  256.88  5567.9  257.74  5578.0  257.65
#Mann=5,-1,0
  4183.7    0.05       0  4714.9     0.1       0  5002.1    0.07       0
  5008.1     0.1       0  5097.6    0.05       0
Bank Sta=5002.1,5008.1
Exp/Cntr=0.3,0.1

Type RM Length L Ch R = 1,19126,458,458,458
BEGIN DESCRIPTION:
UNT018 IN SPCR 31.0
END DESCRIPTION:
XS GIS Cut Line= 3
      2229937.67     13292646.85      2229537.72     13292646.85
      2228737.68     13292146.83
#Sta/Elev= 30
  4569.4  252.75  4619.4  250.46  4629.4  249.43  4659.4  248.18  4729.4  243.82
  4809.4  241.09  4819.4  240.16  4849.4  240.04  4899.4  237.73  4929.4  239.64
  4944.7  239.25  4977.0  238.23  4995.2  235.66  4998.0  235.16  5001.2  235.66
  5019.5  236.33  5040.7  238.33  5114.5  238.78  5144.5  238.14  5165.7  236.11
  5193.4  238.49  5433.4  242.29  5469.9  243.60  5485.3  244.84  5527.7  245.44
  5600.8  248.64  5629.7  249.21  5841.4  256.80  5868.5  258.39  5912.8  259.83
#Mann=5,-1,0
  4569.4    0.05       0  4944.7     0.1       0  4995.2    0.07       0
  5001.2     0.1       0  5114.5    0.05       0
Bank Sta=4995.2,5001.2
Exp/Cntr=0.3,0.1

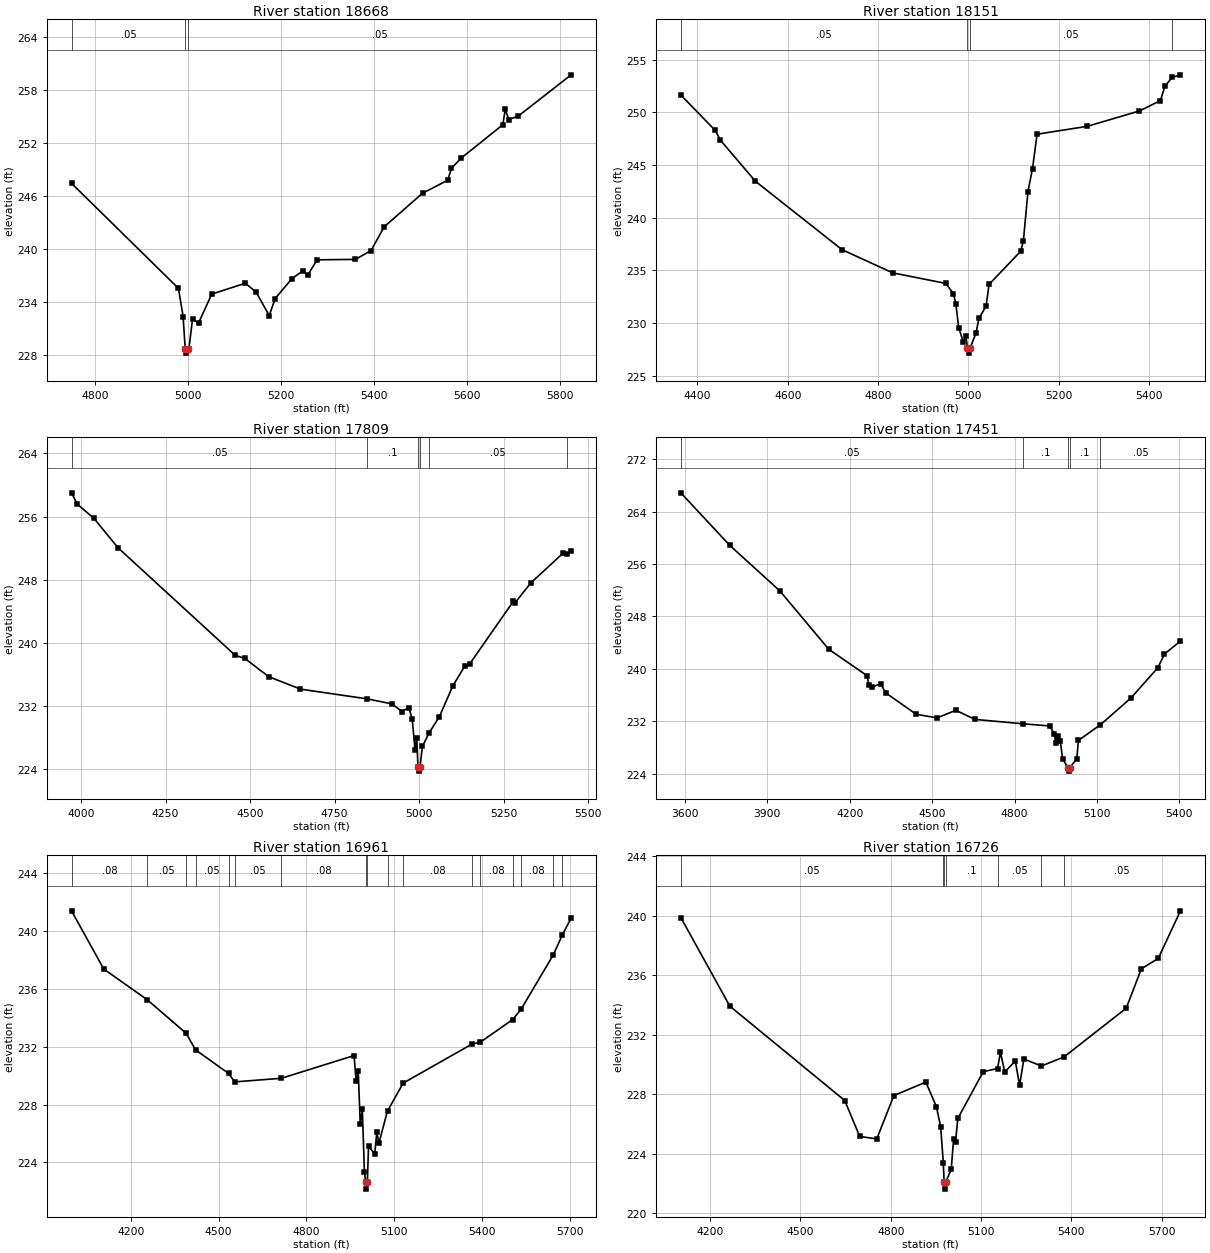
Type RM Length L Ch R = 1,18668,517,517,517
BEGIN DESCRIPTION:
UNT018 IN SPCR 30.0
END DESCRIPTION:
XS GIS Cut Line= 3
      2229837.69     13292196.85      2229587.72     13292196.85
      2228787.71     13291996.85
#Sta/Elev= 30
  4750.0  247.46  4980.0  235.57  4990.0  232.38  4994.5  228.74  4997.2  228.24
  5000.5  228.74  5002.5  228.74  5010.3  232.10  5023.2  231.64  5051.5  234.92
  5123.7  236.15  5146.9  235.16  5175.2  232.49  5188.1  234.42  5224.2  236.68
  5247.4  237.54  5257.7  237.04  5278.3  238.80  5360.7  238.85  5394.2  239.85
  5422.6  242.54  5505.0  246.34  5559.2  247.81  5566.9  249.14  5587.5  250.29
  5677.7  254.09  5682.9  255.82  5690.6  254.68  5711.2  255.08  5824.6  259.74
#Mann=3,-1,0
  4750.0    0.05       0  4994.5   0.035       0  5000.5    0.05       0
Bank Sta=4994.5,5000.5
Exp/Cntr=0.3,0.1

Type RM Length L Ch R = 1,18151,342,342,342
BEGIN DESCRIPTION:
UNT018 IN SPCR 29.0
END DESCRIPTION:
XS GIS Cut Line= 3
      2229955.88     13292028.84      2229301.25     13291694.46
      2228933.86     13291637.93
#Sta/Elev= 30
  4363.1  251.65  4439.2  248.30  4450.9  247.36  4528.1  243.47  4720.4  236.96
  4832.7  234.76  4950.3  233.76  4966.9  232.78  4972.5  231.80  4978.6  229.57
  4989.1  228.18  4994.7  228.73  4998.1  227.64  5000.8  227.14  5004.1  227.64
  5017.0  229.03  5023.5  230.45  5039.2  231.58  5046.0  233.67  5116.1  236.82
  5122.0  237.81  5132.1  242.48  5142.2  244.67  5152.3  247.93  5263.6  248.68
  5379.2  250.14  5425.5  251.12  5435.6  252.50  5451.4  253.32  5469.9  253.57
#Mann=4,-1,0
  4363.1    0.05       0  4998.1   0.035       0  5004.1    0.05       0
  5451.4    0.08       0
Bank Sta=4998.1,5004.1
Exp/Cntr=0.3,0.1

Type RM Length L Ch R = 1,17809,358,358,358
BEGIN DESCRIPTION:
UNT018 IN SPCR 28.0
END DESCRIPTION:
XS GIS Cut Line= 3
      2230364.60     13291834.10      2229988.21     13291410.67
      2229078.71     13291473.39
#Sta/Elev= 30
  3971.8  259.01  3988.9  257.56  4038.3  255.77  4109.3  252.04  4456.4  238.39
  4484.8  238.00  4554.7  235.70  4649.1  234.11  4847.5  232.87  4919.7  232.24
  4949.8  231.27  4969.8  231.78  4979.9  230.28  4988.2  226.38  4993.2  227.92
  4996.9  224.21  4999.7  223.71  5002.9  224.21  5009.9  226.84  5029.7  228.56
  5060.1  230.61  5100.2  234.54  5136.1  237.09  5150.3  237.33  5278.9  245.24
  5283.9  245.05  5330.7  247.58  5426.8  251.38  5438.7  251.30  5450.0  251.62
#Mann=6,-1,0
  3971.8    0.05       0  4847.5     0.1       0  4996.9    0.07       0
  5002.9     0.1       0  5029.7    0.05       0  5438.7    0.08       0
Bank Sta=4996.9,5002.9
Exp/Cntr=0.3,0.1

Type RM Length L Ch R = 1,17451,490,490,490
BEGIN DESCRIPTION:
Mapping XS ddd69753
END DESCRIPTION:
XS GIS Cut Line= 3
      2231015.39     13290712.83      2230145.03     13290908.86
      2229298.26     13291285.20
#Sta/Elev= 30
  3585.0  266.88  3762.3  258.89  3945.6  251.90  4123.7  242.98  4263.8  238.93
  4269.4  237.49  4279.6  237.17  4312.1  237.74  4330.9  236.33  4441.9  233.06
  4518.0  232.51  4586.1  233.67  4655.8  232.28  4832.4  231.60  4928.0  231.28
  4944.8  230.02  4950.2  228.64  4956.8  229.76  4966.7  228.95  4974.6  226.27
  4994.8  224.88  4997.6  224.38  5000.8  224.88  5026.5  226.29  5032.3  229.07
  5112.5  231.46  5223.5  235.54  5322.0  240.19  5345.3  242.25  5403.8  244.23
#Mann=5,-1,0
  3585.0    0.05       0  4832.4     0.1       0  4994.8    0.07       0
  5000.8     0.1       0  5112.5    0.05       0
Bank Sta=4994.8,5000.8
Exp/Cntr=0.3,0.1

Type RM Length L Ch R = 1,16961,235,235,235
BEGIN DESCRIPTION:
UNT018 IN SPCR 27.0
END DESCRIPTION:
XS GIS Cut Line= 4
      2230577.53     13289970.77      2229955.88     13290611.26
      2229791.04     13290776.09      2229372.28     13291180.74
#Sta/Elev= 30
  3997.0  241.39  4107.2  237.37  4256.2  235.24  4388.6  232.93  4421.1  231.78
  4534.1  230.15  4554.9  229.57  4714.6  229.82  4962.9  231.39  4970.0  229.65
  4977.1  230.33  4984.1  226.64  4991.2  227.67  4998.3  223.36  5002.4  222.66
  5005.1  222.16  5008.4  222.66  5012.4  225.13  5033.6  224.58  5040.7  226.10
  5047.8  225.34  5077.3  227.56  5131.0  229.49  5367.6  232.20  5393.7  232.30
  5505.4  233.88  5534.3  234.60  5643.3  238.32  5674.9  239.72  5705.0  240.89
#Mann=17,-1,0
  3997.0    0.08       0  4256.2    0.05       0  4388.6    0.08       0
  4421.1    0.05       0  4534.1    0.08       0  4554.9    0.05       0
  4714.6    0.08       0  5002.4    0.07       0  5008.4    0.08       0
  5077.3     0.1       0  5131.0    0.08       0  5367.6    0.05       0
  5393.7    0.08       0  5505.4    0.05       0  5534.3    0.08       0
  5643.3    0.05       0  5674.9    0.08       0
Bank Sta=5002.4,5008.4
Exp/Cntr=0.3,0.1

Type RM Length L Ch R = 1,16726,121,121,121
BEGIN DESCRIPTION:
UNT018 IN SPCR 26.0
END DESCRIPTION:
XS GIS Cut Line= 3
      2230539.85     13289838.90      2229988.84     13290366.36
      2229311.66     13290954.19
#Sta/Elev= 30
  4102.7  239.87  4265.4  233.92  4647.2  227.58  4696.9  225.17  4753.5  225.00
  4810.2  227.91  4916.5  228.82  4951.6  227.17  4965.8  225.81  4974.6  223.37
  4977.1  222.13  4979.8  221.63  4983.1  222.13  5000.9  222.96  5008.6  224.97
  5015.2  224.80  5022.8  226.38  5107.3  229.52  5154.7  229.73  5164.3  230.82
  5178.6  229.50  5213.7  230.23  5227.9  228.61  5242.2  230.37  5300.3  229.90
  5375.1  230.50  5582.1  233.78  5632.5  236.43  5688.5  237.12  5762.2  240.32
#Mann=7,-1,0
  4102.7    0.05       0  4974.6     0.1       0  4977.1    0.07       0
  4983.1     0.1       0  5154.7    0.05       0  5300.3    0.08       0
  5375.1    0.05       0
Bank Sta=4977.1,4983.1
Exp/Cntr=0.3,0.1

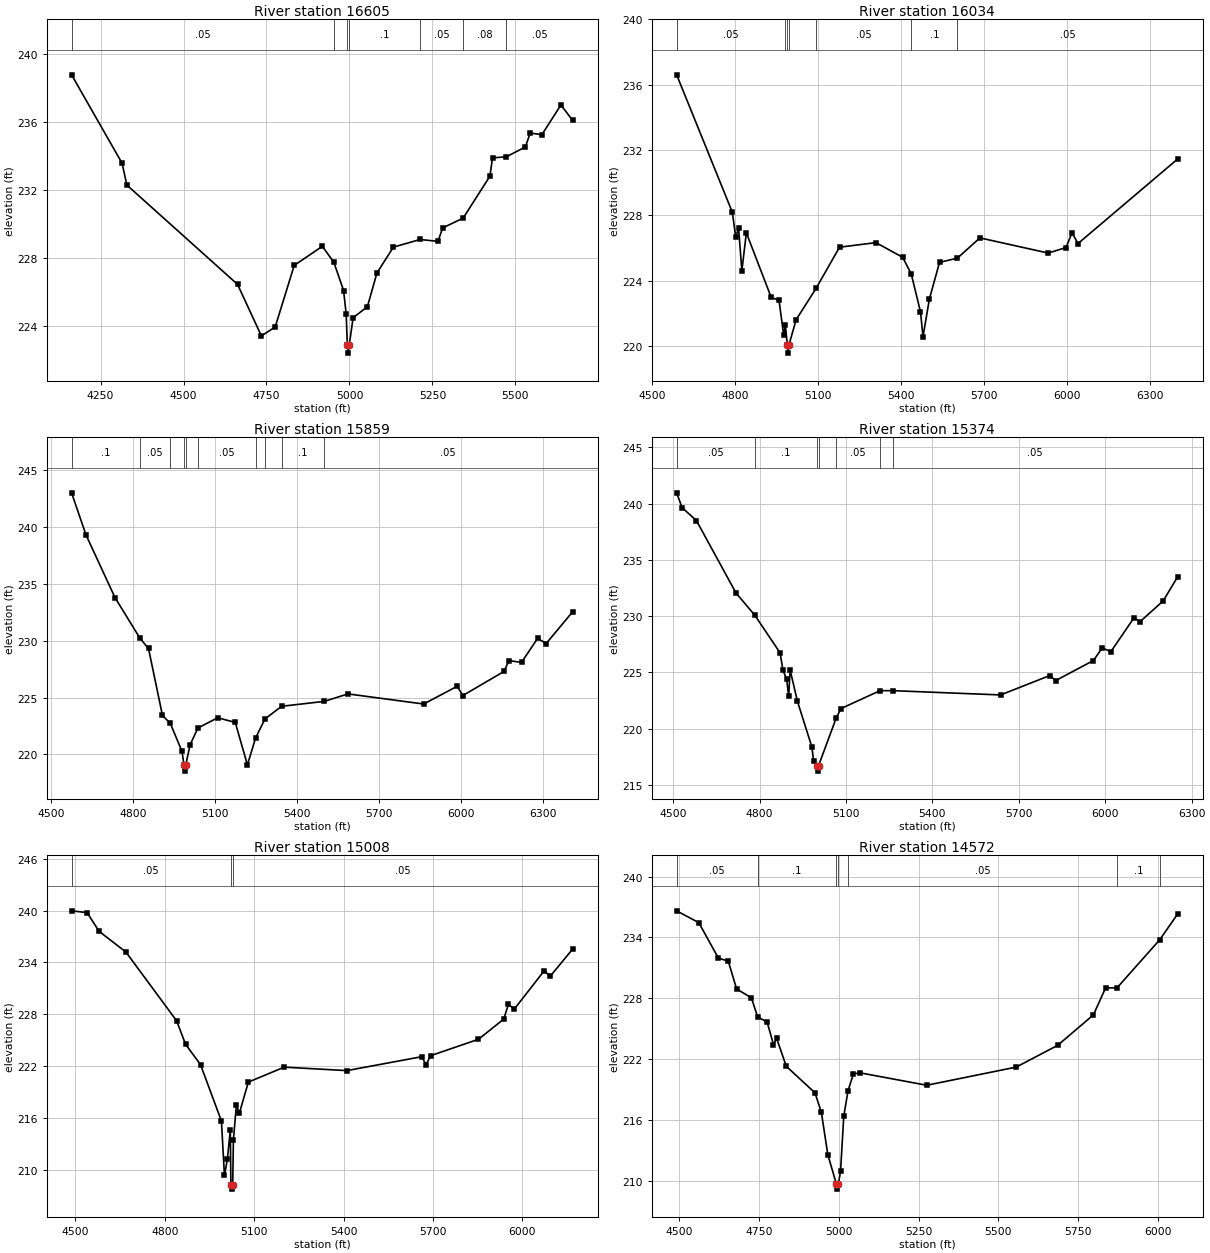
Type RM Length L Ch R = 1,16605,571,571,571
BEGIN DESCRIPTION:
Mapping XS 7b73a6a7
END DESCRIPTION:
XS GIS Cut Line= 3
      2230521.06     13289805.89      2229965.30     13290262.75
      2229353.14     13290761.89
#Sta/Elev= 30
  4162.8  238.75  4315.0  233.55  4329.3  232.27  4662.9  226.43  4734.7  223.40
  4776.3  223.93  4833.7  227.55  4918.4  228.67  4953.2  227.72  4982.3  226.07
  4990.2  224.68  4993.6  222.89  4996.4  222.39  4999.6  222.89  5011.0  224.47
  5054.1  225.12  5082.8  227.10  5132.4  228.62  5212.9  229.07  5266.6  228.96
  5281.0  229.75  5342.7  230.33  5423.2  232.79  5431.1  233.87  5472.6  233.93
  5530.2  234.51  5544.5  235.33  5579.7  235.23  5637.2  236.98  5672.1  236.08
#Mann=7,-1,0
  4162.8    0.05       0  4953.2     0.1       0  4993.6    0.07       0
  4999.6     0.1       0  5212.9    0.05       0  5342.7    0.08       0
  5472.6    0.05       0
Bank Sta=4993.6,4999.6
Exp/Cntr=0.3,0.1

Type RM Length L Ch R = 1,16034,175,175,175
BEGIN DESCRIPTION:
UNT018 IN SPCR 25.0
END DESCRIPTION:
XS GIS Cut Line= 3
      2230469.26     13289801.19      2229960.59     13290050.82
      2228802.38     13289598.84
#Sta/Elev= 30
  4589.6  236.61  4790.8  228.19  4803.0  226.67  4813.3  227.21  4825.2  224.61
  4841.4  226.93  4931.3  222.97  4959.4  222.80  4976.3  220.65  4982.4  221.26
  4989.3  220.06  4992.1  219.56  4995.3  220.06  5021.3  221.61  5093.4  223.53
  5178.1  226.05  5309.6  226.33  5406.2  225.43  5437.2  224.41  5470.6  222.09
  5479.7  220.57  5502.8  222.88  5539.4  225.12  5604.0  225.38  5685.3  226.62
  5932.2  225.69  5996.6  226.03  6018.1  226.94  6039.5  226.27  6399.5  231.45
#Mann=7,-1,0
  4589.6    0.05       0  4982.4     0.1       0  4989.3    0.07       0
  4995.3     0.1       0  5093.4    0.05       0  5437.2     0.1       0
  5604.0    0.05       0
Bank Sta=4989.3,4995.3
Exp/Cntr=0.3,0.1

Type RM Length L Ch R = 1,15859,485,485,485
BEGIN DESCRIPTION:
Mapping XS c1c922e1
END DESCRIPTION:
XS GIS Cut Line= 3
      2230572.82     13289730.57      2230087.74     13289834.18
      2228816.15     13289424.44
#Sta/Elev= 30
  4574.9  243.03  4627.5  239.33  4733.5  233.81  4824.8  230.23  4856.2  229.32
  4907.3  223.42  4935.8  222.73  4978.9  220.25  4986.1  219.02  4988.9  218.52
  4992.1  219.02  5008.2  220.83  5036.9  222.32  5109.4  223.22  5173.5  222.81
  5218.0  219.07  5247.6  221.42  5281.9  223.11  5343.0  224.23  5498.4  224.66
  5585.8  225.32  5862.6  224.43  5985.0  225.99  6006.0  225.18  6156.4  227.30
  6174.1  228.25  6220.5  228.10  6279.2  230.21  6310.7  229.76  6406.9  232.54
#Mann=10,-1,0
  4574.9     0.1       0  4824.8    0.05       0  4935.8     0.1       0
  4986.1    0.07       0  4992.1     0.1       0  5036.9    0.05       0
  5247.6     0.1       0  5281.9    0.05       0  5343.0     0.1       0
  5498.4    0.05       0
Bank Sta=4986.1,4992.1
Exp/Cntr=0.3,0.1

Type RM Length L Ch R = 1,15374,366,366,366
BEGIN DESCRIPTION:
Mapping XS 22213ea7
END DESCRIPTION:
XS GIS Cut Line= 3
      2230516.29     13289462.13      2230134.84     13289443.29
      2228787.91     13289278.45
#Sta/Elev= 30
  4512.3  240.95  4530.9  239.64  4581.0  238.48  4718.3  232.05  4783.7  230.07
  4871.3  226.73  4881.3  225.19  4894.2  224.38  4901.2  222.86  4906.2  225.21
  4931.6  222.42  4982.0  218.34  4987.7  217.08  4999.1  216.72  5001.9  216.22
  5005.1  216.72  5066.0  220.93  5082.7  221.78  5218.4  223.37  5263.1  223.37
  5636.8  222.99  5807.3  224.71  5828.3  224.27  5959.2  226.05  5989.4  227.16
  6019.7  226.84  6100.3  229.86  6120.4  229.49  6201.0  231.34  6251.2  233.48
#Mann=7,-1,0
  4512.3    0.05       0  4783.7     0.1       0  4999.1    0.07       0
  5005.1     0.1       0  5066.0    0.05       0  5218.4     0.1       0
  5263.1    0.05       0
Bank Sta=4999.1,5005.1
Exp/Cntr=0.3,0.1

Type RM Length L Ch R = 1,15008,436,436,436
BEGIN DESCRIPTION:
UNT018 IN SPCR 24.0
END DESCRIPTION:
XS GIS Cut Line= 3
      2230379.74     13289113.62      2230050.07     13289127.75
      2228703.13     13289024.14
#Sta/Elev= 30
  4487.0  239.98  4539.1  239.77  4579.1  237.61  4669.2  235.21  4839.4  227.24
  4869.5  224.52  4919.6  222.16  4989.8  215.63  4999.9  209.33  5009.9  211.22
  5019.6  214.64  5021.6  208.24  5024.3  207.74  5027.6  208.24  5030.0  213.46
  5040.0  217.45  5050.0  216.53  5080.1  220.14  5200.5  221.87  5410.7  221.47
  5661.8  223.08  5676.5  222.16  5691.9  223.20  5852.4  225.10  5937.3  227.44
  5952.7  229.14  5972.7  228.60  6073.0  233.04  6093.1  232.40  6167.9  235.53
#Mann=3,-1,0
  4487.0    0.05       0  5021.6    0.03       0  5027.6    0.05       0
Bank Sta=5021.6,5027.6
Exp/Cntr=0.3,0.1

Type RM Length L Ch R = 1,14572,465,465,465
BEGIN DESCRIPTION:
UNT018 IN SPCR 23.0
END DESCRIPTION:
XS GIS Cut Line= 3
      2230205.46     13288783.94      2229979.43     13288732.15
      2228642.34     13288656.82
#Sta/Elev= 30
  4491.4  236.63  4560.9  235.46  4622.4  231.96  4653.2  231.67  4679.3  228.93
  4725.9  228.04  4745.4  226.16  4775.1  225.66  4795.1  223.44  4805.1  224.04
  4835.2  221.29  4925.3  218.67  4945.3  216.74  4965.4  212.58  4992.4  209.67
  4995.2  209.17  4998.4  209.67  5005.4  210.92  5015.5  216.36  5028.8  218.87
  5045.5  220.52  5065.5  220.65  5275.9  219.42  5556.3  221.21  5686.5  223.36
  5798.4  226.36  5836.8  229.03  5872.5  229.03  6006.4  233.77  6062.5  236.31
#Mann=7,-1,0
  4491.4    0.05       0  4745.4     0.1       0  4992.4    0.07       0
  4998.4     0.1       0  5028.8    0.05       0  5872.5     0.1       0
  6006.4    0.05       0
Bank Sta=4992.4,4998.4
Exp/Cntr=0.3,0.1

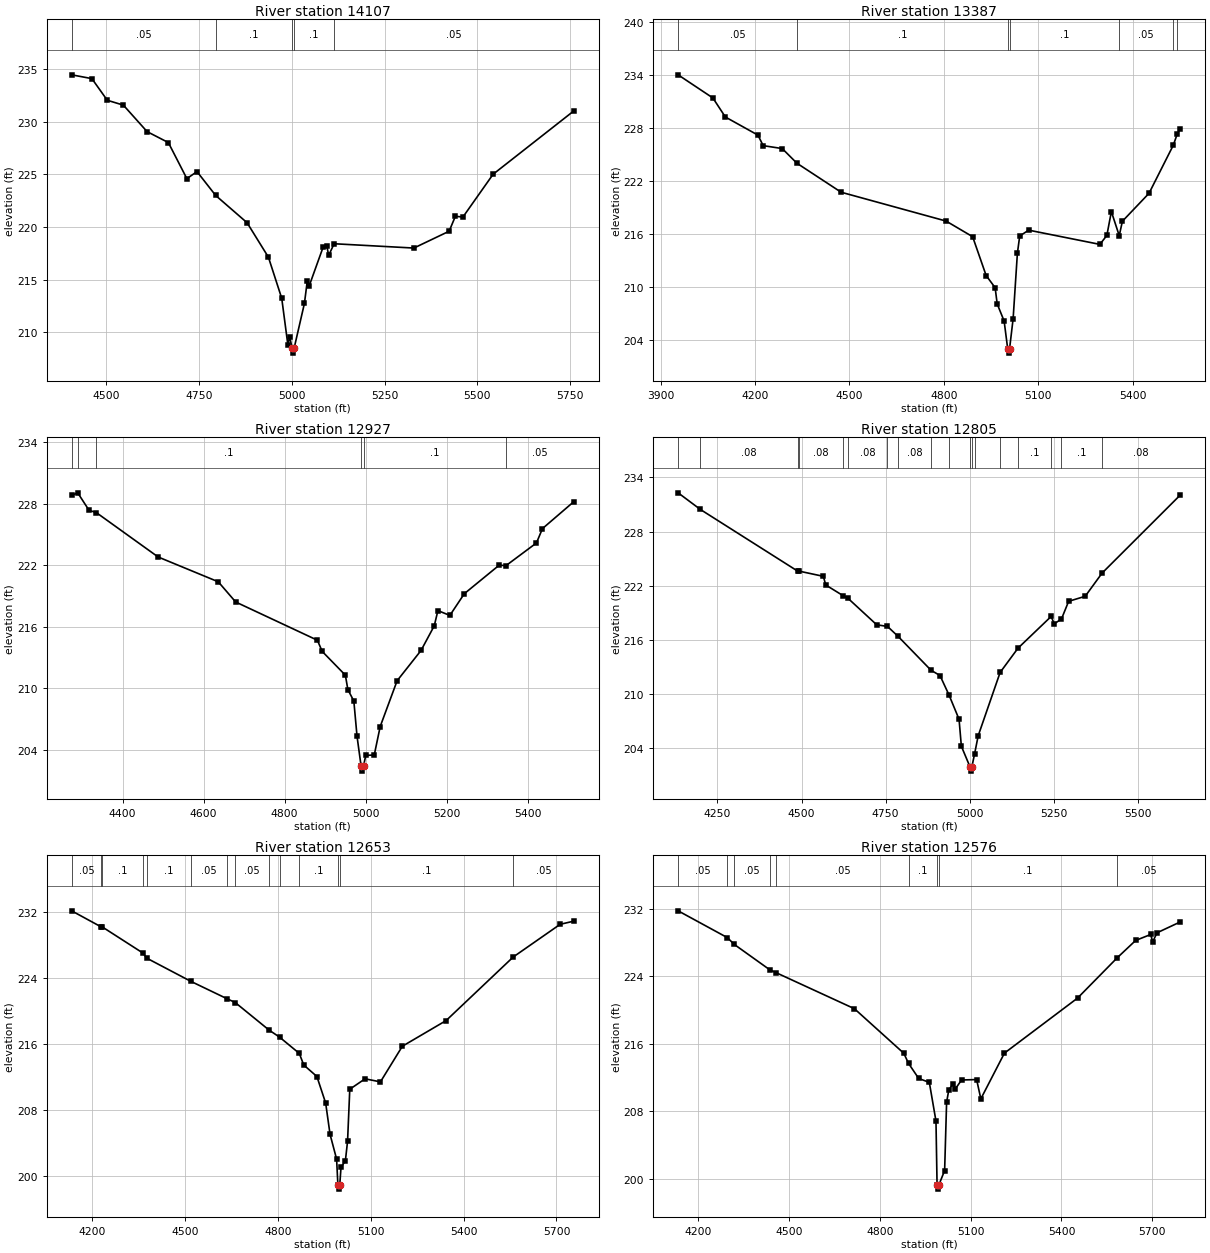
Type RM Length L Ch R = 1,14107,720,720,720
BEGIN DESCRIPTION:
UNT018 IN SPCR 22.0
END DESCRIPTION:
XS GIS Cut Line= 3
      2230111.32     13288539.08      2229828.72     13288312.99
      2228853.88     13288129.33
#Sta/Elev= 30
  4406.3  234.47  4460.8  234.11  4502.4  232.05  4545.7  231.59  4609.7  229.07
  4667.0  228.03  4716.9  224.60  4744.2  225.27  4794.6  223.00  4879.2  220.41
  4936.8  217.13  4972.7  213.22  4989.2  208.80  4994.3  209.56  5000.3  208.51
  5003.0  208.01  5006.3  208.51  5033.8  212.73  5041.7  214.90  5046.7  214.40
  5084.7  218.13  5094.1  218.22  5099.2  217.30  5113.9  218.41  5328.9  218.00
  5424.0  219.60  5440.8  221.02  5461.2  220.95  5542.6  225.02  5760.2  231.04
#Mann=5,-1,0
  4406.3    0.05       0  4794.6     0.1       0  5000.3    0.07       0
  5006.3     0.1       0  5113.9    0.05       0
Bank Sta=5000.3,5006.3
Exp/Cntr=0.3,0.1

Type RM Length L Ch R = 1,13387,460,460,460
BEGIN DESCRIPTION:
UNT018 IN SPCR 21.0
END DESCRIPTION:
XS GIS Cut Line= 3
      2230116.00     13288487.24      2229805.17     13287813.78
      2229151.60     13287263.66
#Sta/Elev= 30
  3955.4  233.99  4066.0  231.37  4105.5  229.22  4209.1  227.17  4225.7  225.98
  4286.2  225.65  4333.0  223.99  4473.5  220.71  4806.9  217.45  4891.4  215.68
  4934.3  211.29  4962.9  209.91  4969.5  208.07  4991.5  206.14  5002.8  203.01
  5005.6  202.51  5008.8  203.01  5020.1  206.41  5033.6  213.79  5041.0  215.76
  5069.6  216.42  5295.9  214.81  5318.0  215.83  5332.3  218.52  5357.3  215.80
  5367.4  217.43  5452.0  220.59  5529.0  226.02  5541.9  227.32  5551.4  227.90
#Mann=7,-1,0
  3955.4    0.05       0  4333.0     0.1       0  5002.8    0.07       0
  5008.8     0.1       0  5357.3    0.05       0  5529.0     0.1       0
  5541.9    0.05       0
Bank Sta=5002.8,5008.8
Exp/Cntr=0.3,0.1

Type RM Length L Ch R = 1,12927,122,122,122
BEGIN DESCRIPTION:
Mapping XS 90d60c5e
END DESCRIPTION:
XS GIS Cut Line= 3
      2230414.10     13287720.80      2229949.19     13287334.48
      2229432.34     13286964.83
#Sta/Elev= 30
  4274.1  228.83  4289.1  229.08  4317.1  227.37  4334.7  227.16  4487.7  222.82
  4636.1  220.40  4679.1  218.43  4880.8  214.70  4892.7  213.61  4949.9  211.29
  4956.1  209.88  4970.8  208.77  4978.7  205.33  4988.7  202.43  4991.4  201.93
  4994.7  202.43  5000.3  203.47  5021.2  203.50  5035.9  206.28  5077.7  210.75
  5136.7  213.70  5169.3  216.10  5178.4  217.59  5207.9  217.12  5243.6  219.24
  5329.6  222.02  5346.6  221.98  5421.7  224.19  5436.5  225.59  5514.0  228.22
#Mann=6,-1,0
  4274.1    0.05       0  4289.1    0.08       0  4334.7     0.1       0
  4988.7    0.07       0  4994.7     0.1       0  5346.6    0.05       0
Bank Sta=4988.7,4994.7
Exp/Cntr=0.3,0.1

Type RM Length L Ch R = 1,12805,152,152,152
BEGIN DESCRIPTION:
UNT018 IN SPCR 19.0
END DESCRIPTION:
XS GIS Cut Line= 4
      2230545.00     13287760.04      2230119.43     13287347.57
      2229602.17     13286876.14      2229442.26     13286755.39
#Sta/Elev= 30
  4133.1  232.30  4199.2  230.46  4489.2  223.61  4492.1  223.63  4564.8  223.05
  4572.0  222.09  4623.4  220.91  4638.5  220.60  4723.5  217.68  4755.5  217.50
  4787.0  216.40  4884.8  212.65  4911.6  212.06  4938.6  209.89  4968.3  207.21
  4975.1  204.23  5000.5  201.97  5003.2  201.47  5006.5  201.97  5014.2  203.33
  5025.1  205.38  5090.3  212.40  5143.5  215.09  5241.9  218.60  5251.4  217.79
  5272.8  218.33  5294.0  220.28  5343.3  220.84  5393.5  223.41  5626.0  232.06
#Mann=18,-1,0
  4133.1    0.05       0  4199.2    0.08       0  4489.2     0.1       0
  4492.1    0.08       0  4623.4     0.1       0  4638.5    0.08       0
  4755.5     0.1       0  4787.0    0.08       0  4884.8     0.1       0
  4938.6    0.08       0  5000.5    0.07       0  5006.5    0.08       0
  5014.2     0.1       0  5090.3    0.08       0  5143.5     0.1       0
  5241.9    0.08       0  5272.8     0.1       0  5393.5    0.08       0
Bank Sta=5000.5,5006.5
Exp/Cntr=0.3,0.1

Type RM Length L Ch R = 1,12653,77,77,77
BEGIN DESCRIPTION:
Mapping XS bbc0f12d
END DESCRIPTION:
XS GIS Cut Line= 3
      2230646.52     13287688.05      2229788.78     13286820.49
      2229484.31     13286558.58
#Sta/Elev= 30
  4134.4  232.12  4229.5  230.18  4233.3  230.17  4365.0  227.00  4376.5  226.40
  4519.6  223.58  4636.2  221.48  4662.7  221.02  4771.8  217.69  4805.9  216.83
  4869.4  214.87  4883.9  213.46  4926.3  212.07  4954.6  208.86  4968.8  205.07
  4990.0  202.06  4994.1  198.94  4996.8  198.44  5000.1  198.94  5004.2  201.08
  5018.3  201.87  5025.3  204.22  5032.5  210.53  5081.9  211.79  5131.5  211.42
  5202.2  215.73  5343.6  218.84  5560.2  226.53  5711.9  230.49  5756.0  230.87
#Mann=14,-1,0
  4134.4    0.05       0  4229.5    0.08       0  4233.3     0.1       0
  4365.0    0.08       0  4376.5     0.1       0  4519.6    0.05       0
  4636.2     0.1       0  4662.7    0.05       0  4771.8     0.1       0
  4805.9    0.05       0  4869.4     0.1       0  4994.1    0.07       0
  5000.1     0.1       0  5560.2    0.05       0
Bank Sta=4994.1,5000.1
Exp/Cntr=0.3,0.1

Type RM Length L Ch R = 1,12576,214,214,214
BEGIN DESCRIPTION:
Mapping XS 71873fa2
END DESCRIPTION:
XS GIS Cut Line= 3
      2230692.37     13287655.33      2230158.72     13287075.84
      2229495.54     13286510.68
#Sta/Elev= 30
  4133.5  231.73  4296.1  228.56  4319.3  227.75  4436.5  224.75  4457.4  224.41
  4716.0  220.15  4879.1  214.88  4894.8  213.68  4928.3  211.90  4963.4  211.44
  4985.4  206.86  4989.0  199.31  4991.7  198.81  4995.0  199.31  5014.0  201.01
  5020.5  209.08  5027.7  210.53  5041.4  211.25  5049.1  210.65  5069.9  211.72
  5119.7  211.77  5133.6  209.49  5211.6  214.90  5453.2  221.41  5584.0  226.17
  5645.2  228.23  5694.7  228.93  5701.3  228.05  5715.6  229.13  5792.6  230.42
#Mann=9,-1,0
  4133.5    0.05       0  4296.1     0.1       0  4319.3    0.05       0
  4436.5     0.1       0  4457.4    0.05       0  4894.8     0.1       0
  4989.0    0.07       0  4995.0     0.1       0  5584.0    0.05       0
Bank Sta=4989,4995
Exp/Cntr=0.3,0.1