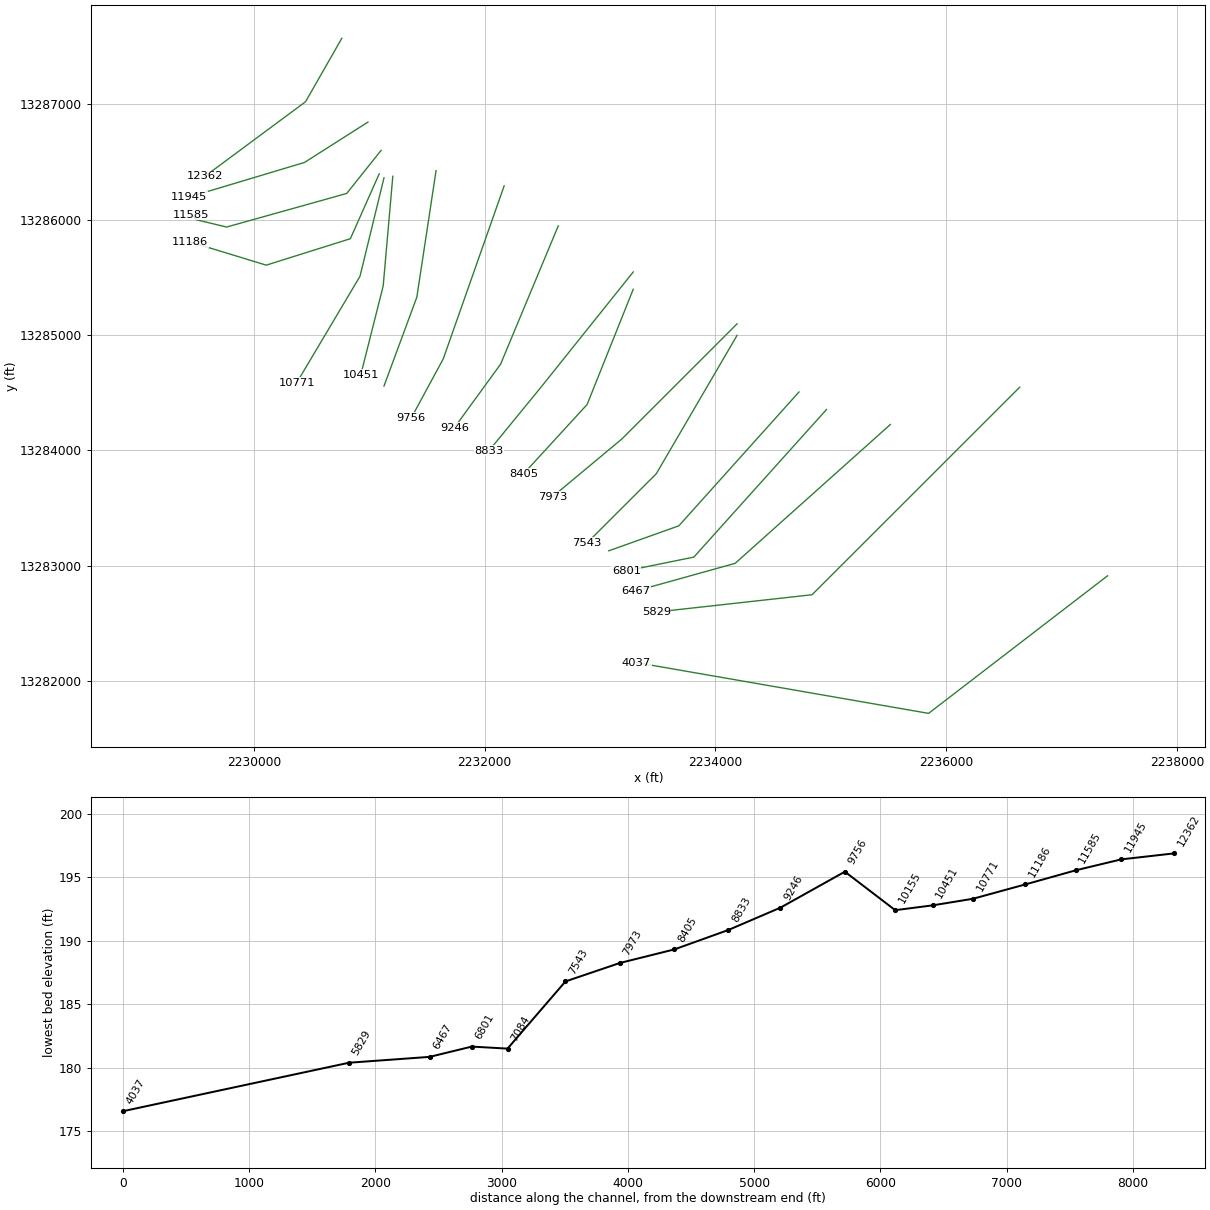
HEC-RAS study UNT018 IN SPCR.prj: UNT018 IN SPCR Base Level Engineering

--- UNT018 IN SPCR.g01 (geometry) --- (continued)

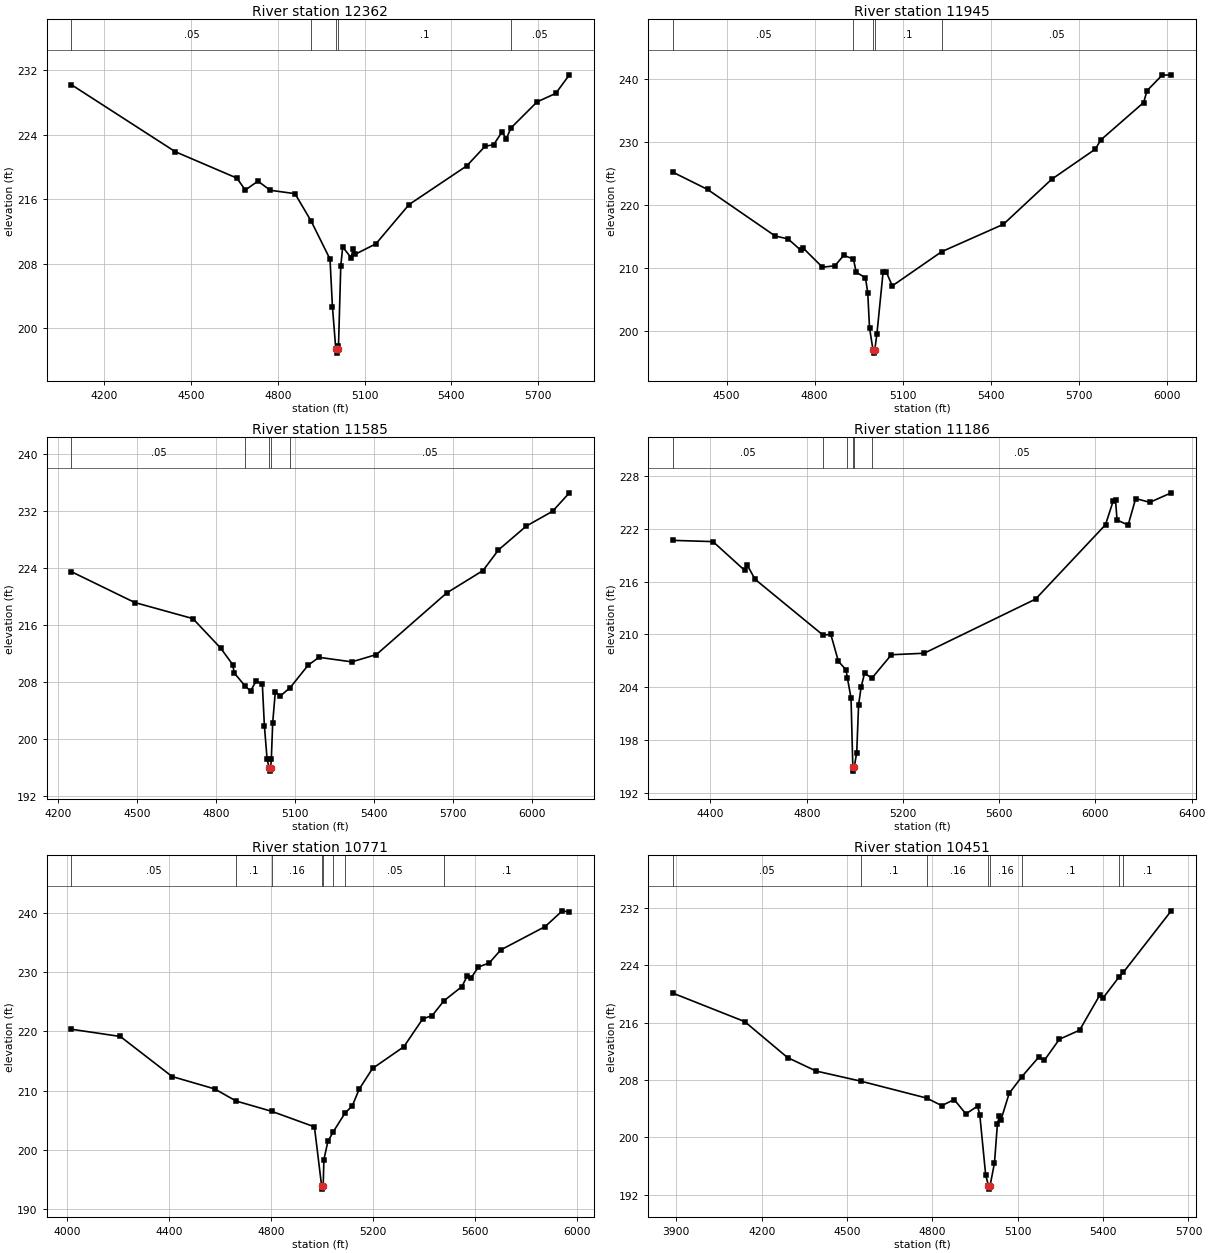
Type RM Length L Ch R = 1,12362,417,417,417
BEGIN DESCRIPTION:
UNT018 IN SPCR 18.0
END DESCRIPTION:
XS GIS Cut Line= 3
      2230761.11     13287573.49      2230446.81     13287023.46
      2229572.72     13286375.26
#Sta/Elev= 30
  4086.7  230.18  4445.9  221.87  4658.7  218.60  4687.8  217.12  4731.5  218.22
  4774.2  217.09  4859.7  216.67  4916.0  213.23  4980.7  208.55  4989.1  202.63
  5000.7  197.39  5003.5  196.89  5006.7  197.39  5010.0  197.77  5017.9  207.69
  5024.6  210.05  5053.8  208.72  5060.0  209.78  5067.7  209.15  5139.4  210.45
  5254.1  215.32  5453.6  220.12  5517.0  222.56  5546.2  222.73  5575.5  224.33
  5590.1  223.48  5606.4  224.82  5696.5  228.05  5761.2  229.11  5808.4  231.41
#Mann=5,-1,0
  4086.7    0.05       0  4916.0     0.1       0  5000.7    0.07       0
  5006.7     0.1       0  5606.4    0.05       0
Bank Sta=5000.7,5006.7
Exp/Cntr=0.3,0.1

Type RM Length L Ch R = 1,11945,360,360,360
BEGIN DESCRIPTION:
UNT018 IN SPCR 17.0
END DESCRIPTION:
XS GIS Cut Line= 3
      2230987.70     13286846.84      2230437.72     13286496.85
      2229437.75     13286196.86
#Sta/Elev= 30
  4318.5  225.15  4435.3  222.44  4665.6  215.04  4709.6  214.57  4753.7  212.74
  4759.6  213.18  4826.5  210.08  4868.8  210.30  4899.3  211.97  4932.2  211.36
  4941.6  209.26  4973.0  208.41  4980.8  206.04  4986.9  200.44  4998.7  196.92
  5001.5  196.42  5004.7  196.92  5012.2  199.53  5033.0  209.26  5043.5  209.37
  5064.4  207.11  5232.4  212.54  5442.8  216.90  5607.3  224.06  5756.0  228.85
  5774.3  230.30  5920.5  236.26  5931.8  238.13  5983.1  240.60  6014.4  240.66
#Mann=5,-1,0
  4318.5    0.05       0  4932.2     0.1       0  4998.7    0.07       0
  5004.7     0.1       0  5232.4    0.05       0
Bank Sta=4998.7,5004.7
Exp/Cntr=0.3,0.1

Type RM Length L Ch R = 1,11585,399,399,399
BEGIN DESCRIPTION:
UNT018 IN SPCR 16.0
END DESCRIPTION:
XS GIS Cut Line= 5
      2231101.60     13286601.18      2230803.66     13286227.93
      2229762.59     13285936.56      2229503.96     13285998.76
      2229454.88     13286044.57
#Sta/Elev= 30
  4250.9  223.54  4491.3  219.22  4712.3  216.96  4817.7  212.83  4863.4  210.51
  4869.6  209.32  4912.1  207.44  4931.6  206.80  4952.7  208.23  4976.2  207.72
  4983.9  201.92  4994.3  197.21  5001.6  196.06  5004.4  195.56  5007.6  196.06
  5010.3  197.25  5015.5  202.35  5025.4  206.71  5044.4  206.10  5082.0  207.28
  5150.0  210.42  5191.3  211.53  5316.2  210.89  5409.6  211.92  5676.5  220.56
  5814.6  223.71  5873.1  226.59  5979.1  229.95  6078.7  232.02  6142.7  234.61
#Mann=5,-1,0
  4250.9    0.05       0  4912.1     0.1       0  5001.6    0.07       0
  5007.6     0.1       0  5082.0    0.05       0
Bank Sta=5001.6,5007.6
Exp/Cntr=0.3,0.1

Type RM Length L Ch R = 1,11186,415,415,415
BEGIN DESCRIPTION:
UNT018 IN SPCR 15.0
END DESCRIPTION:
XS GIS Cut Line= 4
      2231085.31     13286397.68      2230835.31     13285835.17
      2230106.14     13285606.00      2229446.39     13285807.40
#Sta/Elev= 30
  4245.4  220.70  4410.5  220.56  4541.8  217.30  4552.7  217.89  4585.5  216.27
  4867.2  209.94  4900.3  210.00  4931.8  206.94  4963.3  205.98  4969.1  205.04
  4984.2  202.78  4991.7  194.95  4994.5  194.45  4997.7  194.95  5007.9  196.55
  5015.7  202.00  5026.2  204.01  5040.3  205.57  5071.1  205.03  5151.9  207.69
  5288.2  207.86  5751.2  214.02  6041.9  222.48  6073.2  225.13  6083.7  225.26
  6089.8  223.02  6136.0  222.44  6167.3  225.46  6226.2  225.03  6315.1  226.11
#Mann=6,-1,0
  4245.4    0.05       0  4867.2     0.1       0  4969.1    0.16       0
  4991.7    0.07       0  4997.7    0.16       0  5071.1    0.05       0
Bank Sta=4991.7,4997.7
Exp/Cntr=0.3,0.1

Type RM Length L Ch R = 1,10771,320,320,320
BEGIN DESCRIPTION:
Mapping XS ac612ba0
END DESCRIPTION:
XS GIS Cut Line= 3
      2231126.96     13286362.90      2230918.64     13285508.78
      2230370.04     13284585.18
#Sta/Elev= 30
  4016.5  220.37  4208.2  219.15  4411.5  212.37  4578.2  210.28  4662.3  208.23
  4801.7  206.49  4969.7  203.86  4998.0  193.82  5000.7  193.32  5004.0  193.82
  5006.8  198.31  5022.4  201.38  5044.0  203.05  5090.7  206.26  5117.9  207.37
  5145.1  210.23  5197.7  213.74  5320.4  217.41  5394.5  222.13  5431.5  222.68
  5477.6  225.18  5548.4  227.60  5569.8  229.46  5584.1  229.04  5612.7  230.90
  5655.5  231.59  5700.4  233.79  5874.9  237.75  5942.0  240.41  5969.9  240.19
#Mann=8,-1,0
  4016.5    0.05       0  4662.3     0.1       0  4801.7    0.16       0
  4998.0    0.07       0  5004.0    0.16       0  5044.0     0.1       0
  5090.7    0.05       0  5477.6     0.1       0
Bank Sta=4998,5004
Exp/Cntr=0.3,0.1

Type RM Length L Ch R = 1,10451,296,296,296
BEGIN DESCRIPTION:
UNT018 IN SPCR 14.0
END DESCRIPTION:
XS GIS Cut Line= 3
      2231203.36     13286376.79      2231120.03     13285425.45
      2230925.57     13284654.58
#Sta/Elev= 30
  3889.4  220.08  4140.3  216.14  4290.9  211.13  4391.3  209.25  4549.6  207.83
  4780.4  205.48  4832.9  204.43  4876.6  205.28  4917.7  203.28  4958.8  204.37
  4966.7  203.12  4987.3  194.77  4996.9  193.30  4999.6  192.80  5002.9  193.30
  5018.3  196.47  5028.6  201.92  5035.8  202.98  5040.9  202.43  5069.8  206.14
  5114.9  208.49  5173.0  211.15  5193.6  210.75  5246.3  213.68  5317.3  214.94
  5389.5  219.91  5399.9  219.43  5455.4  222.32  5471.1  223.00  5639.4  231.57
#Mann=8,-1,0
  3889.4    0.05       0  4549.6     0.1       0  4780.4    0.16       0
  4996.9    0.07       0  5002.9    0.16       0  5114.9     0.1       0
  5455.4    0.05       0  5471.1     0.1       0
Bank Sta=4996.9,5002.9
Exp/Cntr=0.3,0.1

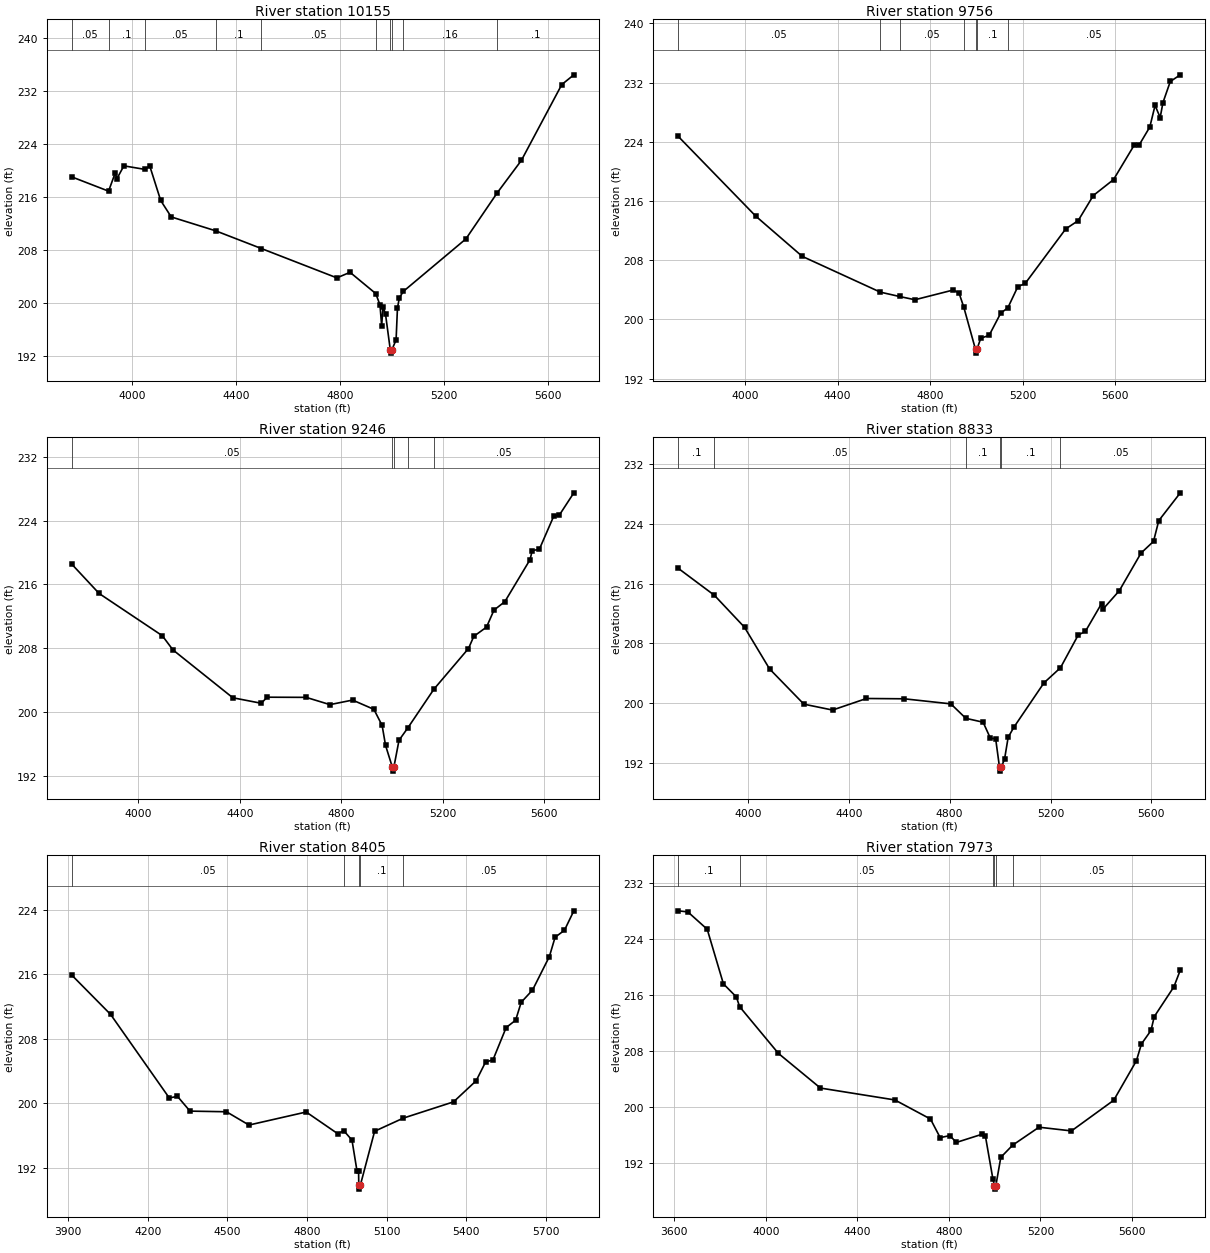
Type RM Length L Ch R = 1,10155,399,399,399
BEGIN DESCRIPTION:
UNT018 IN SPCR 13.0
END DESCRIPTION:
XS GIS Cut Line= 3
      2231578.37     13286425.48      2231411.69     13285328.23
      2231126.97     13284557.37
#Sta/Elev= 30
  3766.8  219.03  3908.8  216.87  3934.9  219.68  3940.0  218.69  3967.7  220.69
  4048.0  220.16  4067.3  220.66  4109.3  215.46  4149.8  212.98  4320.2  210.89
  4496.5  208.21  4787.0  203.78  4837.6  204.62  4936.5  201.41  4952.7  199.70
  4959.2  196.56  4964.5  199.43  4974.0  198.31  4992.4  192.92  4995.1  192.42
  4998.4  192.92  5014.7  194.41  5020.0  199.25  5027.4  200.79  5042.9  201.75
  5283.2  209.66  5403.2  216.59  5496.4  221.50  5652.0  232.96  5698.4  234.43
#Mann=10,-1,0
  3766.8    0.05       0  3908.8     0.1       0  4048.0    0.05       0
  4320.2     0.1       0  4496.5    0.05       0  4936.5     0.1       0
  4992.4    0.07       0  4998.4     0.1       0  5042.9    0.16       0
  5403.2     0.1       0
Bank Sta=4992.4,4998.4
Exp/Cntr=0.3,0.1

Type RM Length L Ch R = 1,9756,510,510,510
BEGIN DESCRIPTION:
UNT018 IN SPCR 12.0
END DESCRIPTION:
XS GIS Cut Line= 3
      2232168.64     13286293.51      2231640.86     13284793.50
      2231363.70     13284280.76
#Sta/Elev= 30
  3709.7  224.74  4045.4  213.96  4246.8  208.52  4584.4  203.69  4667.7  203.10
  4734.4  202.66  4900.7  203.98  4925.3  203.56  4945.8  201.66  4996.5  195.95
  4999.2  195.45  5002.5  195.95  5019.2  197.46  5055.5  197.85  5105.5  200.84
  5136.6  201.58  5179.7  204.43  5211.5  204.86  5387.0  212.23  5440.6  213.34
  5506.3  216.74  5593.8  218.89  5682.5  223.51  5705.3  223.60  5750.7  225.99
  5773.5  228.91  5795.6  227.27  5807.6  229.29  5839.4  232.14  5882.7  233.04
#Mann=7,-1,0
  3709.7    0.05       0  4584.4     0.1       0  4667.7    0.05       0
  4945.8     0.1       0  4996.5    0.07       0  5002.5     0.1       0
  5136.6    0.05       0
Bank Sta=4996.5,5002.5
Exp/Cntr=0.3,0.1

Type RM Length L Ch R = 1,9246,413,413,413
BEGIN DESCRIPTION:
UNT018 IN SPCR 11.0
END DESCRIPTION:
XS GIS Cut Line= 3
      2232637.73     13285946.87      2232137.72     13284746.85
      2231737.72     13284196.85
#Sta/Elev= 30
  3736.7  218.56  3845.1  214.87  4094.2  209.58  4135.9  207.81  4372.1  201.81
  4484.2  201.12  4507.5  201.88  4661.3  201.86  4755.1  200.95  4844.4  201.52
  4928.4  200.36  4960.9  198.34  4974.4  195.84  5001.2  193.12  5004.0  192.62
  5007.2  193.12  5027.5  196.49  5061.9  198.02  5165.2  202.89  5301.4  207.98
  5322.3  209.50  5372.5  210.66  5401.9  212.79  5444.8  213.85  5544.1  219.11
  5552.6  220.24  5580.8  220.41  5638.4  224.62  5659.2  224.67  5716.8  227.48
#Mann=5,-1,0
  3736.7    0.05       0  5001.2    0.03       0  5007.2    0.05       0
  5061.9     0.1       0  5165.2    0.05       0
Bank Sta=5001.2,5007.2
Exp/Cntr=0.3,0.1

Type RM Length L Ch R = 1,8833,428,428,428
BEGIN DESCRIPTION:
UNT018 IN SPCR 10.0
END DESCRIPTION:
XS GIS Cut Line= 3
      2233287.69     13285546.82      2232487.72     13284546.85
      2232037.73     13283996.86
#Sta/Elev= 30
  3723.4  218.07  3867.2  214.44  3986.7  210.15  4085.9  204.57  4222.0  199.84
  4335.7  199.05  4470.1  200.60  4619.8  200.56  4804.7  199.88  4864.2  197.94
  4932.7  197.42  4961.6  195.27  4982.4  195.21  4997.8  191.36  5000.5  190.86
  5003.8  191.36  5017.6  192.44  5032.0  195.39  5054.2  196.72  5174.1  202.70
  5239.4  204.72  5309.8  209.11  5338.5  209.61  5402.4  213.33  5408.8  212.61
  5472.7  215.05  5558.8  220.10  5608.4  221.67  5629.2  224.45  5714.6  228.18
#Mann=6,-1,0
  3723.4     0.1       0  3867.2    0.05       0  4864.2     0.1       0
  4997.8    0.07       0  5003.8     0.1       0  5239.4    0.05       0
Bank Sta=4997.8,5003.8
Exp/Cntr=0.3,0.1

Type RM Length L Ch R = 1,8405,432,432,432
BEGIN DESCRIPTION:
UNT018 IN SPCR 9.0
END DESCRIPTION:
XS GIS Cut Line= 3
      2233287.71     13285396.83      2232887.72     13284396.85
      2232337.75     13283796.89
#Sta/Elev= 30
  3913.6  215.93  4060.3  211.03  4281.1  200.66  4312.1  200.85  4359.2  199.02
  4496.5  198.94  4581.3  197.29  4796.7  198.91  4915.2  196.22  4938.4  196.58
  4969.1  195.42  4987.9  191.62  4994.0  191.62  4994.7  189.83  4997.4  189.33
  5000.7  189.83  5054.4  196.52  5162.4  198.15  5351.6  200.17  5436.7  202.79
  5471.9  205.10  5500.2  205.40  5549.6  209.40  5585.3  210.31  5606.3  212.54
  5648.8  214.05  5712.4  218.22  5733.9  220.62  5769.1  221.48  5804.5  223.90
#Mann=5,-1,0
  3913.6    0.05       0  4938.4     0.1       0  4994.7    0.07       0
  5000.7     0.1       0  5162.4    0.05       0
Bank Sta=4994.7,5000.7
Exp/Cntr=0.3,0.1

Type RM Length L Ch R = 1,7973,430,430,430
BEGIN DESCRIPTION:
UNT018 IN SPCR 8.0
END DESCRIPTION:
XS GIS Cut Line= 3
      2234187.70     13285096.83      2233187.72     13284096.85
      2232587.72     13283596.86
#Sta/Elev= 30
  3616.2  228.08  3658.6  227.93  3743.4  225.44  3814.2  217.63  3870.7  215.76
  3885.2  214.36  4054.6  207.68  4238.4  202.72  4563.7  201.02  4719.3  198.29
  4761.7  195.63  4804.1  195.92  4832.4  194.94  4945.5  196.12  4959.7  195.80
  4992.5  189.65  4999.1  188.76  5001.8  188.26  5005.1  188.76  5026.8  192.81
  5078.5  194.55  5193.7  197.12  5335.6  196.59  5520.5  200.98  5619.4  206.62
  5641.5  209.03  5683.2  210.96  5697.5  212.94  5783.4  217.21  5811.4  219.60
#Mann=6,-1,0
  3616.2     0.1       0  3885.2    0.05       0  4992.5     0.1       0
  4999.1    0.07       0  5005.1     0.1       0  5078.5    0.05       0
Bank Sta=4999.1,5005.1
Exp/Cntr=0.3,0.1

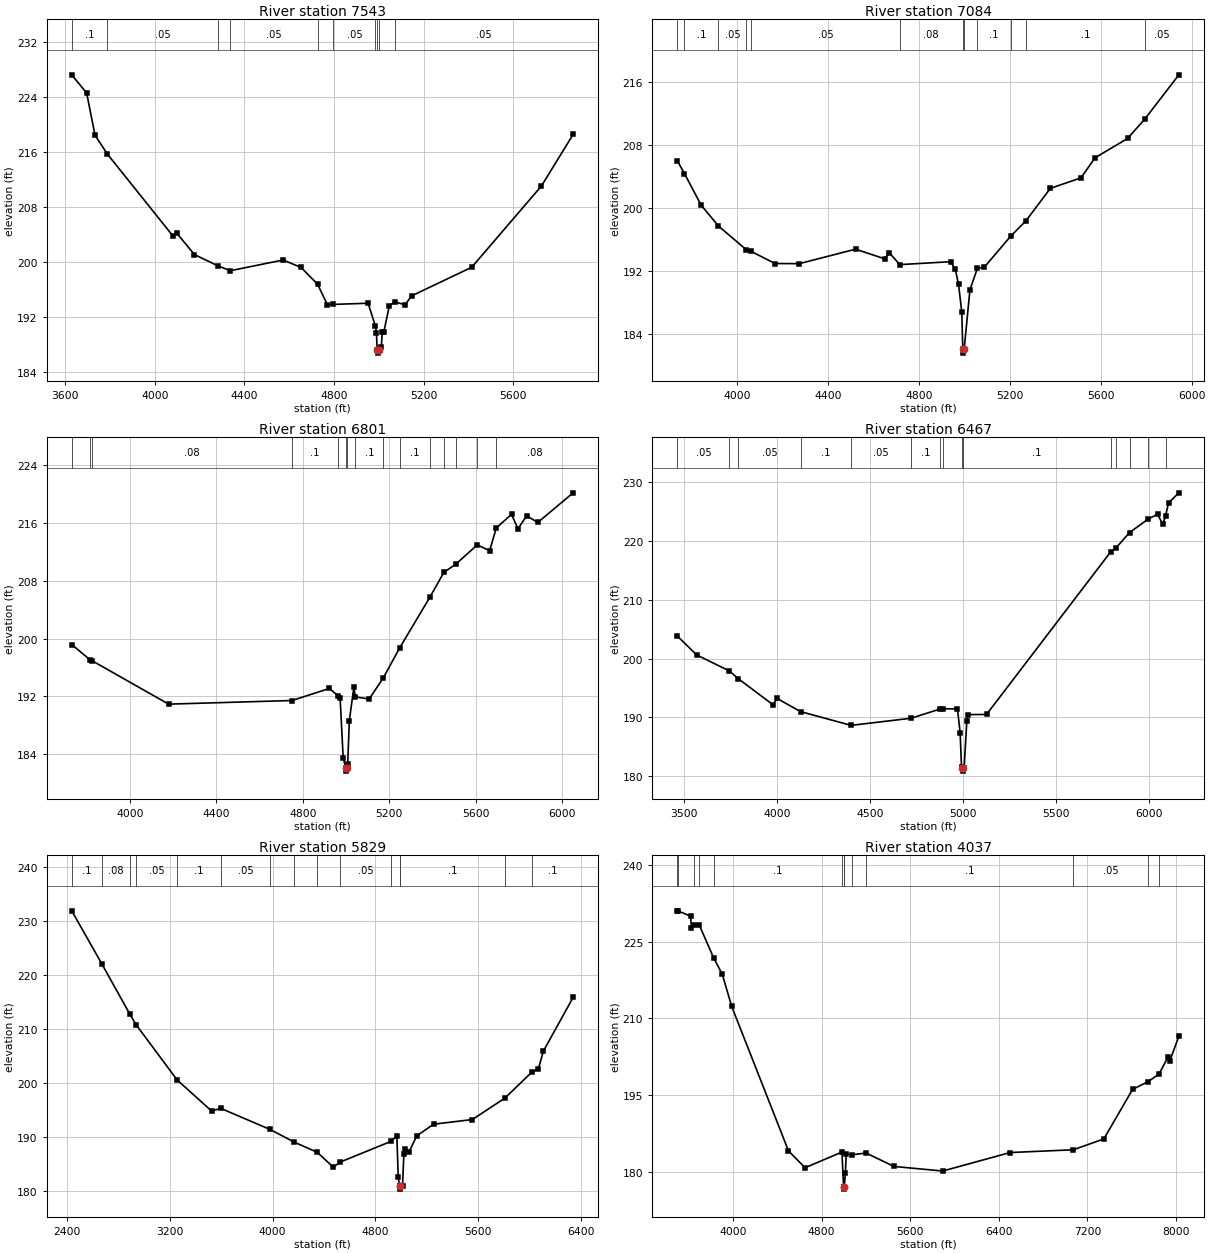
Type RM Length L Ch R = 1,7543,459,459,459
BEGIN DESCRIPTION:
UNT018 IN SPCR 7.0
END DESCRIPTION:
XS GIS Cut Line= 3
      2234187.72     13284996.85      2233487.72     13283796.85
      2232887.70     13283196.83
#Sta/Elev= 30
  3629.1  227.19  3695.7  224.55  3732.9  218.44  3787.5  215.72  4081.0  203.80
  4096.7  204.26  4176.9  201.11  4283.4  199.44  4337.1  198.77  4572.2  200.32
  4652.4  199.25  4726.5  196.80  4769.8  193.85  4796.5  193.88  4951.8  194.05
  4984.2  190.75  4989.0  189.77  4992.2  187.31  4994.9  186.81  4998.2  187.31
  5010.5  187.73  5015.4  189.87  5021.9  189.87  5046.6  193.69  5070.0  194.23
  5117.3  193.84  5145.6  195.11  5414.3  199.27  5725.4  211.06  5866.9  218.55
#Mann=10,-1,0
  3629.1     0.1       0  3787.5    0.05       0  4283.4     0.1       0
  4337.1    0.05       0  4726.5     0.1       0  4796.5    0.05       0
  4984.2     0.1       0  4992.2    0.07       0  4998.2     0.1       0
  5070.0    0.05       0
Bank Sta=4992.2,4998.2
Exp/Cntr=0.3,0.1

Type RM Length L Ch R = 1,7084,283,283,283
BEGIN DESCRIPTION:
Mapping XS e945033b
END DESCRIPTION:
XS GIS Cut Line= 3
      2234724.71     13284505.82      2233683.04     13283344.79
      2233075.36     13283127.76
#Sta/Elev= 30
  3738.8  205.91  3769.5  204.33  3842.4  200.33  3919.2  197.66  4042.2  194.63
  4061.5  194.46  4167.6  192.90  4274.5  192.88  4521.9  194.72  4649.7  193.50
  4670.7  194.26  4716.5  192.76  4939.8  193.13  4960.7  192.15  4974.9  190.26
  4989.1  186.74  4993.6  182.02  4996.3  181.52  4999.6  182.02  5025.0  189.55
  5057.7  192.29  5088.5  192.44  5204.0  196.36  5271.2  198.32  5378.6  202.44
  5513.4  203.78  5575.0  206.32  5718.3  208.78  5794.6  211.26  5943.9  216.86
#Mann=12,-1,0
  3738.8    0.05       0  3769.5     0.1       0  3919.2    0.05       0
  4042.2     0.1       0  4061.5    0.05       0  4716.5    0.08       0
  4993.6    0.07       0  4999.6    0.08       0  5057.7     0.1       0
  5204.0    0.08       0  5271.2     0.1       0  5794.6    0.05       0
Bank Sta=4993.6,4999.6
Exp/Cntr=0.3,0.1

Type RM Length L Ch R = 1,6801,334,334,334
BEGIN DESCRIPTION:
Mapping XS 462fbcfd
END DESCRIPTION:
XS GIS Cut Line= 3
      2234963.43     13284353.92      2233813.25     13283073.52
      2233227.33     13282954.17
#Sta/Elev= 30
  3731.5  199.18  3815.3  197.09  3824.4  196.96  4179.7  190.94  4750.3  191.44
  4923.4  193.11  4962.1  192.11  4972.8  191.79  4987.0  183.55  4998.2  182.18
  5000.9  181.68  5004.2  182.18  5007.9  182.64  5015.4  188.66  5036.3  193.25
  5043.2  191.94  5107.3  191.65  5172.4  194.56  5247.7  198.69  5388.7  205.75
  5452.5  209.15  5507.5  210.28  5607.1  212.95  5664.4  212.16  5695.0  215.29
  5765.6  217.18  5795.1  215.18  5835.9  216.97  5886.9  216.05  6050.6  220.15
#Mann=15,-1,0
  3731.5    0.08       0  3815.3    0.05       0  3824.4    0.08       0
  4750.3     0.1       0  4962.1    0.08       0  4998.2    0.07       0
  5004.2    0.08       0  5043.2     0.1       0  5172.4    0.08       0
  5247.7     0.1       0  5388.7    0.08       0  5452.5     0.1       0
  5507.5    0.08       0  5607.1     0.1       0  5695.0    0.08       0
Bank Sta=4998.2,5004.2
Exp/Cntr=0.3,0.1

Type RM Length L Ch R = 1,6467,638,638,638
BEGIN DESCRIPTION:
Mapping XS 44b390e4
END DESCRIPTION:
XS GIS Cut Line= 3
      2235516.82     13284223.71      2234171.32     13283019.27
      2233314.08     13282780.54
#Sta/Elev= 30
  3465.6  203.81  3569.2  200.62  3744.7  197.91  3791.5  196.61  3979.6  192.15
  4001.2  193.23  4127.4  190.99  4399.2  188.65  4721.2  189.86  4875.6  191.41
  4894.7  191.47  4971.0  191.46  4985.2  187.41  4992.7  181.64  4996.4  181.37
  4999.2  180.87  5002.4  181.37  5006.9  181.48  5021.1  189.35  5027.8  190.48
  5127.3  190.51  5795.1  218.17  5824.8  218.88  5896.2  221.44  5997.3  223.75
  6046.6  224.55  6074.5  222.85  6089.9  224.29  6105.6  226.48  6161.3  228.19
#Mann=15,-1,0
  3465.6    0.05       0  3744.7     0.1       0  3791.5    0.05       0
  4127.4     0.1       0  4399.2    0.05       0  4721.2     0.1       0
  4875.6    0.05       0  4894.7     0.1       0  4996.4    0.07       0
  5002.4     0.1       0  5795.1    0.08       0  5824.8     0.1       0
  5896.2    0.08       0  5997.3     0.1       0  6089.9    0.08       0
Bank Sta=4996.4,5002.4
Exp/Cntr=0.3,0.1

Type RM Length L Ch R = 1,5829,1792,1792,1792
BEGIN DESCRIPTION:
UNT018 IN SPCR 3.0
END DESCRIPTION:
XS GIS Cut Line= 3
      2236637.71     13284546.84      2234837.72     13282746.85
      2233487.69     13282596.85
#Sta/Elev= 30
  2436.1  231.93  2671.4  222.07  2888.3  212.81  2936.4  210.87  3257.2  200.61
  3525.0  194.87  3596.4  195.36  3980.0  191.46  4166.5  189.14  4348.2  187.21
  4472.5  184.48  4527.2  185.43  4920.8  189.24  4967.5  190.23  4978.1  182.70
  4988.7  180.91  4991.5  180.41  4994.7  180.91  5011.8  181.07  5021.9  186.92
  5032.0  187.88  5062.2  187.30  5122.5  190.27  5253.3  192.43  5555.2  193.29
  5808.6  197.26  6019.8  202.10  6068.3  202.61  6108.6  205.97  6340.0  215.91
#Mann=15,-1,0
  2436.1     0.1       0  2671.4    0.08       0  2888.3     0.1       0
  2936.4    0.05       0  3257.2     0.1       0  3596.4    0.05       0
  3980.0     0.1       0  4166.5    0.05       0  4348.2     0.1       0
  4527.2    0.05       0  4920.8     0.1       0  4988.7    0.07       0
  4994.7     0.1       0  5808.6    0.16       0  6019.8     0.1       0
Bank Sta=4988.7,4994.7
Exp/Cntr=0.3,0.1

Type RM Length L Ch R = 1,4037,2514,2514,2514
BEGIN DESCRIPTION:
UNT018 IN SPCR 2.0
END DESCRIPTION:
XS GIS Cut Line= 3
      2237399.67     13282911.30      2235848.04     13281717.74
      2233316.25     13282158.16
#Sta/Elev= 30
  3498.4  231.05  3501.6  231.05  3616.5  230.01  3624.7  227.61  3651.8  228.33
  3694.4  228.32  3823.8  221.90  3902.9  218.64  3988.1  212.34  4500.9  184.07
  4650.4  180.78  4983.6  183.84  4998.2  177.09  5000.9  176.59  5004.2  177.09
  5014.8  179.67  5022.0  183.47  5076.0  183.33  5202.3  183.65  5453.0  181.03
  5893.1  180.13  6501.8  183.75  7072.0  184.29  7348.2  186.41  7608.2  196.12
  7746.4  197.60  7846.5  199.11  7929.3  202.50  7943.1  201.63  8025.8  206.51
#Mann=13,-1,0
  3498.4     0.1       0  3501.6    0.08       0  3651.8     0.1       0
  3694.4    0.08       0  3823.8     0.1       0  4983.6    0.07       0
  4998.2    0.07       0  5004.2    0.07       0  5076.0    0.16       0
  5202.3     0.1       0  7072.0    0.05       0  7746.4    0.08       0
  7846.5     0.1       0
Bank Sta=4998.2,5004.2
Exp/Cntr=0.3,0.1