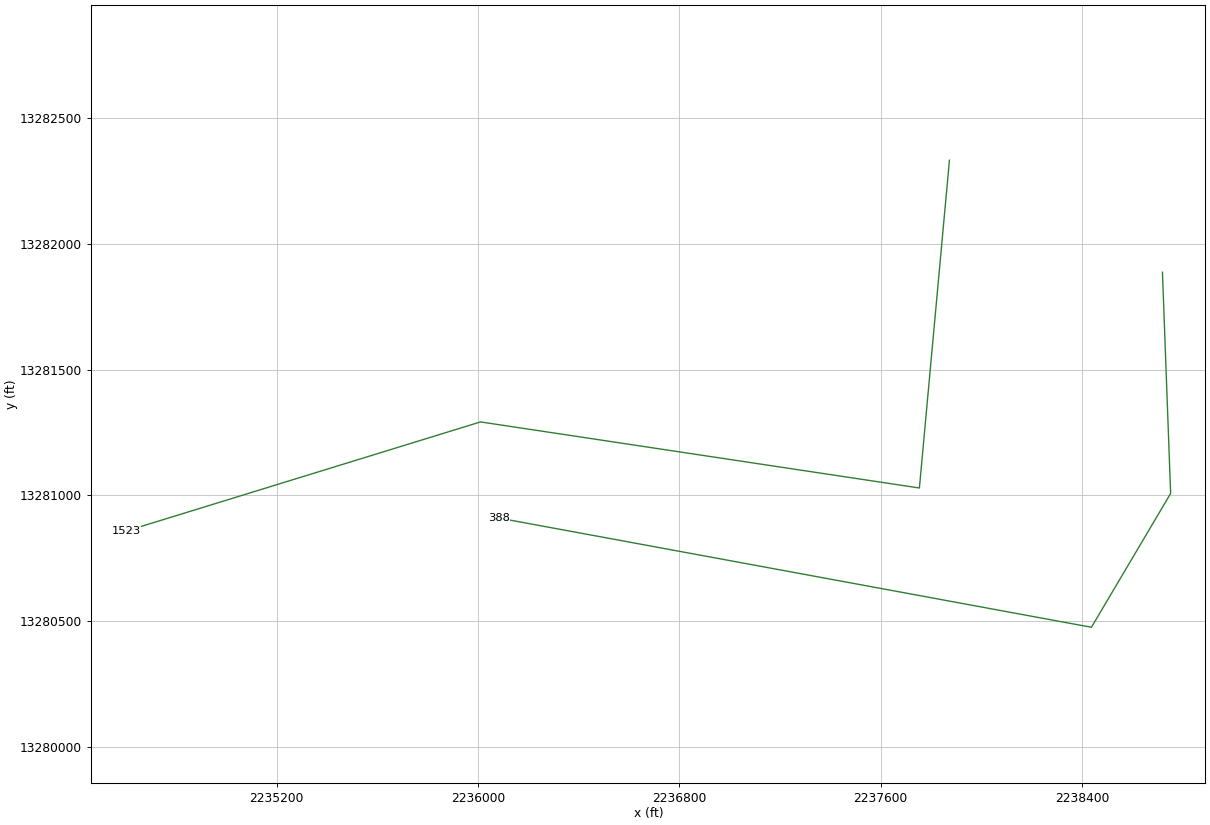
HEC-RAS study UNT018 IN SPCR.prj: UNT018 IN SPCR Base Level Engineering

--- UNT018 IN SPCR.g01 (geometry) --- (continued)

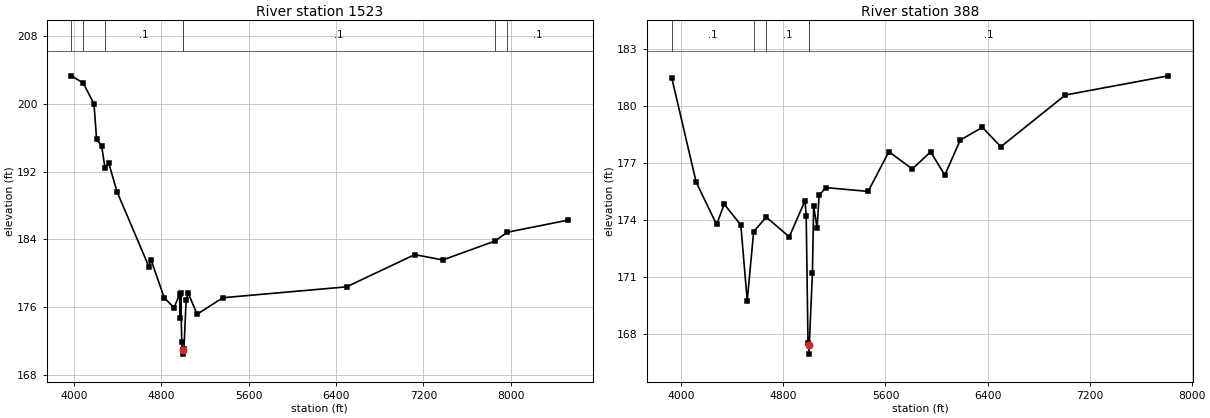
Type RM Length L Ch R = 1,1523,1135,1135,1135
BEGIN DESCRIPTION:
Mapping XS f36c3706
END DESCRIPTION:
XS GIS Cut Line= 4
      2237873.58     13282331.81      2237754.22     13281029.68
      2236010.36     13281292.20      2234602.13     13280858.47
#Sta/Elev= 30
  3978.5  203.33  4086.9  202.46  4184.3  200.01  4208.2  195.84  4254.6  195.04
  4285.7  192.38  4318.2  193.07  4395.2  189.62  4686.4  180.77  4706.5  181.56
  4827.0  177.09  4917.4  175.89  4967.6  177.51  4973.2  174.68  4978.2  177.60
  4987.7  171.79  4994.7  170.91  4997.5  170.41  5000.7  170.91  5007.7  171.02
  5027.8  176.81  5047.9  177.59  5128.3  175.13  5363.1  177.08  6496.1  178.37
  7119.5  182.18  7376.7  181.55  7854.9  183.79  7967.5  184.83  8523.1  186.26
#Mann=7,-1,0
  3978.5     0.1       0  4086.9    0.08       0  4285.7     0.1       0
  4994.7    0.07       0  5000.7     0.1       0  7854.9    0.05       0
  7967.5     0.1       0
Bank Sta=4994.7,5000.7
Exp/Cntr=0.3,0.1

Type RM Length L Ch R = 1,388,0,0,0
BEGIN DESCRIPTION:
UNT018 IN SPCR 1.0
END DESCRIPTION:
XS GIS Cut Line= 4
      2238719.93     13281886.91      2238752.48     13281007.98
      2238437.81     13280476.30      2236083.24     13280910.32
#Sta/Elev= 30
  3926.3  181.46  4116.5  176.00  4276.8  173.77  4336.6  174.84  4466.7  173.74
  4516.8  169.75  4567.0  173.39  4665.7  174.16  4846.2  173.12  4969.8  175.02
  4978.9  174.24  4993.1  167.53  4997.3  167.45  5000.0  166.95  5003.3  167.45
  5027.9  171.24  5037.4  174.73  5064.6  173.59  5080.2  175.30  5132.5  175.71
  5464.4  175.51  5627.1  177.60  5810.2  176.69  5954.2  177.59  6065.3  176.37
  6186.4  178.21  6359.3  178.88  6504.6  177.86  7010.0  180.58  7817.9  181.59
#Mann=5,-1,0
  3926.3     0.1       0  4567.0    0.08       0  4665.7     0.1       0
  4997.3    0.07       0  5003.3     0.1       0
Bank Sta=4997.3,5003.3
Exp/Cntr=0.3,0.1

Chan Stop Cuts=-1