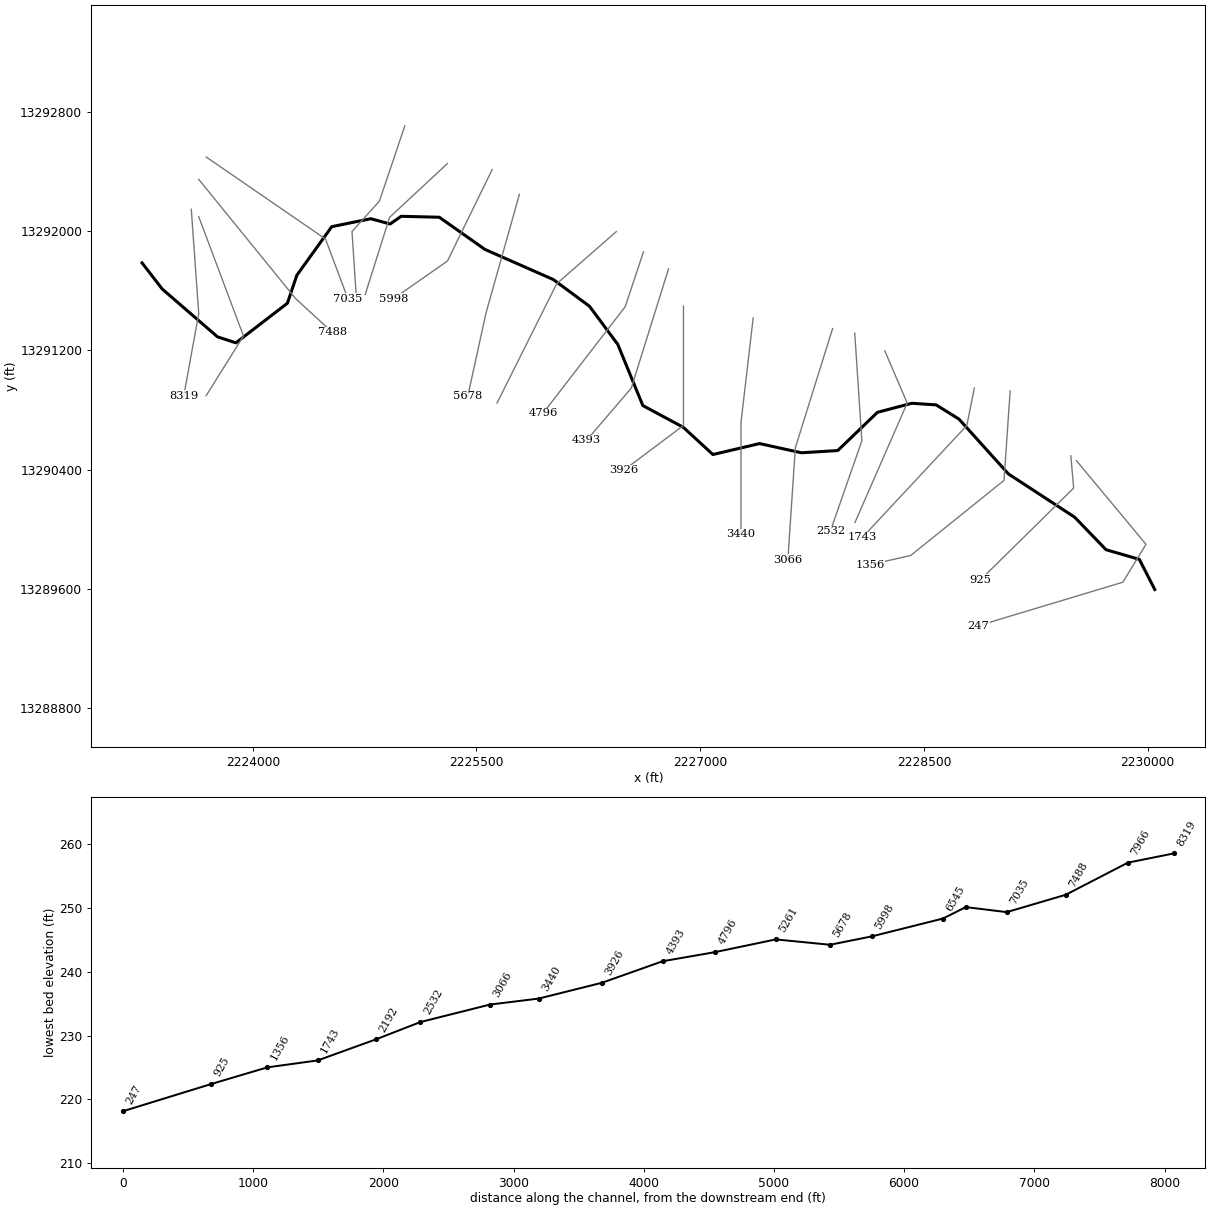
--- UNT019 IN SPCR.prj (project) ---

Proj Title=UNT019 IN SPCR Base Level Engineering
Current Plan=p01
Default Exp/Contr=0.3,0.1
English Units
Geom File=g01
Flow File=f01
Plan File=p01
BEGIN DESCRIPTION:
UNT019 IN SPCR
END DESCRIPTION:

--- UNT019 IN SPCR.p01 (plan) ---

Plan Title=Multiple Run
Short Identifier=Multiple
Geom File=g01
Flow File=f01
Subcritical Flow
K Sum by GR= 0
Std Step Tol= 0.01
Critical Tol= 0.01
Num of Std Step Trials= 20
Max Error Tol= 0.3
Flow Tol Ratio= 0.001
Split Flow NTrial= 30
Split Flow Tol= 0.02
Split Flow Ratio= 0.02
Log Output Level= 0
Friction Slope Method= 1
Unsteady Friction Slope Method= 2
Unsteady Bridges Friction Slope Method= 1
Parabolic Critical Depth
Global Vel Dist=  1 , 1 , 1
Global Log Level= 0
CheckData=True
Encroach Param= -1, 0, 0, 0
BEGIN DESCRIPTION:
Multiple Run
END DESCRIPTION:

--- UNT019 IN SPCR.f01 (steady flow) ---

Flow Title=Multiple
Number of Profiles=7
Profile Names=10-year,25-year,50-year,1pct_min,100-year,1pct_plu,500-year
River Rch & RM= UNT019 IN SPCR,Reach-1,8319
     349     495     618     568     768    1039    1206
Boundary for River Rch & Prof#=UNT019 IN SPCR,Reach-1,1
Up Type=0
Dn Type=3
Dn Slope=0.005
Boundary for River Rch & Prof#=UNT019 IN SPCR,Reach-1,2
Up Type=0
Dn Type=3
Dn Slope=0.005
Boundary for River Rch & Prof#=UNT019 IN SPCR,Reach-1,3
Up Type=0
Dn Type=3
Dn Slope=0.005
Boundary for River Rch & Prof#=UNT019 IN SPCR,Reach-1,4
Up Type=0
Dn Type=3
Dn Slope=0.005
Boundary for River Rch & Prof#=UNT019 IN SPCR,Reach-1,5
Up Type=0
Dn Type=3
Dn Slope=0.005
Boundary for River Rch & Prof#=UNT019 IN SPCR,Reach-1,6
Up Type=0
Dn Type=3
Dn Slope=0.005
Boundary for River Rch & Prof#=UNT019 IN SPCR,Reach-1,7
Up Type=0
Dn Type=3
Dn Slope=0.005

--- UNT019 IN SPCR.g01 (geometry) ---

Geom Title=Existing Conditions

River Reach=UNT019 IN SPCR,Reach-1
Reach XY= 30
      2223257.72     13291786.85      2223392.99     13291611.52
      2223763.71     13291291.02      2223887.01     13291250.75
      2224232.31     13291516.49      2224295.51     13291703.99
      2224529.53     13292029.68      2224791.55     13292083.13
      2224920.84     13292047.65      2224994.67     13292099.11
      2225250.79     13292092.88      2225556.48     13291877.23
      2226015.16     13291675.15      2226257.56     13291496.22
      2226447.38     13291240.38      2226615.28     13290830.37
      2226886.73     13290684.47      2227085.20     13290501.98
      2227398.17     13290575.40      2227677.99     13290513.79
      2227922.08     13290528.53      2228188.47     13290785.03
      2228418.31     13290845.61      2228581.77     13290834.79
      2228735.08     13290739.38      2229066.10     13290372.10
      2229510.57     13290081.79      2229721.23     13289863.72
      2229944.10     13289799.23      2230047.72     13289596.86

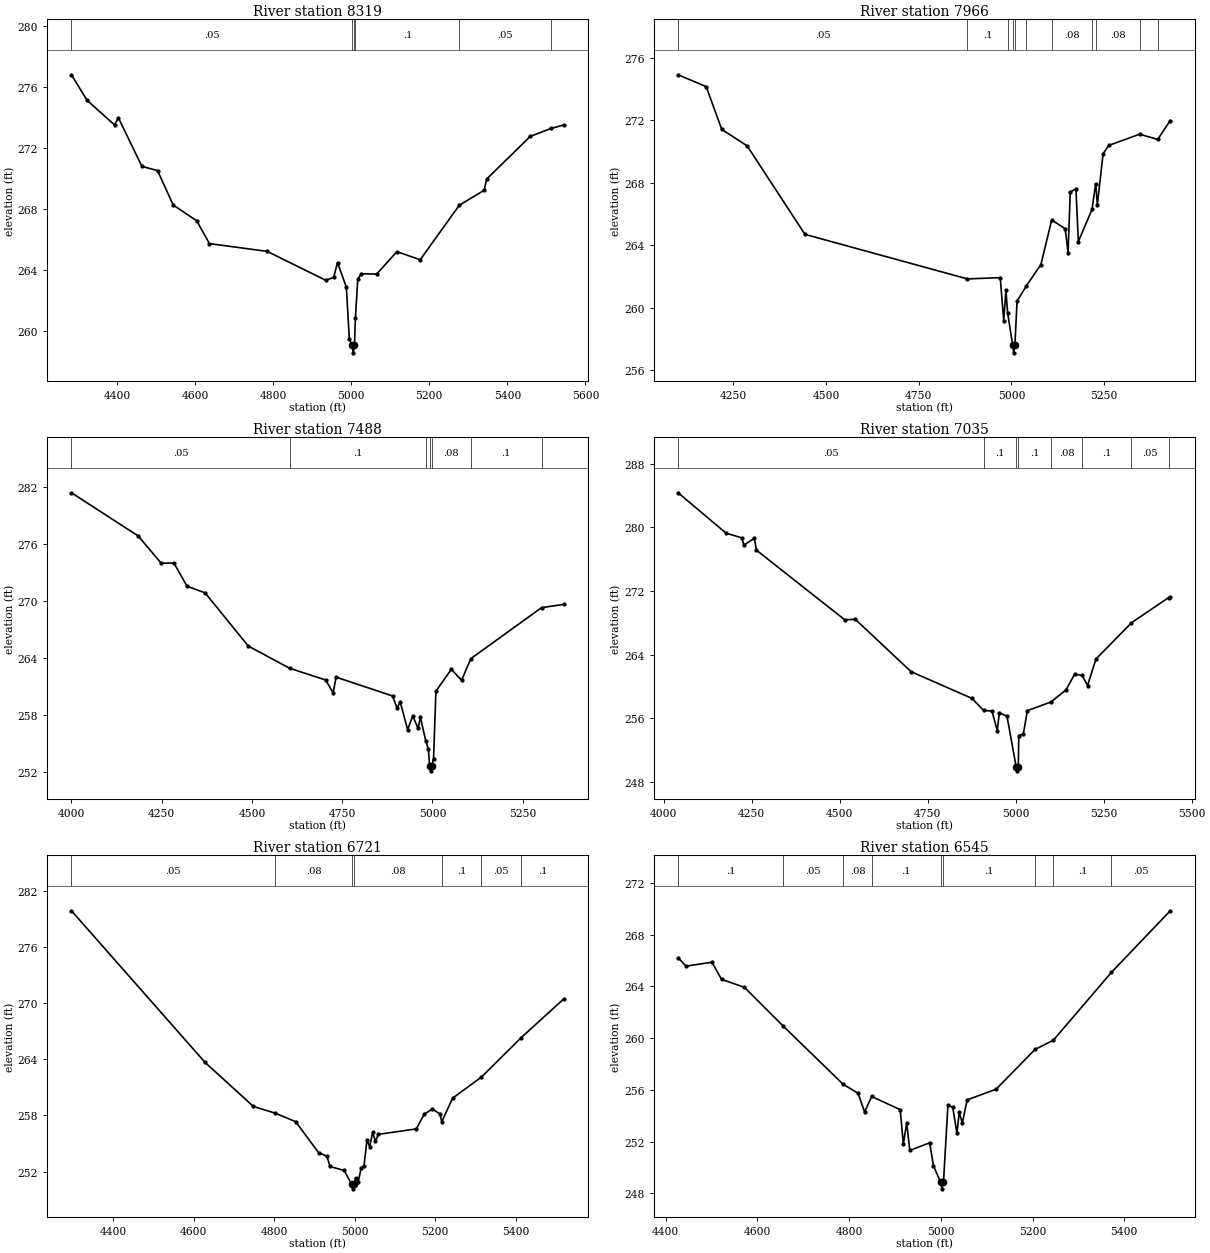
Type RM Length L Ch R = 1,8319,353,353,353
BEGIN DESCRIPTION:
UNT019 IN SPCR 17.0
END DESCRIPTION:
XS GIS Cut Line= 3
      2223587.72     13292146.86      2223637.72     13291446.85
      2223537.72     13290896.86
#Sta/Elev= 30
  4283.2  276.82  4323.3  275.14  4393.5  273.53  4403.5  273.99  4463.7  270.81
  4503.8  270.53  4543.9  268.27  4604.0  267.24  4636.6  265.74  4784.5  265.23
  4934.9  263.33  4954.9  263.52  4964.9  264.49  4987.5  262.88  4995.2  259.46
  5002.3  259.07  5005.1  258.57  5008.3  259.07  5010.7  260.86  5016.7  263.39
  5025.6  263.76  5065.0  263.74  5117.1  265.21  5176.8  264.68  5276.9  268.26
  5340.7  269.24  5347.1  269.98  5458.9  272.78  5512.4  273.30  5544.0  273.52
#Mann=6,-1,0
  4283.2    0.05       0  5002.3    0.03       0  5008.3    0.05       0
  5010.7     0.1       0  5276.9    0.05       0  5512.4    0.08       0
Bank Sta=5002.3,5008.3
Exp/Cntr=0.3,0.1

Type RM Length L Ch R = 1,7966,478,478,478
BEGIN DESCRIPTION:
UNT019 IN SPCR 16.0
END DESCRIPTION:
XS GIS Cut Line= 3
      2223637.71     13292096.87      2223937.72     13291296.85
      2223687.73     13290896.87
#Sta/Elev= 30
  4101.7  274.91  4177.4  274.15  4219.2  271.42  4287.7  270.36  4443.5  264.70
  4881.2  261.85  4969.7  261.93  4979.1  259.18  4985.0  261.12  4989.6  259.68
  5003.2  257.62  5006.0  257.12  5009.2  257.62  5015.1  260.43  5040.3  261.41
  5079.3  262.77  5108.3  265.62  5144.8  265.06  5152.5  263.53  5158.4  267.40
  5173.7  267.62  5180.2  264.24  5217.1  266.30  5226.9  267.94  5231.5  266.60
  5246.8  269.85  5262.1  270.39  5345.6  271.11  5393.9  270.77  5427.8  271.98
#Mann=11,-1,0
  4101.7    0.05       0  4881.2     0.1       0  4989.6    0.08       0
  5003.2    0.07       0  5009.2    0.08       0  5040.3     0.1       0
  5108.3    0.08       0  5217.1    0.05       0  5226.9    0.08       0
  5345.6    0.05       0  5393.9    0.08       0
Bank Sta=5003.2,5009.2
Exp/Cntr=0.3,0.1

Type RM Length L Ch R = 1,7488,453,453,453
BEGIN DESCRIPTION:
UNT019 IN SPCR 15.0
END DESCRIPTION:
XS GIS Cut Line= 3
      2223637.70     13292346.88      2224287.72     13291546.85
      2224532.45     13291322.52
#Sta/Elev= 30
  4000.3  281.37  4184.9  276.83  4248.9  273.95  4284.0  273.97  4320.7  271.52
  4370.3  270.83  4490.2  265.22  4604.8  262.88  4704.3  261.65  4725.1  260.28
  4733.0  261.95  4889.4  259.97  4902.5  258.67  4910.4  259.38  4931.3  256.43
  4945.6  257.87  4960.0  256.55  4966.7  257.71  4981.4  255.26  4988.7  254.37
  4992.2  252.58  4994.9  252.08  4998.2  252.58  5003.1  253.36  5009.6  260.47
  5052.4  262.77  5080.7  261.62  5106.4  263.90  5302.2  269.27  5363.1  269.61
#Mann=7,-1,0
  4000.3    0.05       0  4604.8     0.1       0  4981.4    0.08       0
  4992.2    0.07       0  4998.2    0.08       0  5106.4     0.1       0
  5302.2    0.05       0
Bank Sta=4992.2,4998.2
Exp/Cntr=0.3,0.1

Type RM Length L Ch R = 1,7035,314,314,314
BEGIN DESCRIPTION:
UNT019 IN SPCR 14.0
END DESCRIPTION:
XS GIS Cut Line= 3
      2223687.72     13292496.85      2224487.72     13291946.85
      2224637.71     13291546.88
#Sta/Elev= 30
  4041.1  284.37  4177.1  279.29  4221.7  278.70  4227.8  277.78  4257.6  278.64
  4263.7  277.14  4514.7  268.37  4544.4  268.44  4702.7  261.85  4876.0  258.48
  4908.8  256.97  4932.8  256.88  4947.7  254.42  4953.7  256.69  4975.5  256.21
  5001.5  249.86  5004.2  249.36  5007.5  249.86  5008.9  253.80  5021.7  253.98
  5033.3  256.94  5100.3  258.03  5142.8  259.54  5167.7  261.54  5188.8  261.37
  5204.2  260.10  5228.2  263.44  5329.0  268.00  5434.7  271.18  5439.1  271.27
#Mann=8,-1,0
  4041.1    0.05       0  4908.8     0.1       0  5001.5    0.07       0
  5007.5     0.1       0  5100.3    0.08       0  5188.8     0.1       0
  5329.0    0.05       0  5434.7     0.1       0
Bank Sta=5001.5,5007.5
Exp/Cntr=0.3,0.1

Type RM Length L Ch R = 1,6721,176,176,176
BEGIN DESCRIPTION:
Mapping XS 025b9e05
END DESCRIPTION:
XS GIS Cut Line= 4
      2225019.42     13292705.09      2224849.20     13292201.23
      2224665.34     13291996.95      2224692.57     13291581.71
#Sta/Elev= 30
  4295.9  279.84  4627.9  263.65  4747.9  258.95  4802.3  258.23  4853.1  257.32
  4909.9  254.02  4930.8  253.63  4938.3  252.54  4973.4  252.11  4992.1  250.65
  4994.8  250.15  4998.1  250.65  5001.8  251.27  5008.6  250.93  5016.0  252.39
  5022.8  252.57  5030.2  255.35  5037.0  254.67  5044.4  256.18  5051.2  255.24
  5058.6  255.97  5152.8  256.55  5172.8  258.14  5192.9  258.67  5211.6  258.14
  5216.1  257.31  5243.0  259.83  5314.8  262.09  5413.6  266.30  5518.7  270.41
#Mann=7,-1,0
  4295.9    0.05       0  4802.3    0.08       0  4992.1    0.07       0
  4998.1    0.08       0  5216.1     0.1       0  5314.8    0.05       0
  5413.6     0.1       0
Bank Sta=4992.1,4998.1
Exp/Cntr=0.3,0.1

Type RM Length L Ch R = 1,6545,547,547,547
BEGIN DESCRIPTION:
UNT019 IN SPCR 13.0
END DESCRIPTION:
XS GIS Cut Line= 3
      2225305.40     13292453.15      2224917.30     13292092.28
      2224753.86     13291574.73
#Sta/Elev= 30
  4427.5  266.22  4444.5  265.57  4501.1  265.87  4522.1  264.55  4572.0  263.93
  4656.6  260.93  4787.1  256.44  4819.7  255.74  4833.9  254.30  4849.5  255.49
  4911.6  254.47  4918.4  251.82  4925.7  253.43  4932.6  251.32  4975.8  251.91
  4984.1  250.13  4999.9  248.85  5002.6  248.35  5005.9  248.85  5015.6  254.81
  5026.1  254.66  5035.2  252.65  5040.4  254.26  5047.0  253.43  5057.5  255.23
  5120.4  256.05  5205.6  259.13  5245.4  259.84  5371.8  265.08  5500.2  269.85
#Mann=9,-1,0
  4427.5     0.1       0  4656.6    0.05       0  4787.1    0.08       0
  4849.5     0.1       0  4999.9    0.07       0  5005.9     0.1       0
  5205.6    0.05       0  5245.4     0.1       0  5371.8    0.05       0
Bank Sta=4999.9,5005.9
Exp/Cntr=0.3,0.1

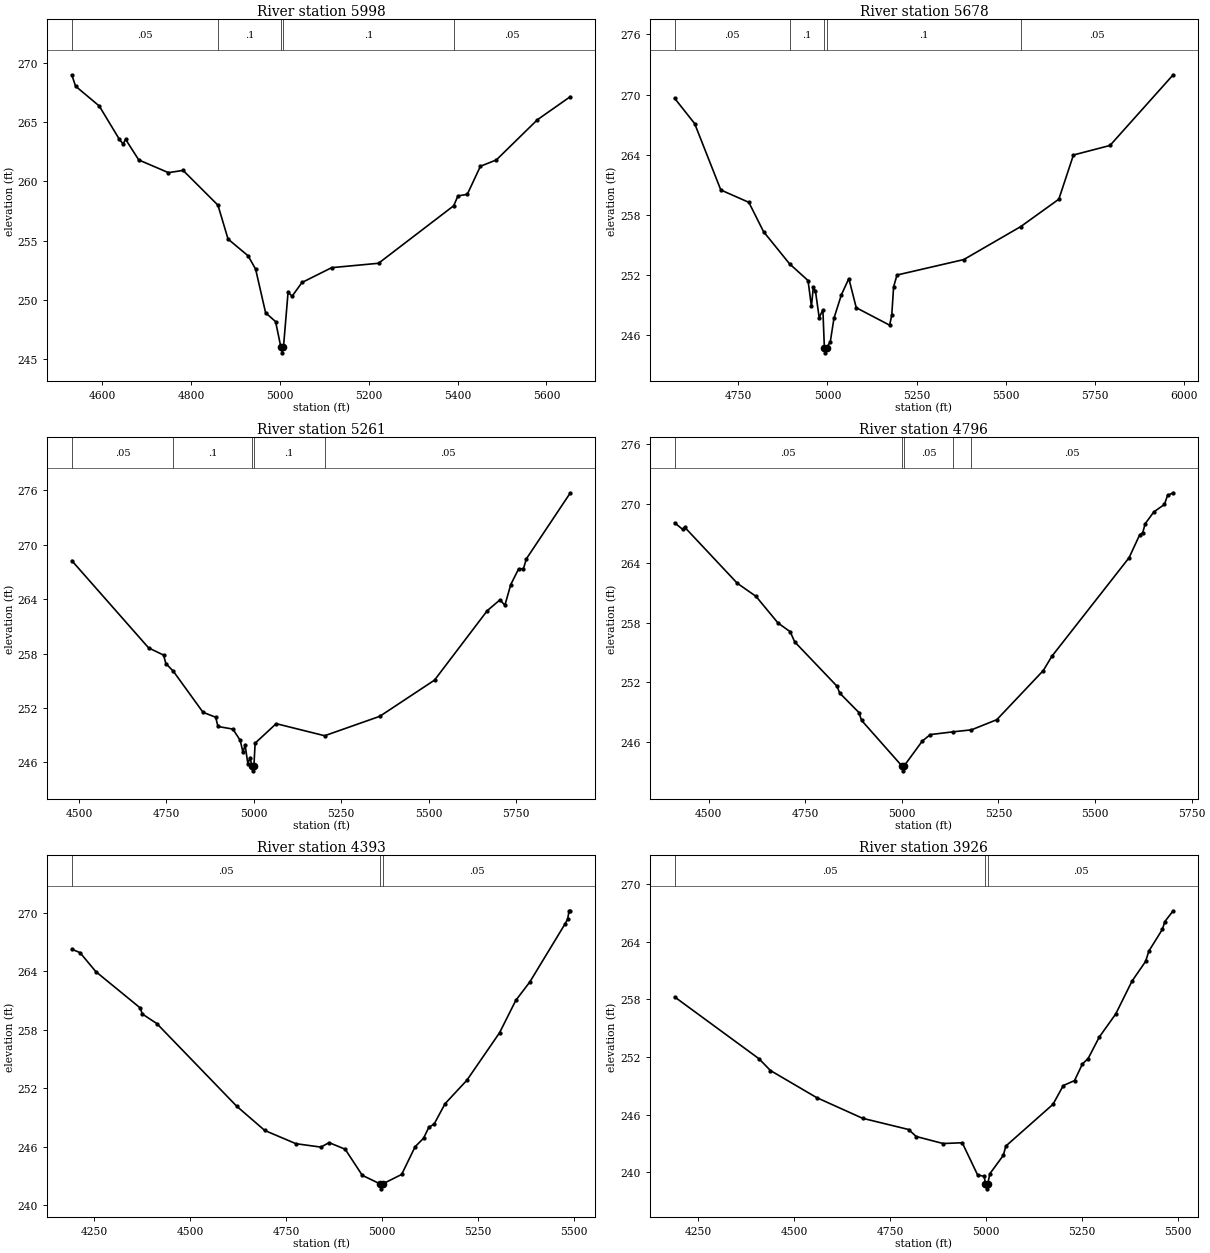
Type RM Length L Ch R = 1,5998,320,320,320
BEGIN DESCRIPTION:
UNT019 IN SPCR 12.0
END DESCRIPTION:
XS GIS Cut Line= 3
      2225605.08     13292412.37      2225305.44     13291799.47
      2224944.51     13291547.50
#Sta/Elev= 30
  4531.4  268.99  4539.9  268.03  4593.2  266.36  4637.7  263.60  4646.9  263.15
  4652.5  263.55  4682.2  261.81  4749.0  260.74  4782.0  260.93  4860.4  258.00
  4883.2  255.14  4928.3  253.73  4945.2  252.61  4967.7  248.93  4990.2  248.18
  5002.0  246.05  5004.8  245.55  5008.0  246.05  5018.3  250.67  5027.3  250.32
  5049.6  251.48  5116.4  252.73  5221.9  253.10  5391.2  257.95  5400.7  258.78
  5421.7  258.91  5451.3  261.28  5487.1  261.81  5579.6  265.20  5653.8  267.15
#Mann=5,-1,0
  4531.4    0.05       0  4860.4     0.1       0  5002.0    0.07       0
  5008.0     0.1       0  5391.2    0.05       0
Bank Sta=5002,5008
Exp/Cntr=0.3,0.1

Type RM Length L Ch R = 1,5678,417,417,417
BEGIN DESCRIPTION:
UNT019 IN SPCR 11.0
END DESCRIPTION:
XS GIS Cut Line= 3
      2225787.71     13292246.82      2225564.20     13291452.19
      2225441.64     13290893.85
#Sta/Elev= 30
  4571.8  269.63  4628.0  267.10  4701.3  260.48  4779.8  259.25  4821.1  256.32
  4894.1  253.11  4945.7  251.45  4955.2  248.87  4960.4  250.76  4966.5  250.40
  4976.9  247.76  4987.3  248.52  4991.5  244.74  4994.2  244.24  4997.5  244.74
  5008.1  245.35  5018.4  247.70  5039.2  250.03  5060.0  251.65  5080.8  248.74
  5174.3  247.00  5180.3  248.00  5185.5  250.83  5195.0  252.00  5382.0  253.54
  5541.7  256.83  5648.4  259.56  5689.4  263.97  5791.8  264.92  5968.9  271.97
#Mann=5,-1,0
  4571.8    0.05       0  4894.1     0.1       0  4991.5    0.07       0
  4997.5     0.1       0  5541.7    0.05       0
Bank Sta=4991.5,4997.5
Exp/Cntr=0.3,0.1

Type RM Length L Ch R = 1,5261,465,465,465
BEGIN DESCRIPTION:
UNT019 IN SPCR 10.0
END DESCRIPTION:
XS GIS Cut Line= 3
      2226437.75     13291996.88      2226037.72     13291646.85
      2225637.71     13290846.83
#Sta/Elev= 30
  4479.4  268.25  4699.2  258.63  4741.9  257.84  4748.5  256.91  4770.0  256.05
  4854.8  251.53  4890.9  250.99  4897.5  249.97  4940.2  249.68  4961.1  248.44
  4968.7  247.18  4975.3  247.88  4982.9  245.88  4989.6  246.55  4994.2  245.58
  4996.9  245.08  5000.2  245.58  5003.8  248.13  5064.0  250.28  5202.6  248.95
  5360.3  251.09  5516.9  255.08  5667.8  262.74  5704.1  263.93  5718.1  263.33
  5734.9  265.61  5757.2  267.33  5771.2  267.37  5779.6  268.45  5905.4  275.73
#Mann=5,-1,0
  4479.4    0.05       0  4770.0     0.1       0  4994.2    0.07       0
  5000.2     0.1       0  5202.6    0.05       0
Bank Sta=4994.2,5000.2
Exp/Cntr=0.3,0.1

Type RM Length L Ch R = 1,4796,403,403,403
BEGIN DESCRIPTION:
UNT019 IN SPCR 9.0
END DESCRIPTION:
XS GIS Cut Line= 3
      2226619.67     13291860.73      2226497.11     13291493.04
      2225945.54     13290778.05
#Sta/Elev= 30
  4411.6  268.07  4432.5  267.40  4437.8  267.62  4573.8  261.98  4622.3  260.66
  4679.2  257.98  4710.8  257.10  4722.4  256.08  4832.3  251.60  4838.8  250.93
  4888.7  248.96  4895.4  248.18  4999.8  243.59  5002.5  243.09  5005.8  243.59
  5052.6  246.08  5073.4  246.74  5132.8  247.02  5180.1  247.22  5245.6  248.24
  5366.0  253.19  5388.0  254.62  5588.0  264.55  5615.3  266.84  5623.3  267.07
  5629.6  267.97  5652.3  269.17  5679.4  269.91  5687.6  270.82  5702.2  271.09
#Mann=5,-1,0
  4411.6    0.05       0  4999.8   0.035       0  5005.8    0.05       0
  5132.8     0.1       0  5180.1    0.05       0
Bank Sta=4999.8,5005.8
Exp/Cntr=0.3,0.1

Type RM Length L Ch R = 1,4393,467,467,467
BEGIN DESCRIPTION:
UNT019 IN SPCR 8.0
END DESCRIPTION:
XS GIS Cut Line= 3
      2226787.71     13291746.81      2226537.72     13290946.85
      2226237.71     13290596.84
#Sta/Elev= 30
  4191.1  266.29  4212.5  265.94  4253.9  263.98  4369.2  260.26  4374.9  259.63
  4412.6  258.65  4620.6  250.16  4693.9  247.66  4775.1  246.30  4840.1  245.95
  4861.6  246.41  4903.5  245.73  4948.0  243.05  4994.8  242.16  4997.5  241.66
  5000.8  242.16  5050.6  243.14  5085.7  245.99  5107.7  246.86  5121.4  247.99
  5135.1  248.31  5163.7  250.41  5220.7  252.83  5305.8  257.71  5348.0  261.03
  5384.3  262.91  5476.5  268.90  5483.0  269.38  5486.9  270.24  5490.2  270.24
#Mann=3,-1,0
  4191.1    0.05       0  4994.8   0.035       0  5000.8    0.05       0
Bank Sta=4994.8,5000.8
Exp/Cntr=0.3,0.1

Type RM Length L Ch R = 1,3926,486,486,486
BEGIN DESCRIPTION:
UNT019 IN SPCR 7.0
END DESCRIPTION:
XS GIS Cut Line= 3
      2226887.72     13291496.86      2226887.72     13290696.85
      2226487.72     13290396.86
#Sta/Elev= 30
  4188.4  258.27  4408.4  251.83  4438.4  250.60  4558.4  247.79  4678.4  245.63
  4798.4  244.46  4818.4  243.73  4888.4  243.00  4938.4  243.08  4978.4  239.73
  4995.7  239.58  4998.9  238.78  5001.7  238.28  5004.9  238.78  5010.3  239.85
  5045.7  241.78  5051.9  242.73  5174.9  247.08  5201.9  249.04  5231.1  249.55
  5251.9  251.30  5266.5  251.84  5295.7  254.09  5338.4  256.48  5381.1  259.92
  5416.5  261.97  5424.9  263.04  5460.3  265.31  5466.5  266.11  5488.4  267.24
#Mann=3,-1,0
  4188.4    0.05       0  4998.9   0.035       0  5004.9    0.05       0
Bank Sta=4998.9,5004.9
Exp/Cntr=0.3,0.1

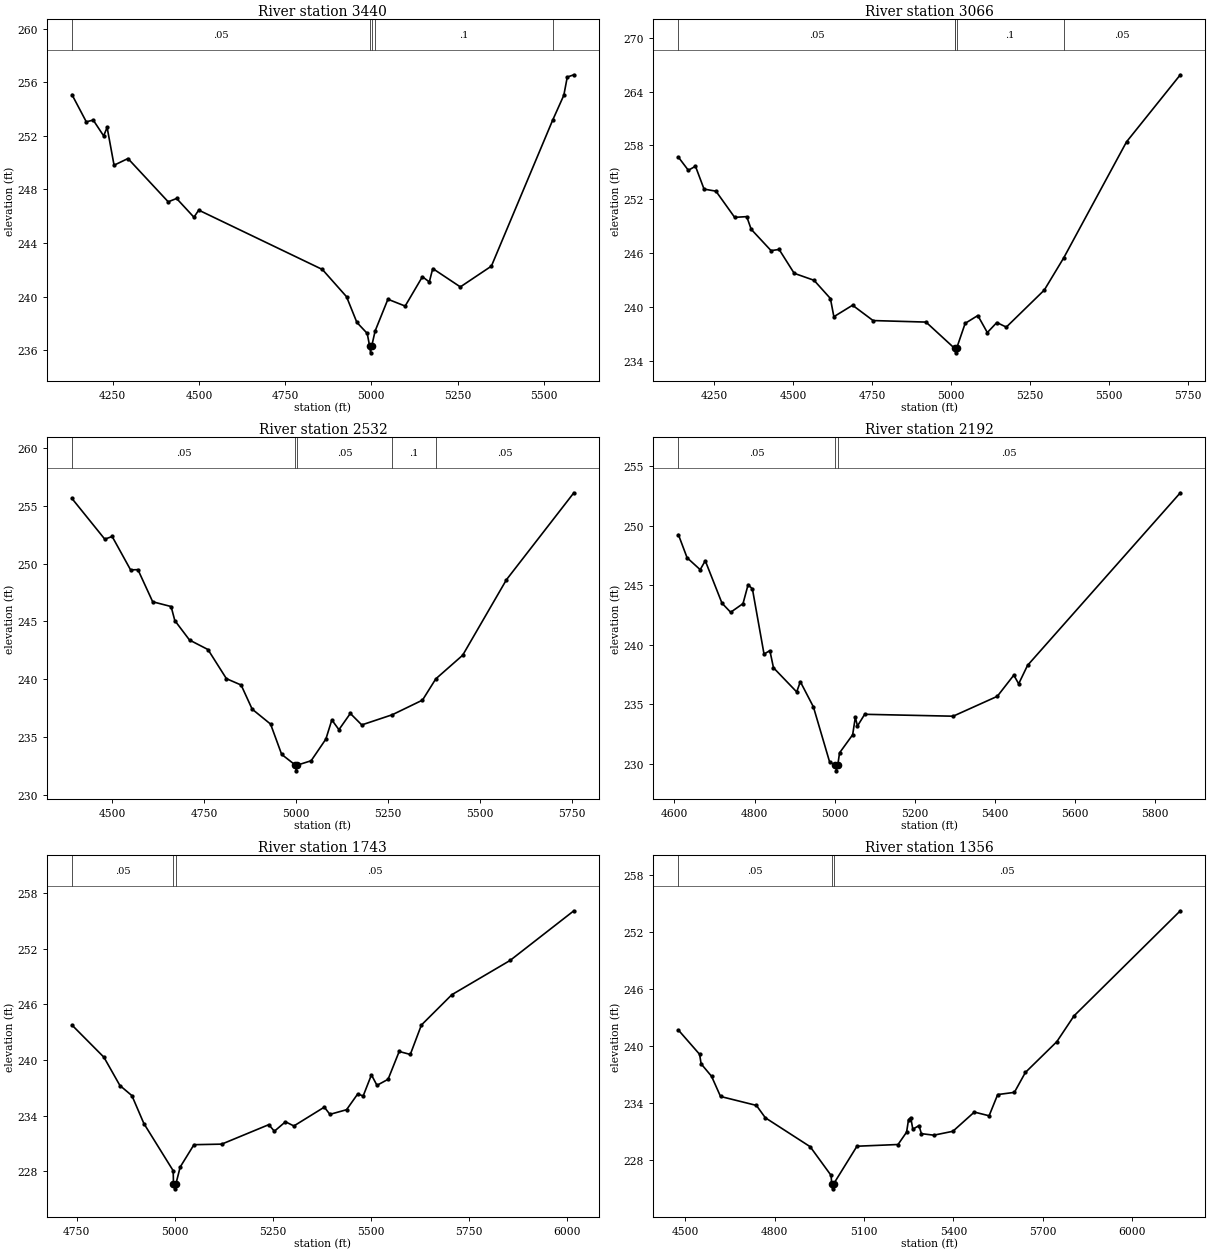
Type RM Length L Ch R = 1,3440,374,374,374
BEGIN DESCRIPTION:
UNT019 IN SPCR 6.0
END DESCRIPTION:
XS GIS Cut Line= 3
      2227355.11     13291418.18      2227273.39     13290716.76
      2227273.39     13289967.73
#Sta/Elev= 30
  4131.9  255.07  4173.5  253.04  4193.6  253.17  4223.8  251.99  4233.9  252.62
  4254.0  249.80  4294.3  250.30  4411.0  247.07  4435.3  247.32  4485.6  245.92
  4499.5  246.45  4858.0  242.02  4928.0  239.99  4958.0  238.07  4988.0  237.25
  4995.0  236.30  4997.7  235.80  5001.0  236.30  5010.9  237.43  5048.0  239.80
  5098.0  239.29  5148.0  241.48  5168.0  241.09  5178.0  242.09  5258.0  240.72
  5348.0  242.27  5525.6  253.16  5558.0  255.02  5568.0  256.38  5587.1  256.55
#Mann=5,-1,0
  4131.9    0.05       0  4995.0   0.035       0  5001.0    0.05       0
  5010.9     0.1       0  5525.6    0.05       0
Bank Sta=4995,5001
Exp/Cntr=0.3,0.1

Type RM Length L Ch R = 1,3066,534,534,534
BEGIN DESCRIPTION:
UNT019 IN SPCR 5.0
END DESCRIPTION:
XS GIS Cut Line= 3
      2227887.72     13291346.86      2227637.72     13290546.85
      2227587.72     13289796.88
#Sta/Elev= 30
  4136.7  256.68  4168.1  255.22  4190.7  255.67  4217.9  253.12  4255.6  252.89
  4314.8  249.97  4353.1  250.05  4367.2  248.64  4430.1  246.26  4455.7  246.39
  4503.4  243.73  4566.3  242.95  4618.1  240.92  4629.1  238.89  4688.3  240.17
  4753.3  238.46  4920.9  238.29  5011.5  235.36  5011.9  235.36  5014.7  234.86
  5017.9  235.36  5045.0  238.15  5085.1  239.02  5115.2  237.12  5145.2  238.24
  5175.3  237.73  5295.6  241.86  5357.3  245.46  5556.1  258.39  5726.5  265.87
#Mann=5,-1,0
  4136.7    0.05       0  5011.5     0.1       0  5011.9   0.035       0
  5017.9     0.1       0  5357.3    0.05       0
Bank Sta=5011.9,5017.9
Exp/Cntr=0.3,0.1

Type RM Length L Ch R = 1,2532,340,340,340
BEGIN DESCRIPTION:
UNT019 IN SPCR 4.0
END DESCRIPTION:
XS GIS Cut Line= 3
      2228036.06     13291316.01      2228083.73     13290594.19
      2227872.62     13289988.10
#Sta/Elev= 30
  4390.3  255.61  4479.6  252.10  4499.7  252.33  4549.8  249.45  4569.8  249.47
  4609.9  246.70  4660.0  246.29  4670.1  245.08  4710.1  243.40  4760.3  242.58
  4810.4  240.07  4850.5  239.52  4880.5  237.44  4930.6  236.15  4960.7  233.54
  4997.8  232.62  5000.5  232.12  5003.8  232.62  5040.9  232.99  5081.0  234.86
  5097.2  236.51  5116.5  235.67  5147.5  237.07  5178.6  236.08  5261.8  236.96
  5343.8  238.22  5379.9  240.05  5453.1  242.09  5572.1  248.60  5755.5  256.10
#Mann=5,-1,0
  4390.3    0.05       0  4997.8   0.035       0  5003.8    0.05       0
  5261.8     0.1       0  5379.9    0.05       0
Bank Sta=4997.8,5003.8
Exp/Cntr=0.3,0.1

Type RM Length L Ch R = 1,2192,449,449,449
BEGIN DESCRIPTION:
UNT019 IN SPCR 3.0
END DESCRIPTION:
XS GIS Cut Line= 3
      2228237.73     13291196.84      2228387.72     13290846.85
      2228037.71     13290046.84
#Sta/Elev= 30
  4609.8  249.26  4631.5  247.32  4664.2  246.32  4676.9  247.07  4718.6  243.51
  4740.3  242.74  4771.2  243.47  4783.9  245.06  4794.7  244.70  4823.7  239.23
  4838.3  239.52  4847.3  238.08  4905.3  236.05  4914.4  236.91  4947.1  234.79
  4987.8  230.14  5002.0  229.92  5004.7  229.42  5008.0  229.92  5012.4  230.93
  5045.1  232.45  5051.8  233.91  5057.2  233.19  5075.2  234.17  5296.2  234.01
  5406.5  235.68  5447.8  237.46  5459.9  236.73  5482.1  238.28  5863.8  252.78
#Mann=3,-1,0
  4609.8    0.05       0  5002.0   0.035       0  5008.0    0.05       0
Bank Sta=5002,5008
Exp/Cntr=0.3,0.1

Type RM Length L Ch R = 1,1743,387,387,387
BEGIN DESCRIPTION:
UNT019 IN SPCR 2.0
END DESCRIPTION:
XS GIS Cut Line= 3
      2228837.73     13290946.89      2228787.72     13290696.85
      2228087.72     13289946.86
#Sta/Elev= 30
  4737.8  243.76  4819.4  240.29  4860.2  237.24  4890.8  236.15  4921.4  233.14
  4996.2  228.05  4996.9  226.60  4999.6  226.10  5002.9  226.60  5014.0  228.45
  5049.2  230.86  5120.0  230.92  5240.2  233.02  5254.4  232.31  5282.7  233.33
  5304.2  232.88  5381.9  234.91  5396.1  234.13  5438.6  234.63  5466.9  236.32
  5481.1  236.12  5502.1  238.39  5516.2  237.26  5544.6  237.91  5572.9  240.91
  5601.3  240.59  5629.6  243.76  5707.3  247.03  5855.8  250.72  6018.7  256.08
#Mann=3,-1,0
  4737.8    0.05       0  4996.9   0.035       0  5002.9    0.05       0
Bank Sta=4996.9,5002.9
Exp/Cntr=0.3,0.1

Type RM Length L Ch R = 1,1356,431,431,431
BEGIN DESCRIPTION:
Mapping XS be4647f3
END DESCRIPTION:
XS GIS Cut Line= 4
      2229077.91     13290927.82      2229037.06     13290328.61
      2228410.58     13289824.71      2228138.18     13289763.42
#Sta/Elev= 30
  4477.5  241.70  4548.6  239.15  4553.7  238.15  4588.7  236.84  4618.8  234.72
  4739.1  233.78  4769.1  232.48  4919.5  229.44  4989.7  226.42  4991.8  225.51
  4994.5  225.01  4997.8  225.51  5076.5  229.49  5214.3  229.67  5243.0  230.97
  5249.5  232.29  5256.9  232.50  5263.9  231.28  5284.7  231.66  5292.6  230.81
  5334.3  230.65  5398.3  231.06  5470.2  233.08  5519.8  232.69  5548.6  234.92
  5604.6  235.15  5641.4  237.24  5747.0  240.48  5804.6  243.19  6161.3  254.24
#Mann=3,-1,0
  4477.5    0.05       0  4991.8   0.035       0  4997.8    0.05       0
Bank Sta=4991.8,4997.8
Exp/Cntr=0.3,0.1

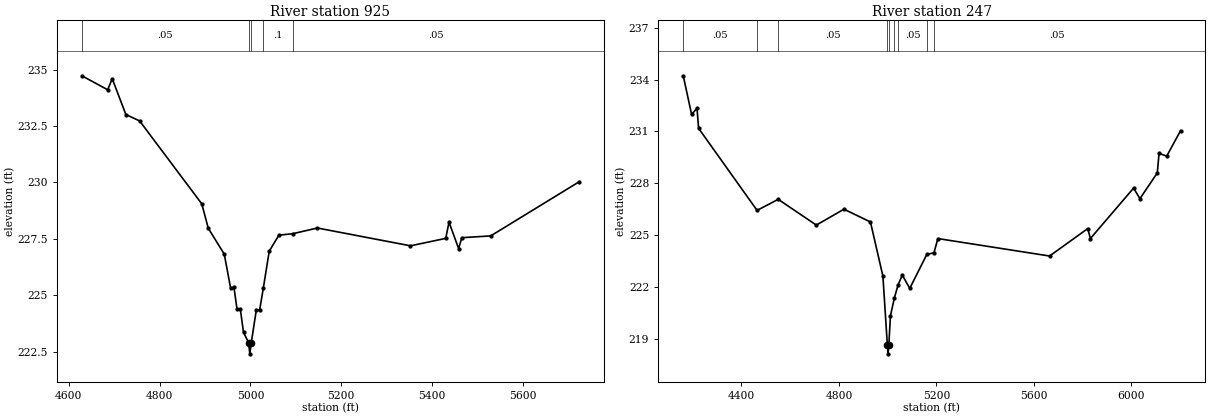
Type RM Length L Ch R = 1,925,678,678,678
BEGIN DESCRIPTION:
Mapping XS 58095755
END DESCRIPTION:
XS GIS Cut Line= 3
      2229484.92     13290493.53      2229503.76     13290276.88
      2228878.35     13289660.88
#Sta/Elev= 30
  4628.6  234.73  4685.5  234.11  4695.5  234.60  4725.6  233.01  4755.8  232.73
  4892.8  229.05  4907.0  227.97  4942.3  226.82  4956.4  225.30  4963.5  225.36
  4970.5  224.37  4977.7  224.37  4984.7  223.35  4995.8  222.90  4998.6  222.40
  5001.8  222.90  5013.0  224.36  5020.1  224.33  5028.2  225.30  5041.3  226.95
  5062.5  227.66  5093.8  227.73  5147.4  227.98  5352.4  227.19  5430.1  227.52
  5437.3  228.24  5458.4  227.07  5465.6  227.55  5529.2  227.63  5723.9  230.03
#Mann=5,-1,0
  4628.6    0.05       0  4995.8    0.03       0  5001.8    0.05       0
  5028.2     0.1       0  5093.8    0.05       0
Bank Sta=4995.8,5001.8
Exp/Cntr=0.3,0.1

Type RM Length L Ch R = 1,247,0,0,0
BEGIN DESCRIPTION:
UNT019 IN SPCR 1.0
END DESCRIPTION:
XS GIS Cut Line= 4
      2229522.63     13290460.51      2229988.84     13289900.11
      2229833.43     13289645.80      2228863.24     13289353.80
#Sta/Elev= 30
  4161.2  234.22  4195.5  231.98  4217.7  232.34  4224.2  231.18  4464.1  226.43
  4550.8  227.07  4707.2  225.58  4820.5  226.50  4929.2  225.76  4980.3  222.63
  4998.6  218.63  5001.3  218.13  5004.6  218.63  5011.2  220.33  5027.4  221.37
  5042.5  222.11  5059.6  222.69  5090.5  221.92  5160.4  223.88  5189.8  223.98
  5205.9  224.80  5664.1  223.79  5820.8  225.38  5831.4  224.80  6008.7  227.72
  6034.8  227.11  6106.0  228.60  6113.2  229.73  6144.5  229.57  6201.4  231.04
#Mann=9,-1,0
  4161.2    0.05       0  4464.1     0.1       0  4550.8    0.05       0
  4998.6    0.03       0  5004.6    0.05       0  5027.4     0.1       0
  5042.5    0.05       0  5160.4     0.1       0  5189.8    0.05       0
Bank Sta=4998.6,5004.6
Exp/Cntr=0.3,0.1

Chan Stop Cuts=-1