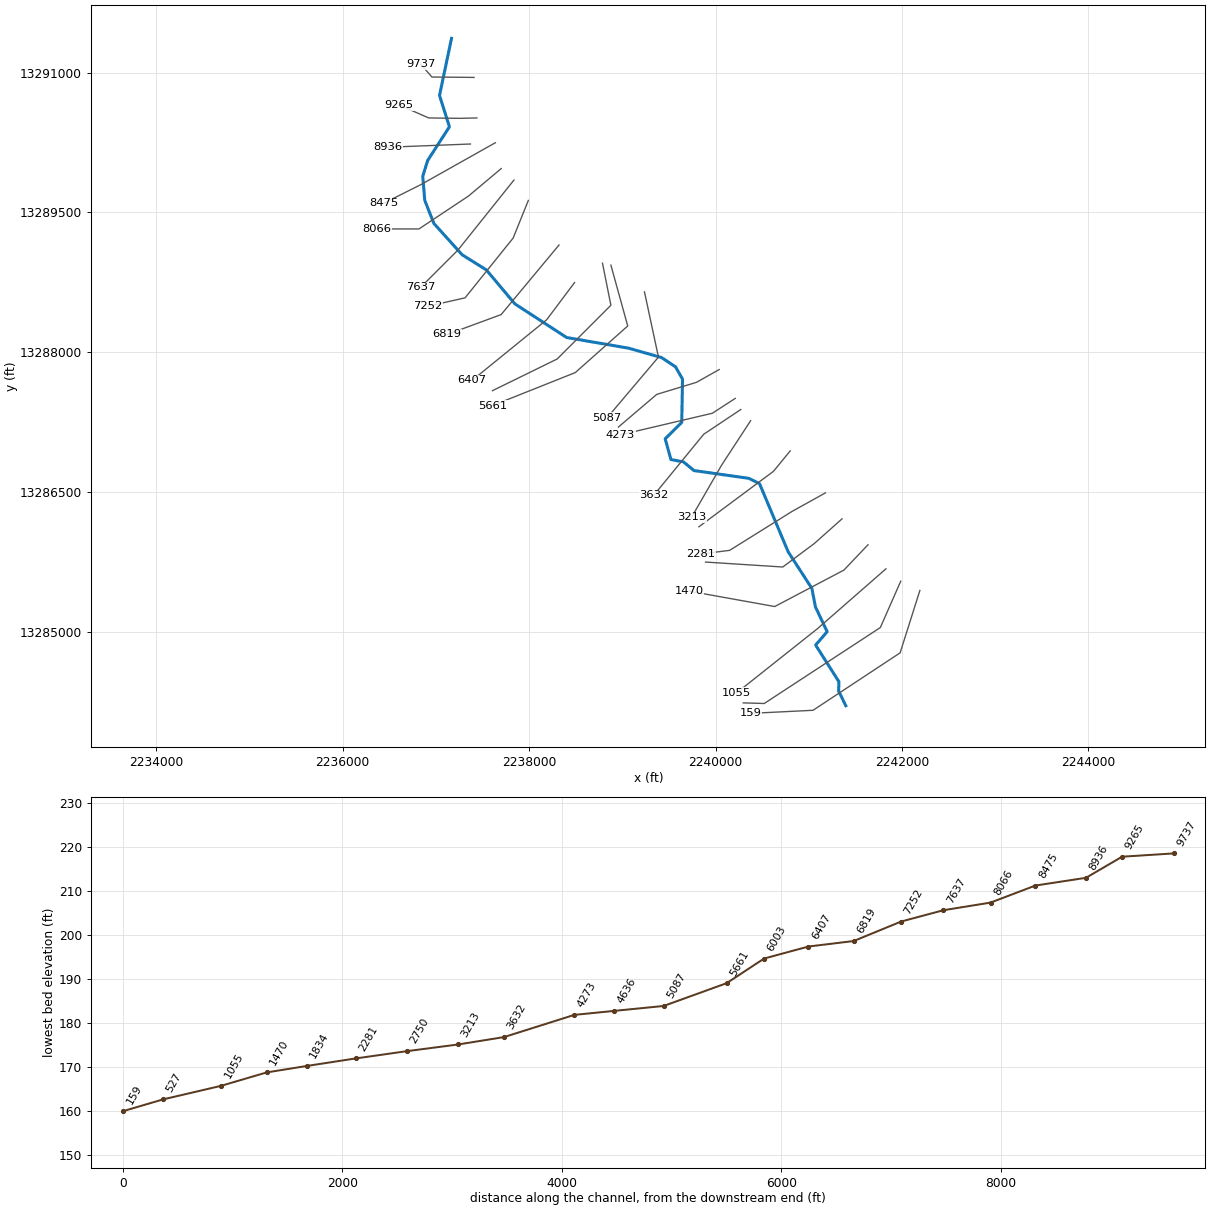
--- UNT020 IN SPCR.prj (project) ---

Proj Title=UNT020 IN SPCR Base Level Engineering
Current Plan=p01
Default Exp/Contr=0.3,0.1
English Units
Geom File=g01
Flow File=f01
Plan File=p01
Y Axis Title=Elevation
X Axis Title(PF)=Main Channel Distance
X Axis Title(XS)=Station
BEGIN DESCRIPTION:
UNT020 IN SPCR
END DESCRIPTION:
DSS Export Rating Curves= 0
DSS Export Rating Curve Sorted= 0
DSS Export Volume Flow Curves= 0
DXF OffsetX= 0
DXF OffsetY= 0
DXF ScaleX= 1
DXF ScaleY= 10

--- UNT020 IN SPCR.p01 (plan) ---

Plan Title=Multiple Run
Short Identifier=Multiple
Geom File=g01
Flow File=f01
Subcritical Flow
K Sum by GR= 0
Std Step Tol= 0.01
Critical Tol= 0.01
Num of Std Step Trials= 20
Max Error Tol= 0.3
Flow Tol Ratio= 0.001
Split Flow NTrial= 30
Split Flow Tol= 0.02
Split Flow Ratio= 0.02
Log Output Level= 0
Friction Slope Method= 1
Unsteady Friction Slope Method= 2
Unsteady Bridges Friction Slope Method= 1
Parabolic Critical Depth
Global Vel Dist=  1 , 1 , 1
Global Log Level= 0
CheckData=True
Encroach Param= -1, 0, 0, 0
BEGIN DESCRIPTION:
Multiple Run
END DESCRIPTION:

--- UNT020 IN SPCR.f01 (steady flow) ---

Flow Title=Multiple
Number of Profiles=7
Profile Names=10-year,25-year,50-year,1pct_min,100-year,1pct_plu,500-year
River Rch & RM= UNT020 IN SPCR,Reach-1,9737
     222     309     381     347     469     634     721
River Rch & RM= UNT020 IN SPCR,Reach-1,8475
     332     473     592     546     738     998    1164
River Rch & RM= UNT020 IN SPCR,Reach-1,5661
     409     585     736     681     921    1245    1463
Boundary for River Rch & Prof#=UNT020 IN SPCR,Reach-1,1
Up Type=0
Dn Type=3
Dn Slope=0.005
Boundary for River Rch & Prof#=UNT020 IN SPCR,Reach-1,2
Up Type=0
Dn Type=3
Dn Slope=0.005
Boundary for River Rch & Prof#=UNT020 IN SPCR,Reach-1,3
Up Type=0
Dn Type=3
Dn Slope=0.005
Boundary for River Rch & Prof#=UNT020 IN SPCR,Reach-1,4
Up Type=0
Dn Type=3
Dn Slope=0.005
Boundary for River Rch & Prof#=UNT020 IN SPCR,Reach-1,5
Up Type=0
Dn Type=3
Dn Slope=0.005
Boundary for River Rch & Prof#=UNT020 IN SPCR,Reach-1,6
Up Type=0
Dn Type=3
Dn Slope=0.005
Boundary for River Rch & Prof#=UNT020 IN SPCR,Reach-1,7
Up Type=0
Dn Type=3
Dn Slope=0.005

--- UNT020 IN SPCR.g01 (geometry) ---

Geom Title=Existing Conditions

River Reach=UNT020 IN SPCR,Reach-1
Reach XY= 30
      2237167.72     13291366.86      2237038.78     13290754.77
      2237145.11     13290418.18      2236911.61     13290056.22
      2236858.88     13289886.67      2236880.70     13289628.09
      2236978.71     13289380.60      2237281.79     13289044.69
      2237540.71     13288883.05      2237847.42     13288517.98
      2238403.00     13288157.01      2239066.51     13288043.05
      2239420.39     13287942.14      2239570.14     13287843.18
      2239645.87     13287711.26      2239637.74     13287246.40
      2239459.80     13287070.54      2239521.51     13286848.13
      2239656.18     13286823.35      2239768.91     13286729.72
      2240357.46     13286646.27      2240472.28     13286589.25
      2240779.53     13285857.60      2241033.92     13285465.28
      2241071.26     13285268.39      2241197.57     13285001.45
      2241073.99     13284857.69      2241323.87     13284464.60
      2241320.57     13284364.53      2241397.72     13284206.85

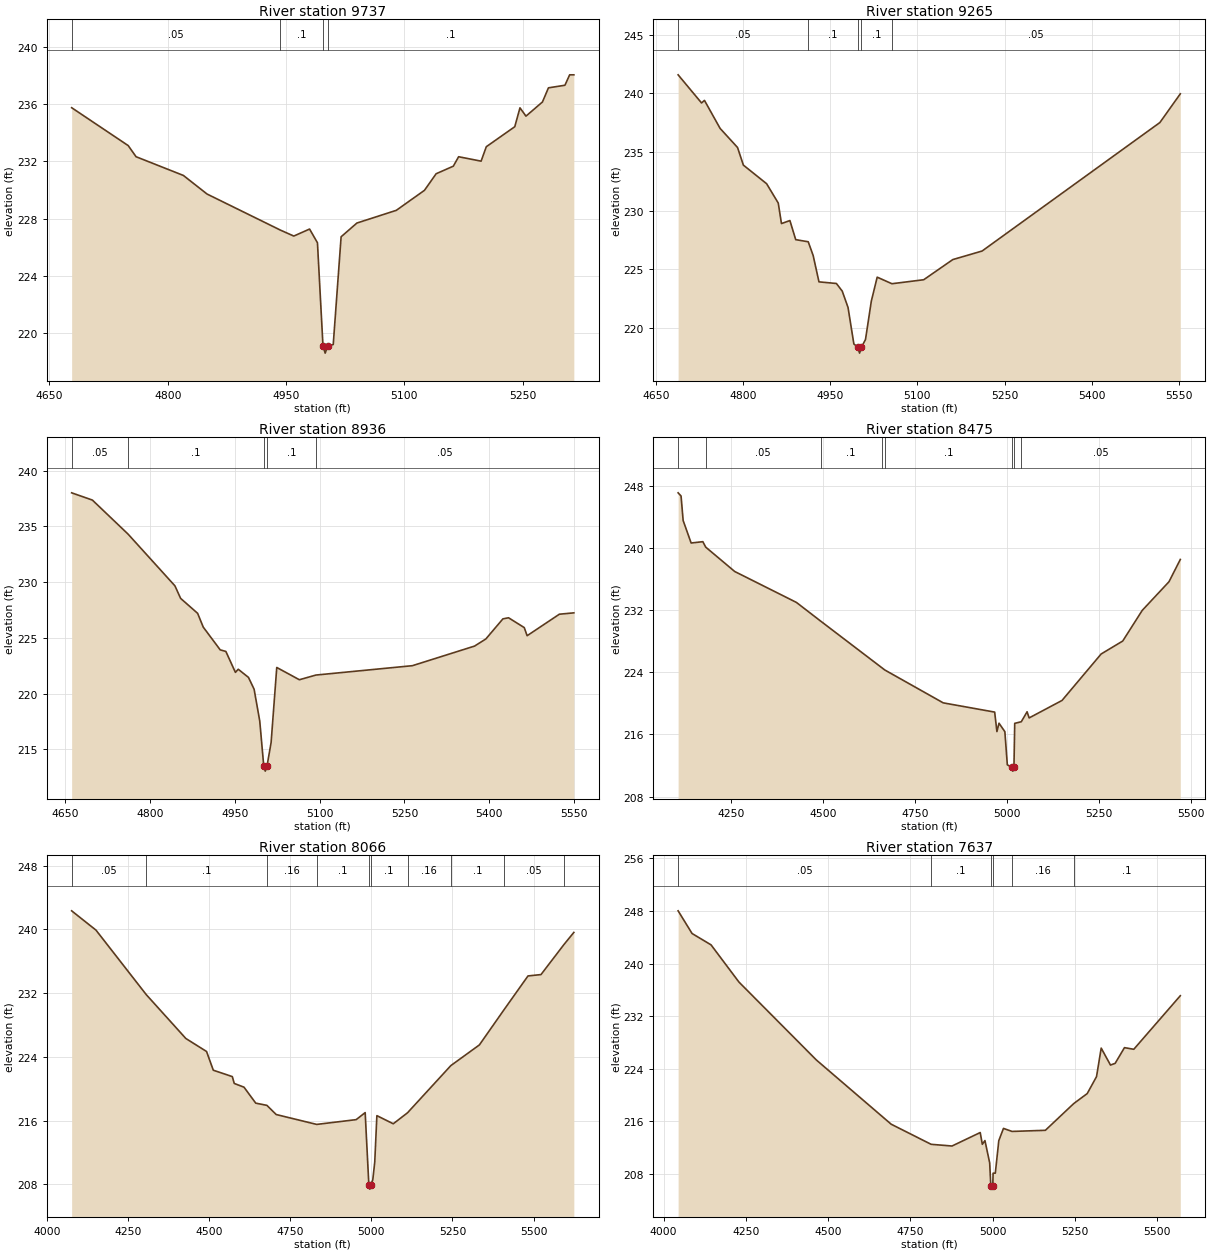
Type RM Length L Ch R = 1,9737,472,472,472
BEGIN DESCRIPTION:
UNT020 IN SPCR 22.0
END DESCRIPTION:
XS GIS Cut Line= 3
      2237409.44     13290947.55      2236957.47     13290951.89
      2236835.77     13291090.97
#Sta/Elev= 30
  4678.1  235.76  4749.8  233.11  4759.8  232.33  4819.8  231.02  4849.8  229.72
  4942.7  227.20  4959.8  226.78  4979.8  227.27  4989.8  226.31  4996.8  219.09
  4999.6  218.59  5002.8  219.09  5009.8  219.19  5019.8  226.73  5039.8  227.69
  5089.8  228.58  5125.5  229.98  5140.3  231.14  5162.1  231.67  5168.8  232.33
  5197.3  232.02  5203.9  233.03  5240.0  234.43  5246.6  235.75  5254.2  235.17
  5275.1  236.16  5282.7  237.15  5303.6  237.33  5309.6  238.06  5314.9  238.06
#Mann=4,-1,0
  4678.1    0.05       0  4942.7     0.1       0  4996.8    0.07       0
  5002.8     0.1       0
Bank Sta=4996.8,5002.8
Exp/Cntr=0.3,0.1

Type RM Length L Ch R = 1,9265,329,329,329
BEGIN DESCRIPTION:
UNT020 IN SPCR 21.0
END DESCRIPTION:
XS GIS Cut Line= 4
      2237439.90     13290512.91      2237261.71     13290508.57
      2236922.70     13290512.91      2236605.61     13290651.91
#Sta/Elev= 30
  4688.5  241.58  4728.8  239.18  4733.8  239.40  4760.7  237.01  4790.7  235.38
  4800.7  233.88  4840.7  232.29  4860.7  230.64  4866.2  228.89  4880.7  229.15
  4890.7  227.52  4912.2  227.34  4920.7  226.17  4930.7  223.92  4960.7  223.78
  4970.7  223.13  4980.7  221.73  4990.7  218.62  4997.7  218.34  5000.5  217.84
  5003.7  218.34  5010.7  219.00  5020.7  222.27  5030.8  224.32  5056.1  223.76
  5110.8  224.10  5160.8  225.82  5211.2  226.55  5516.9  237.51  5552.0  239.96
#Mann=5,-1,0
  4688.5    0.05       0  4912.2     0.1       0  4997.7    0.07       0
  5003.7     0.1       0  5056.1    0.05       0
Bank Sta=4997.7,5003.7
Exp/Cntr=0.3,0.1

Type RM Length L Ch R = 1,8936,461,461,461
BEGIN DESCRIPTION:
UNT020 IN SPCR 20.0
END DESCRIPTION:
XS GIS Cut Line= 2
      2237370.51     13290233.24      2236482.19     13290198.54
#Sta/Elev= 30
  4660.9  238.01  4697.6  237.36  4760.9  234.30  4843.8  229.66  4853.8  228.54
  4883.9  227.20  4893.9  225.96  4923.9  223.92  4933.9  223.78  4950.8  221.90
  4955.8  222.18  4973.9  221.45  4983.9  220.39  4993.9  217.53  5000.9  213.54
  5003.7  213.04  5006.9  213.54  5014.0  215.61  5024.0  222.34  5064.0  221.24
  5093.3  221.66  5264.1  222.50  5374.2  224.26  5394.2  224.90  5424.3  226.70
  5434.3  226.80  5462.1  225.92  5467.2  225.19  5524.3  227.12  5549.9  227.24
#Mann=5,-1,0
  4660.9    0.05       0  4760.9     0.1       0  5000.9    0.07       0
  5006.9     0.1       0  5093.3    0.05       0
Bank Sta=5000.9,5006.9
Exp/Cntr=0.3,0.1

Type RM Length L Ch R = 1,8475,409,409,409
BEGIN DESCRIPTION:
UNT020 IN SPCR 19.0
END DESCRIPTION:
XS GIS Cut Line= 3
      2237637.71     13290246.85      2236837.72     13289796.85
      2236437.70     13289596.85
#Sta/Elev= 30
  4106.1  247.11  4114.1  246.70  4119.8  243.54  4141.5  240.65  4173.3  240.82
  4181.1  240.12  4260.0  236.98  4427.7  233.00  4494.0  230.58  4659.4  224.61
  4668.0  224.30  4826.7  220.07  4966.6  218.88  4972.7  216.37  4978.4  217.45
  4994.3  216.36  5001.0  212.09  5013.0  211.78  5015.7  211.28  5019.0  211.78
  5021.1  217.43  5039.0  217.64  5054.7  218.92  5060.3  218.13  5149.7  220.38
  5256.0  226.36  5314.7  228.03  5367.8  231.98  5440.4  235.66  5471.2  238.53
#Mann=8,-1,0
  4106.1     0.1       0  4181.1    0.05       0  4494.0     0.1       0
  4659.4    0.05       0  4668.0     0.1       0  5013.0    0.07       0
  5019.0     0.1       0  5039.0    0.05       0
Bank Sta=5013,5019
Exp/Cntr=0.3,0.1

Type RM Length L Ch R = 1,8066,429,429,429
BEGIN DESCRIPTION:
UNT020 IN SPCR 18.0
END DESCRIPTION:
XS GIS Cut Line= 4
      2237700.73     13289969.65      2237348.64     13289674.07
      2236818.38     13289322.01      2236366.38     13289322.01
#Sta/Elev= 30
  4075.9  242.32  4150.9  239.90  4305.8  231.81  4428.0  226.30  4491.8  224.67
  4512.6  222.32  4571.2  221.52  4577.2  220.66  4607.3  220.19  4643.4  218.19
  4677.9  217.91  4706.5  216.76  4831.4  215.52  4953.1  216.12  4980.8  217.00
  4992.2  207.90  4995.0  207.40  4998.2  207.90  5004.3  208.57  5010.3  210.78
  5016.9  216.62  5067.4  215.60  5111.4  216.98  5244.9  222.90  5332.8  225.49
  5408.9  229.91  5482.8  234.15  5522.8  234.32  5594.2  238.12  5624.1  239.61
#Mann=10,-1,0
  4075.9    0.05       0  4305.8     0.1       0  4677.9    0.16       0
  4831.4     0.1       0  4992.2    0.07       0  4998.2     0.1       0
  5111.4    0.16       0  5244.9     0.1       0  5408.9    0.05       0
  5594.2     0.1       0
Bank Sta=4992.2,4998.2
Exp/Cntr=0.3,0.1

Type RM Length L Ch R = 1,7637,385,385,385
BEGIN DESCRIPTION:
UNT020 IN SPCR 17.0
END DESCRIPTION:
XS GIS Cut Line= 3
      2237837.74     13289846.87      2237237.72     13289096.85
      2236837.71     13288696.84
#Sta/Elev= 30
  4044.3  248.02  4086.7  244.57  4144.4  242.84  4229.2  237.18  4464.5  225.32
  4691.8  215.55  4813.2  212.49  4876.7  212.23  4962.4  214.28  4968.8  212.49
  4976.8  213.06  4991.2  209.66  4994.6  206.17  4997.3  205.67  5000.6  206.17
  5001.6  208.10  5008.3  208.10  5018.9  213.05  5033.1  214.91  5059.1  214.45
  5160.4  214.62  5246.4  218.68  5287.6  220.21  5315.9  222.79  5330.1  227.13
  5358.3  224.55  5372.5  224.81  5400.8  227.20  5429.1  226.95  5570.5  235.10
#Mann=6,-1,0
  4044.3    0.05       0  4813.2     0.1       0  4994.6    0.07       0
  5000.6     0.1       0  5059.1    0.16       0  5246.4     0.1       0
Bank Sta=4994.6,5000.6
Exp/Cntr=0.3,0.1

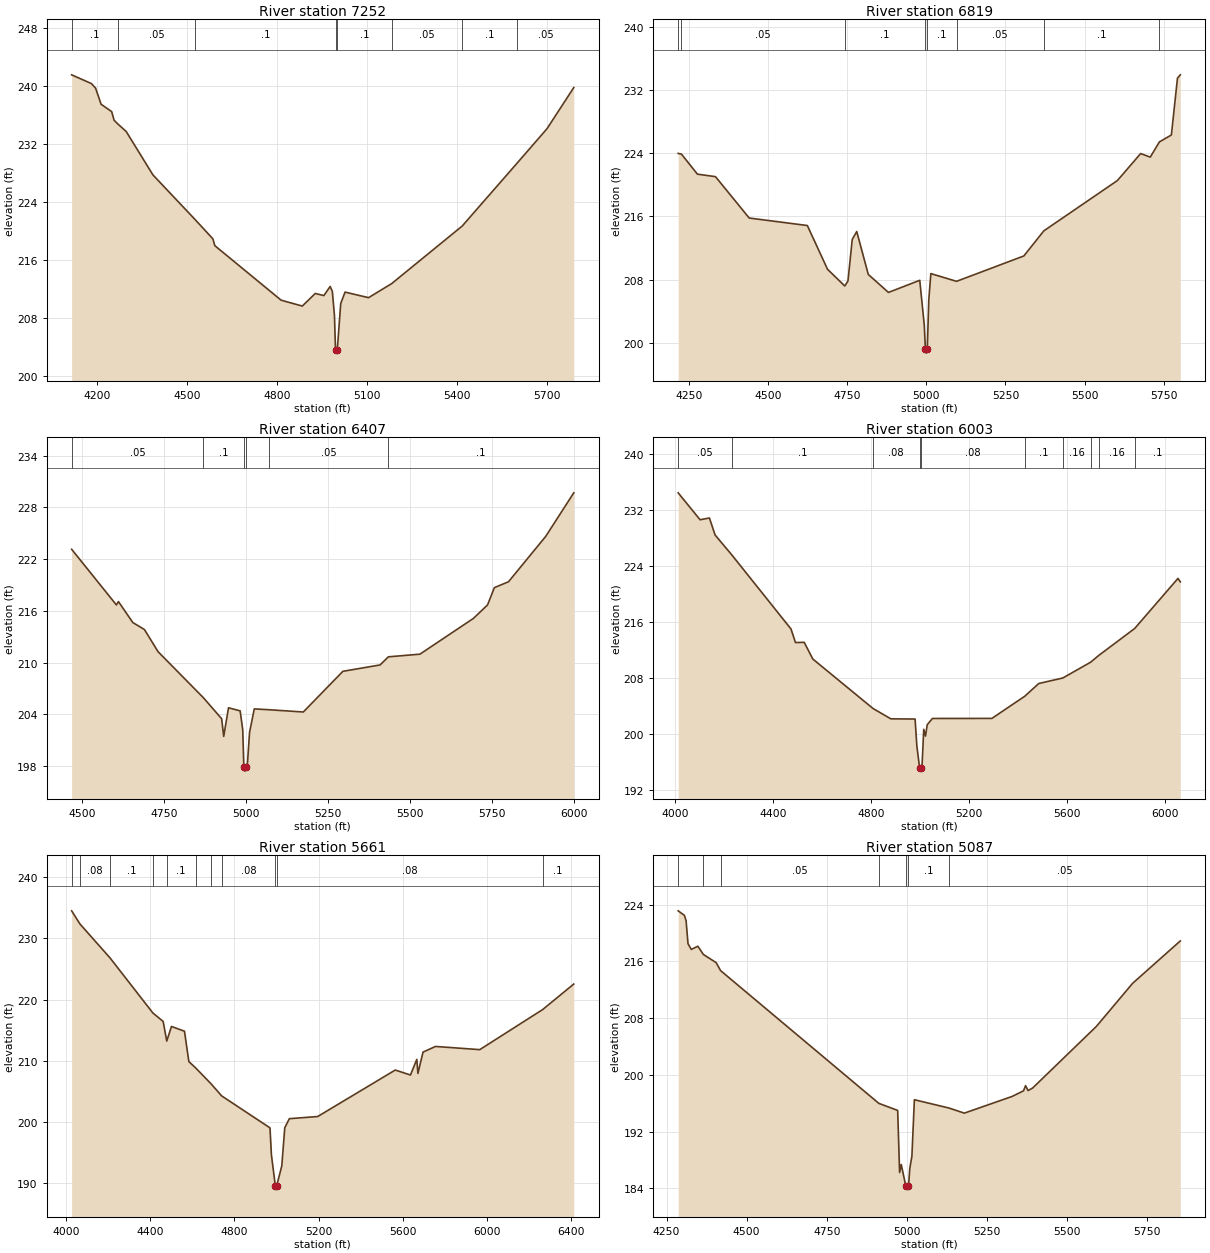
Type RM Length L Ch R = 1,7252,433,433,433
BEGIN DESCRIPTION:
UNT020 IN SPCR 16.0
END DESCRIPTION:
XS GIS Cut Line= 4
      2237991.67     13289627.88      2237828.83     13289224.16
      2237313.12     13288582.91      2236909.40     13288491.31
#Sta/Elev= 30
  4116.1  241.59  4181.9  240.38  4195.8  239.75  4214.2  237.52  4249.5  236.50
  4257.4  235.31  4271.0  234.75  4297.8  233.75  4386.8  227.75  4527.3  221.57
  4586.5  218.90  4593.0  217.96  4813.8  210.42  4884.2  209.61  4927.4  211.35
  4956.1  211.06  4977.0  212.32  4984.3  211.64  4991.3  208.30  4994.8  203.60
  4997.5  203.10  5000.8  203.60  5012.2  209.96  5026.6  211.54  5104.9  210.77
  5181.7  212.71  5416.8  220.68  5600.7  229.43  5699.2  234.14  5788.3  239.83
#Mann=8,-1,0
  4116.1     0.1       0  4271.0    0.05       0  4527.3     0.1       0
  4994.8    0.07       0  5000.8     0.1       0  5181.7    0.05       0
  5416.8     0.1       0  5600.7    0.05       0
Bank Sta=4994.8,5000.8
Exp/Cntr=0.3,0.1

Type RM Length L Ch R = 1,6819,412,412,412
BEGIN DESCRIPTION:
UNT020 IN SPCR 15.0
END DESCRIPTION:
XS GIS Cut Line= 3
      2238320.79     13289149.51      2237699.90     13288403.09
      2237121.22     13288189.89
#Sta/Elev= 30
  4215.3  224.00  4225.7  223.91  4276.1  221.37  4333.3  221.05  4439.9  215.80
  4623.7  214.85  4687.5  209.30  4742.0  207.18  4752.1  207.81  4765.6  213.07
  4779.9  214.09  4816.4  208.64  4880.2  206.36  4979.1  207.90  4993.4  202.22
  4996.9  199.16  4999.7  198.66  5002.9  199.16  5007.7  205.42  5014.2  208.75
  5095.4  207.77  5308.3  210.99  5371.3  214.17  5604.1  220.56  5677.5  223.98
  5707.9  223.53  5736.8  225.46  5774.7  226.34  5793.9  233.55  5802.9  233.97
#Mann=8,-1,0
  4215.3     0.1       0  4225.7    0.05       0  4742.0     0.1       0
  4996.9    0.07       0  5002.9     0.1       0  5095.4    0.05       0
  5371.3     0.1       0  5736.8    0.05       0
Bank Sta=4996.9,5002.9
Exp/Cntr=0.3,0.1

Type RM Length L Ch R = 1,6407,404,404,404
BEGIN DESCRIPTION:
UNT020 IN SPCR 14.0
END DESCRIPTION:
XS GIS Cut Line= 3
      2238487.74     13288746.88      2238187.72     13288346.85
      2237387.73     13287696.86
#Sta/Elev= 30
  4468.1  223.15  4604.6  216.69  4610.8  217.08  4654.6  214.65  4690.0  213.84
  4731.7  211.26  4869.7  205.93  4925.4  203.49  4931.7  201.44  4946.3  204.76
  4981.8  204.40  4989.7  202.21  4993.1  197.91  4995.9  197.41  4999.1  197.91
  5004.1  198.31  5010.5  201.91  5024.9  204.63  5071.0  204.53  5174.3  204.27
  5295.0  208.99  5408.4  209.73  5433.6  210.67  5529.9  210.98  5692.9  215.13
  5736.0  216.69  5756.8  218.70  5799.9  219.38  5913.4  224.65  5998.9  229.70
#Mann=6,-1,0
  4468.1    0.05       0  4869.7     0.1       0  4993.1    0.07       0
  4999.1     0.1       0  5071.0    0.05       0  5433.6     0.1       0
Bank Sta=4993.1,4999.1
Exp/Cntr=0.3,0.1

Type RM Length L Ch R = 1,6003,342,342,342
BEGIN DESCRIPTION:
Mapping XS ed228e4f
END DESCRIPTION:
XS GIS Cut Line= 4
      2238787.21     13288954.55      2238877.48     13288503.21
      2238301.09     13287926.82      2237606.60     13287586.52
#Sta/Elev= 30
  4012.0  234.48  4101.4  230.63  4139.6  230.88  4162.6  228.45  4230.9  225.60
  4472.3  215.01  4490.7  213.07  4526.1  213.10  4561.5  210.71  4806.9  203.64
  4879.7  202.16  4978.7  202.13  4985.7  198.34  4996.9  195.18  4999.6  194.68
  5002.9  195.18  5006.9  195.38  5014.0  200.66  5021.1  199.69  5028.1  201.31
  5049.4  202.21  5292.1  202.22  5426.2  205.39  5483.3  207.21  5581.5  208.00
  5695.0  210.26  5728.2  211.23  5874.7  215.08  6051.3  222.24  6060.8  221.75
#Mann=10,-1,0
  4012.0    0.05       0  4230.9     0.1       0  4806.9    0.08       0
  4996.9    0.07       0  5002.9    0.08       0  5426.2     0.1       0
  5581.5    0.16       0  5695.0     0.1       0  5728.2    0.16       0
  5874.7     0.1       0
Bank Sta=4996.9,5002.9
Exp/Cntr=0.3,0.1

Type RM Length L Ch R = 1,5661,574,574,574
BEGIN DESCRIPTION:
Mapping XS 59a25691
END DESCRIPTION:
XS GIS Cut Line= 4
      2238877.48     13288933.77      2239058.04     13288280.99
      2238495.54     13287780.99      2237606.69     13287426.83
#Sta/Elev= 30
  4026.2  234.50  4065.6  232.36  4209.0  226.80  4412.2  217.83  4461.2  216.44
  4478.3  213.24  4500.7  215.62  4562.5  214.85  4583.3  209.89  4615.5  208.86
  4689.8  206.23  4738.8  204.30  4969.0  199.07  4975.7  194.68  4994.4  189.57
  4997.2  189.07  5000.4  189.57  5025.0  192.85  5039.2  199.09  5061.0  200.57
  5195.6  200.92  5564.3  208.51  5636.7  207.70  5666.8  210.25  5672.1  207.96
  5696.4  211.44  5755.7  212.36  5966.1  211.84  6264.9  218.38  6412.9  222.55
#Mann=11,-1,0
  4026.2    0.05       0  4065.6    0.08       0  4209.0     0.1       0
  4412.2    0.08       0  4478.3     0.1       0  4615.5    0.08       0
  4689.8    0.05       0  4738.8    0.08       0  4994.4    0.07       0
  5000.4    0.08       0  6264.9     0.1       0
Bank Sta=4994.4,5000.4
Exp/Cntr=0.3,0.1

Type RM Length L Ch R = 1,5087,451,451,451
BEGIN DESCRIPTION:
UNT020 IN SPCR 11.0
END DESCRIPTION:
XS GIS Cut Line= 3
      2239237.72     13288646.86      2239387.72     13287946.85
      2238837.70     13287296.83
#Sta/Elev= 30
  4286.4  223.11  4306.0  222.46  4311.1  221.72  4317.1  218.48  4327.3  217.67
  4347.8  218.12  4365.1  216.96  4404.9  215.81  4418.7  214.69  4912.6  195.98
  4971.6  194.98  4977.6  186.23  4982.7  187.36  4996.7  184.39  4999.5  183.89
  5002.7  184.39  5005.6  184.39  5009.4  186.80  5016.0  188.55  5023.7  196.49
  5132.5  195.31  5179.7  194.60  5329.2  196.96  5364.3  197.74  5370.9  198.47
  5378.6  197.78  5392.9  198.14  5591.8  206.82  5704.9  212.89  5853.8  218.87
#Mann=7,-1,0
  4286.4     0.1       0  4365.1    0.08       0  4418.7    0.05       0
  4912.6     0.1       0  4996.7    0.07       0  5002.7     0.1       0
  5132.5    0.05       0
Bank Sta=4996.7,5002.7
Exp/Cntr=0.3,0.1

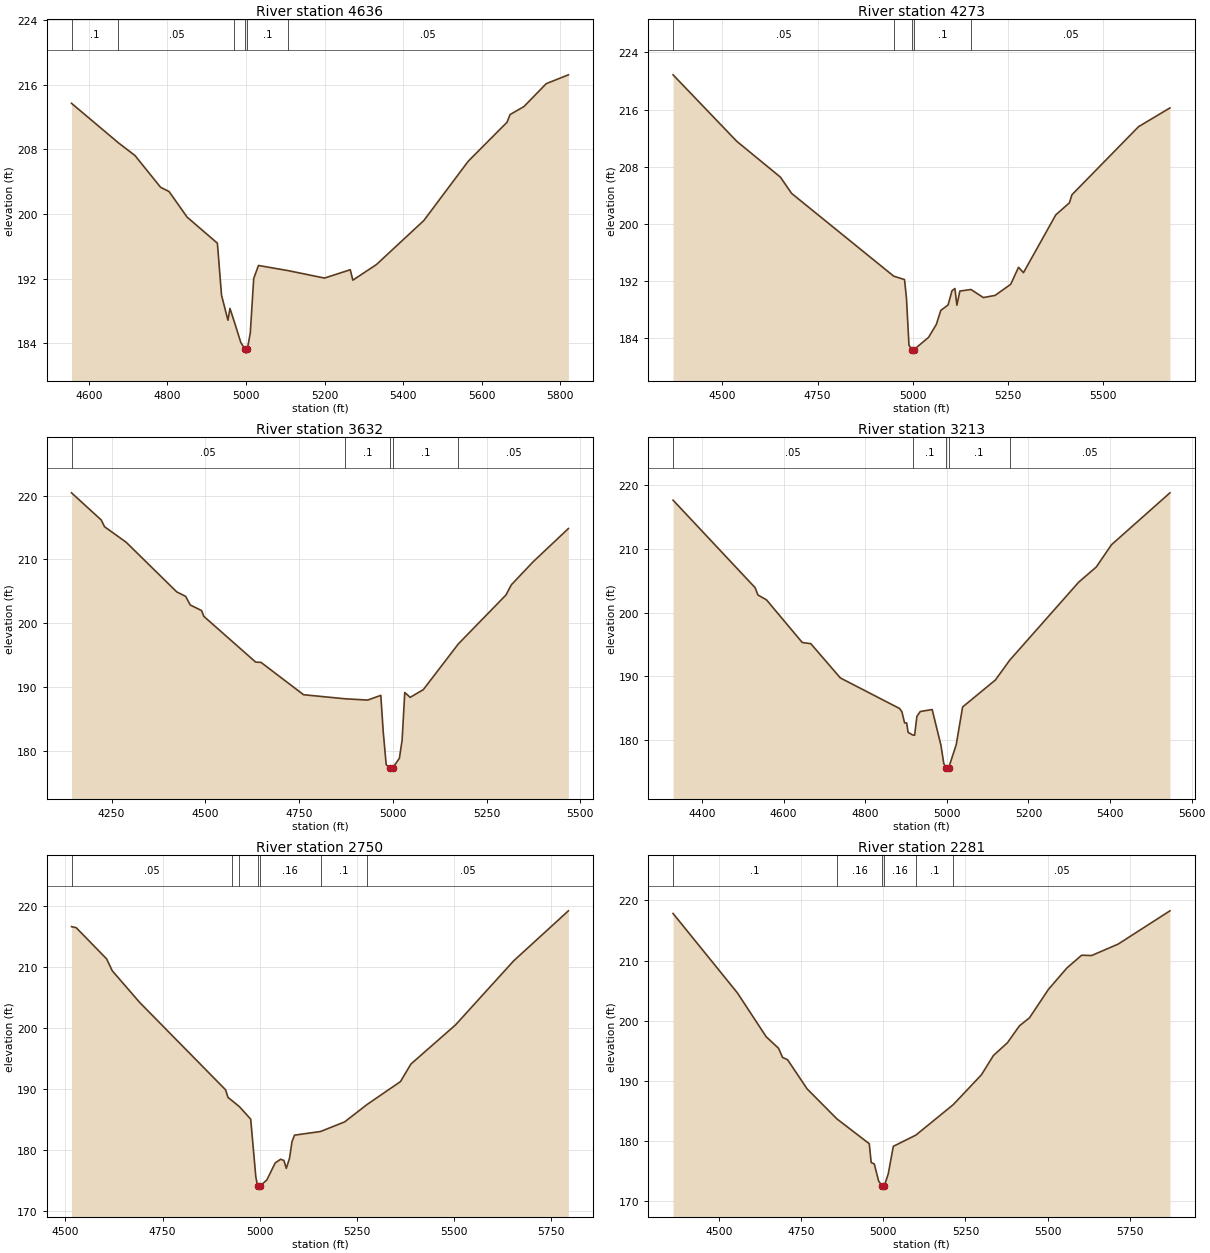
Type RM Length L Ch R = 1,4636,363,363,363
BEGIN DESCRIPTION:
UNT020 IN SPCR 10.0
END DESCRIPTION:
XS GIS Cut Line= 4
      2240039.40     13287813.57      2239795.72     13287676.50
      2239369.33     13287547.07      2238958.17     13287196.82
#Sta/Elev= 30
  4555.7  213.72  4674.8  208.84  4717.4  207.25  4782.5  203.32  4804.1  202.79
  4850.1  199.62  4927.2  196.39  4937.7  189.96  4954.0  186.85  4959.2  188.31
  4970.4  186.64  4986.9  184.08  4997.4  183.27  5000.1  182.77  5003.4  183.27
  5010.9  185.25  5019.7  192.02  5031.8  193.63  5106.4  193.00  5199.9  192.07
  5265.6  193.10  5272.1  191.81  5332.1  193.74  5452.9  199.20  5566.0  206.55
  5664.8  211.38  5672.5  212.33  5707.6  213.31  5764.7  216.16  5821.0  217.25
#Mann=6,-1,0
  4555.7     0.1       0  4674.8    0.05       0  4970.4     0.1       0
  4997.4    0.07       0  5003.4     0.1       0  5106.4    0.05       0
Bank Sta=4997.4,5003.4
Exp/Cntr=0.3,0.1

Type RM Length L Ch R = 1,4273,641,641,641
BEGIN DESCRIPTION:
UNT020 IN SPCR 9.0
END DESCRIPTION:
XS GIS Cut Line= 3
      2240211.32     13287503.83      2239966.17     13287344.81
      2238980.80     13287113.35
#Sta/Elev= 30
  4370.4  220.87  4537.5  211.56  4652.2  206.53  4681.6  204.25  4949.6  192.65
  4978.0  192.17  4983.1  189.57  4989.7  182.98  4997.0  182.36  4999.7  181.86
  5003.0  182.36  5041.1  184.07  5061.6  185.89  5073.1  187.84  5092.4  188.62
  5102.7  190.62  5110.3  190.91  5115.5  188.58  5123.3  190.56  5152.4  190.78
  5184.9  189.65  5215.7  189.95  5256.8  191.51  5277.3  193.89  5290.3  193.14
  5375.1  201.24  5410.9  202.93  5417.5  204.06  5592.3  213.60  5674.8  216.23
#Mann=5,-1,0
  4370.4    0.05       0  4949.6     0.1       0  4997.0    0.07       0
  5003.0     0.1       0  5152.4    0.05       0
Bank Sta=4997,5003
Exp/Cntr=0.3,0.1

Type RM Length L Ch R = 1,3632,419,419,419
BEGIN DESCRIPTION:
UNT020 IN SPCR 8.0
END DESCRIPTION:
XS GIS Cut Line= 3
      2240270.91     13287384.54      2239873.42     13287119.55
      2239336.77     13286463.64
#Sta/Elev= 30
  4143.2  220.45  4222.7  216.18  4231.2  215.14  4288.8  212.71  4424.0  204.91
  4447.5  204.22  4460.0  202.86  4490.1  201.99  4496.1  201.08  4634.3  193.91
  4648.7  193.86  4762.1  188.79  4871.7  188.16  4933.0  187.95  4968.1  188.69
  4974.6  182.96  4982.5  177.81  4993.8  177.31  4996.6  176.81  4999.8  177.31
  5017.7  178.83  5024.9  181.66  5032.0  189.14  5046.4  188.38  5081.5  189.59
  5174.9  196.76  5301.9  204.43  5316.3  206.03  5373.7  209.60  5468.4  214.85
#Mann=5,-1,0
  4143.2    0.05       0  4871.7     0.1       0  4993.8    0.07       0
  4999.8     0.1       0  5174.9    0.05       0
Bank Sta=4993.8,4999.8
Exp/Cntr=0.3,0.1

Type RM Length L Ch R = 1,3213,463,463,463
BEGIN DESCRIPTION:
UNT020 IN SPCR 7.0
END DESCRIPTION:
XS GIS Cut Line= 3
      2240376.93     13287265.28      2240065.55     13286788.27
      2239741.80     13286226.65
#Sta/Elev= 30
  4328.9  217.68  4530.0  203.94  4536.9  202.79  4558.0  202.02  4645.5  195.33
  4666.6  195.14  4739.0  189.76  4883.9  184.97  4889.8  184.46  4896.4  182.70
  4901.4  182.70  4905.1  181.21  4916.2  180.81  4920.9  180.76  4926.6  183.73
  4934.8  184.49  4964.0  184.80  4985.5  179.19  4992.5  176.31  4998.3  175.63
  5001.1  175.13  5004.3  175.63  5022.9  179.27  5038.6  185.20  5119.1  189.45
  5153.8  192.53  5323.1  204.80  5366.2  207.18  5403.5  210.68  5546.8  218.83
#Mann=5,-1,0
  4328.9    0.05       0  4916.2     0.1       0  4998.3    0.07       0
  5004.3     0.1       0  5153.8    0.05       0
Bank Sta=4998.3,5004.3
Exp/Cntr=0.3,0.1

Type RM Length L Ch R = 1,2750,469,469,469
BEGIN DESCRIPTION:
UNT020 IN SPCR 6.0
END DESCRIPTION:
XS GIS Cut Line= 3
      2240801.00     13286940.68      2240622.09     13286722.02
      2239821.58     13286126.59
#Sta/Elev= 30
  4515.5  216.66  4527.7  216.48  4606.0  211.37  4620.3  209.44  4690.7  204.26
  4912.5  189.90  4918.7  188.65  4929.3  188.12  4948.3  187.13  4977.2  185.09
  4990.4  175.62  4995.0  174.12  4997.8  173.62  5001.0  174.12  5018.8  175.13
  5040.3  177.92  5054.3  178.52  5062.7  178.32  5068.9  177.02  5077.3  178.71
  5083.5  181.39  5090.1  182.47  5157.3  183.07  5219.1  184.64  5277.1  187.50
  5363.0  191.25  5390.1  194.14  5504.8  200.54  5655.0  211.07  5795.7  219.25
#Mann=7,-1,0
  4515.5    0.05       0  4929.3     0.1       0  4948.3    0.16       0
  4995.0    0.07       0  5001.0    0.16       0  5157.3     0.1       0
  5277.1    0.05       0
Bank Sta=4995,5001
Exp/Cntr=0.3,0.1

Type RM Length L Ch R = 1,2281,447,447,447
BEGIN DESCRIPTION:
UNT020 IN SPCR 5.0
END DESCRIPTION:
XS GIS Cut Line= 4
      2241178.64     13286490.13      2240820.86     13286291.36
      2240151.69     13285873.95      2239841.47     13285834.35
#Sta/Elev= 30
  4361.0  217.84  4556.5  204.63  4644.0  197.33  4681.8  195.40  4693.8  193.89
  4709.2  193.49  4768.7  188.64  4859.0  183.66  4957.5  179.52  4963.4  176.39
  4972.8  176.15  4986.1  173.29  4997.0  172.46  4999.7  171.96  5003.0  172.46
  5015.3  174.51  5030.6  179.08  5099.2  180.95  5212.8  186.02  5298.4  190.98
  5335.0  194.20  5377.5  196.32  5414.0  199.13  5444.7  200.48  5502.5  205.22
  5558.4  208.77  5603.3  210.89  5633.5  210.84  5714.2  212.74  5871.7  218.28
#Mann=6,-1,0
  4361.0     0.1       0  4859.0    0.16       0  4997.0    0.07       0
  5003.0    0.16       0  5099.2     0.1       0  5212.8    0.05       0
Bank Sta=4997,5003
Exp/Cntr=0.3,0.1

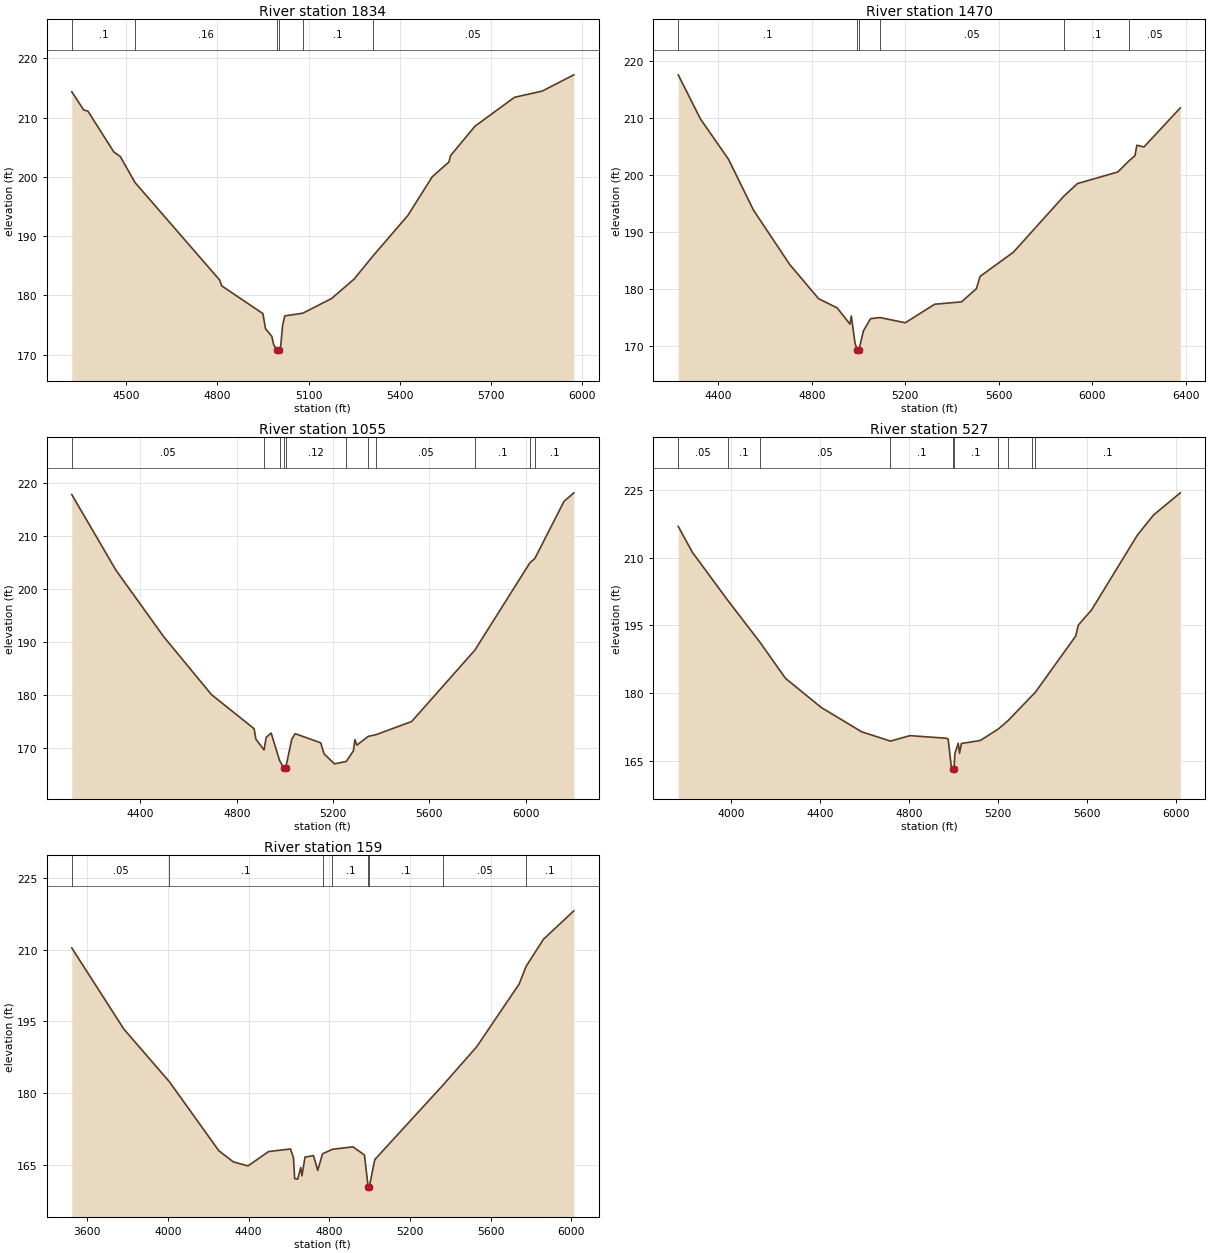
Type RM Length L Ch R = 1,1834,364,364,364
BEGIN DESCRIPTION:
UNT020 IN SPCR 4.0
END DESCRIPTION:
XS GIS Cut Line= 4
      2241357.56     13286211.88      2241059.38     13285946.84
      2240721.48     13285695.07      2239893.30     13285748.07
#Sta/Elev= 30
  4321.8  214.38  4361.0  211.30  4375.1  211.09  4459.7  204.23  4481.4  203.42
  4529.9  199.03  4808.3  182.56  4814.6  181.60  4950.1  176.91  4958.5  174.38
  4979.3  173.07  4985.5  171.66  4997.1  170.74  4999.9  170.24  5003.1  170.74
  5008.5  171.42  5014.7  174.91  5022.1  176.53  5081.0  176.98  5176.0  179.47
  5249.8  182.74  5310.4  186.56  5426.5  193.49  5506.6  200.02  5561.6  202.52
  5566.8  203.59  5646.9  208.55  5777.2  213.44  5867.4  214.47  5972.0  217.23
#Mann=6,-1,0
  4321.8     0.1       0  4529.9    0.16       0  4997.1    0.07       0
  5003.1    0.16       0  5081.0     0.1       0  5310.4    0.05       0
Bank Sta=4997.1,5003.1
Exp/Cntr=0.3,0.1

Type RM Length L Ch R = 1,1470,415,415,415
BEGIN DESCRIPTION:
UNT020 IN SPCR 3.0
END DESCRIPTION:
XS GIS Cut Line= 4
      2241635.78     13285933.57      2241377.40     13285661.94
      2240635.35     13285271.04      2239714.44     13285436.67
#Sta/Elev= 30
  4227.7  217.54  4322.9  209.80  4443.4  202.71  4549.4  193.86  4704.0  184.36
  4828.3  178.33  4908.1  176.70  4962.9  173.87  4968.5  175.30  4984.9  170.44
  4994.8  169.28  4997.6  168.78  5000.8  169.28  5020.4  172.67  5051.0  174.82
  5091.8  175.01  5199.6  174.10  5325.6  177.35  5440.4  177.76  5503.7  180.06
  5520.2  182.23  5662.4  186.46  5879.2  196.31  5936.8  198.49  6109.5  200.52
  6159.0  202.53  6183.0  203.37  6190.8  205.20  6221.3  204.90  6377.0  211.75
#Mann=6,-1,0
  4227.7     0.1       0  4994.8    0.07       0  5000.8     0.1       0
  5091.8    0.05       0  5879.2     0.1       0  6159.0    0.05       0
Bank Sta=4994.8,5000.8
Exp/Cntr=0.3,0.1

Type RM Length L Ch R = 1,1055,528,528,528
BEGIN DESCRIPTION:
UNT020 IN SPCR 2.0
END DESCRIPTION:
XS GIS Cut Line= 3
      2241827.97     13285675.22      2241092.50     13285032.52
      2240224.58     13284343.48
#Sta/Elev= 30
  4114.9  217.84  4298.4  203.59  4496.8  191.05  4695.2  180.14  4872.2  173.72
  4879.4  171.75  4913.3  169.72  4922.1  172.09  4942.9  172.90  4978.1  167.70
  4996.9  166.23  4999.7  165.73  5002.9  166.23  5028.4  171.75  5042.6  172.79
  5148.8  171.06  5162.5  168.99  5205.8  167.10  5255.0  167.56  5284.3  169.55
  5290.7  171.67  5298.7  170.63  5346.1  172.28  5377.7  172.59  5526.2  175.07
  5788.8  188.53  6017.1  204.97  6038.1  205.82  6159.0  216.56  6199.8  218.17
#Mann=11,-1,0
  4114.9    0.05       0  4913.3     0.1       0  4978.1    0.12       0
  4996.9    0.07       0  5002.9    0.12       0  5255.0     0.1       0
  5346.1    0.12       0  5377.7    0.05       0  5788.8     0.1       0
  6017.1    0.05       0  6038.1     0.1       0
Bank Sta=4996.9,5002.9
Exp/Cntr=0.3,0.1

Type RM Length L Ch R = 1,527,368,368,368
BEGIN DESCRIPTION:
Mapping XS 6b20956e
END DESCRIPTION:
XS GIS Cut Line= 4
      2241986.96     13285542.71      2241768.30     13285045.77
      2240522.71     13284230.83      2240297.42     13284237.46
#Sta/Elev= 30
  3763.9  216.92  3827.2  211.20  3985.9  200.57  4132.0  191.18  4245.9  183.23
  4407.2  176.75  4588.1  171.38  4717.8  169.31  4805.3  170.52  4971.1  169.93
  4977.1  169.75  4992.2  163.30  4997.6  163.15  5000.4  162.65  5003.6  163.15
  5007.3  166.54  5022.4  168.82  5028.4  166.63  5036.5  168.77  5121.9  169.45
  5202.8  171.99  5246.7  173.86  5355.9  179.47  5367.4  180.03  5550.2  192.57
  5562.3  195.04  5622.0  198.41  5827.7  214.98  5900.3  219.44  6020.7  224.36
#Mann=10,-1,0
  3763.9    0.05       0  3985.9     0.1       0  4132.0    0.05       0
  4717.8     0.1       0  4997.6    0.07       0  5003.6     0.1       0
  5202.8    0.05       0  5246.7     0.1       0  5355.9    0.05       0
  5367.4     0.1       0
Bank Sta=4997.6,5003.6
Exp/Cntr=0.3,0.1

Type RM Length L Ch R = 1,159,0,0,0
BEGIN DESCRIPTION:
UNT020 IN SPCR 1.0
END DESCRIPTION:
XS GIS Cut Line= 4
      2242192.32     13285443.26      2241980.32     13284774.12
      2241046.13     13284157.95      2240376.96     13284124.83
#Sta/Elev= 30
  3522.5  210.34  3780.9  193.39  4006.7  182.39  4252.1  167.97  4324.3  165.64
  4396.6  164.80  4499.0  167.80  4607.4  168.34  4622.5  166.53  4628.5  162.14
  4643.5  162.03  4658.6  164.47  4664.6  162.74  4679.7  166.65  4721.8  166.95
  4742.9  163.87  4766.7  167.33  4815.8  168.27  4917.5  168.79  4974.7  167.08
  4992.8  160.45  4995.5  159.95  4998.8  160.45  5025.9  166.12  5363.8  181.66
  5532.1  189.72  5742.4  202.81  5776.2  206.46  5862.6  212.14  6013.5  218.09
#Mann=8,-1,0
  3522.5    0.05       0  4006.7     0.1       0  4766.7    0.16       0
  4815.8     0.1       0  4992.8    0.07       0  4998.8     0.1       0
  5363.8    0.05       0  5776.2     0.1       0
Bank Sta=4992.8,4998.8
Exp/Cntr=0.3,0.1

Chan Stop Cuts=-1