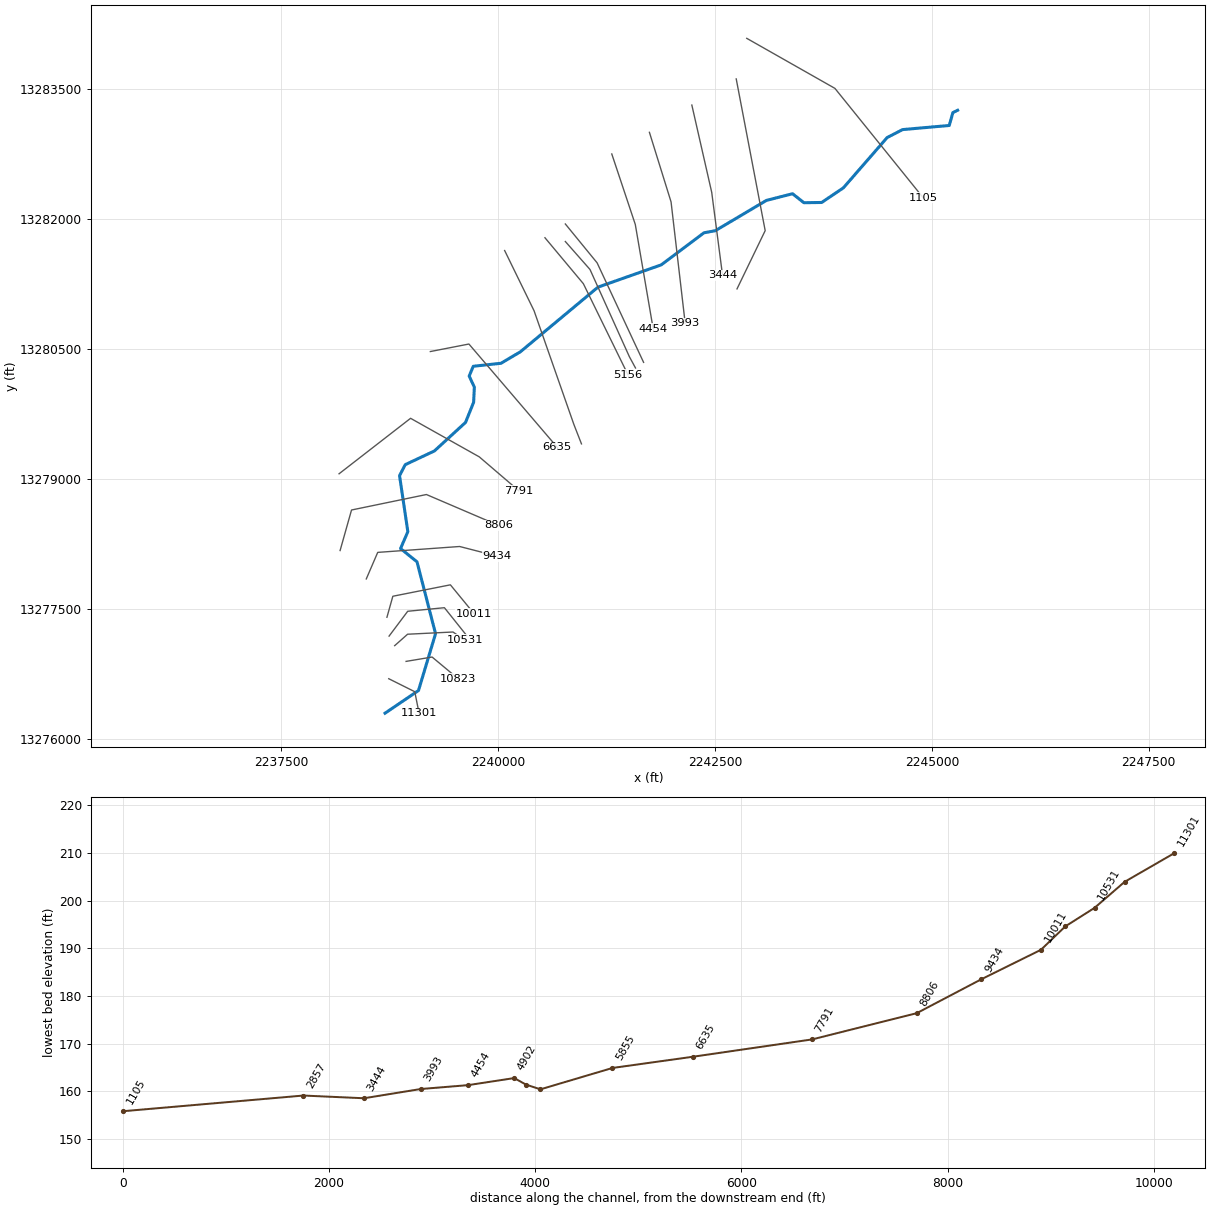
--- UNT021 IN SPCR.prj (project) ---

Proj Title=UNT021 IN SPCR Base Level Engineering
Current Plan=p01
Default Exp/Contr=0.3,0.1
English Units
Geom File=g01
Flow File=f01
Plan File=p01
BEGIN DESCRIPTION:
UNT021 IN SPCR
END DESCRIPTION:

--- UNT021 IN SPCR.p01 (plan) ---

Plan Title=Multiple Run
Short Identifier=Multiple
Geom File=g01
Flow File=f01
Subcritical Flow
K Sum by GR= 0
Std Step Tol= 0.01
Critical Tol= 0.01
Num of Std Step Trials= 20
Max Error Tol= 0.3
Flow Tol Ratio= 0.001
Split Flow NTrial= 30
Split Flow Tol= 0.02
Split Flow Ratio= 0.02
Log Output Level= 0
Friction Slope Method= 1
Unsteady Friction Slope Method= 2
Unsteady Bridges Friction Slope Method= 1
Parabolic Critical Depth
Global Vel Dist=  1 , 1 , 1
Global Log Level= 0
CheckData=True
Encroach Param= -1, 0, 0, 0
BEGIN DESCRIPTION:
Multiple Run
END DESCRIPTION:

--- UNT021 IN SPCR.f01 (steady flow) ---

Flow Title=Multiple
Number of Profiles=7
Profile Names=10-year,25-year,50-year,1pct_min,100-year,1pct_plu,500-year
River Rch & RM= UNT021 IN SPCR,Reach-1,11301
     229     320     396     361     489     661     755
River Rch & RM= UNT021 IN SPCR,Reach-1,6635
     321     454     566     519     702     949    1096
Boundary for River Rch & Prof#=UNT021 IN SPCR,Reach-1,1
Up Type=0
Dn Type=3
Dn Slope=0.005
Boundary for River Rch & Prof#=UNT021 IN SPCR,Reach-1,2
Up Type=0
Dn Type=3
Dn Slope=0.005
Boundary for River Rch & Prof#=UNT021 IN SPCR,Reach-1,3
Up Type=0
Dn Type=3
Dn Slope=0.005
Boundary for River Rch & Prof#=UNT021 IN SPCR,Reach-1,4
Up Type=0
Dn Type=3
Dn Slope=0.005
Boundary for River Rch & Prof#=UNT021 IN SPCR,Reach-1,5
Up Type=0
Dn Type=3
Dn Slope=0.005
Boundary for River Rch & Prof#=UNT021 IN SPCR,Reach-1,6
Up Type=0
Dn Type=3
Dn Slope=0.005
Boundary for River Rch & Prof#=UNT021 IN SPCR,Reach-1,7
Up Type=0
Dn Type=3
Dn Slope=0.005

--- UNT021 IN SPCR.g01 (geometry) ---

Geom Title=Existing Conditions

River Reach=UNT021 IN SPCR,Reach-1
Reach XY= 30
      2238694.70     13276298.75      2239080.58     13276560.49
      2239277.37     13277216.19      2239063.55     13278045.60
      2238874.04     13278199.16      2238957.86     13278393.70
      2238862.28     13279039.66      2238927.72     13279166.85
      2239264.21     13279325.14      2239623.00     13279654.09
      2239716.50     13279887.06      2239724.93     13280061.36
      2239665.18     13280189.37      2239712.42     13280302.18
      2240032.56     13280337.01      2240256.14     13280469.59
      2241150.43     13281215.41      2241880.06     13281472.55
      2242373.52     13281843.02      2242502.86     13281866.45
      2243092.27     13282216.28      2243394.13     13282293.26
      2243524.32     13282189.66      2243730.19     13282192.50
      2243979.78     13282360.94      2244485.02     13282941.83
      2244663.38     13283033.58      2245200.99     13283081.05
      2245242.65     13283229.49      2245297.72     13283256.85

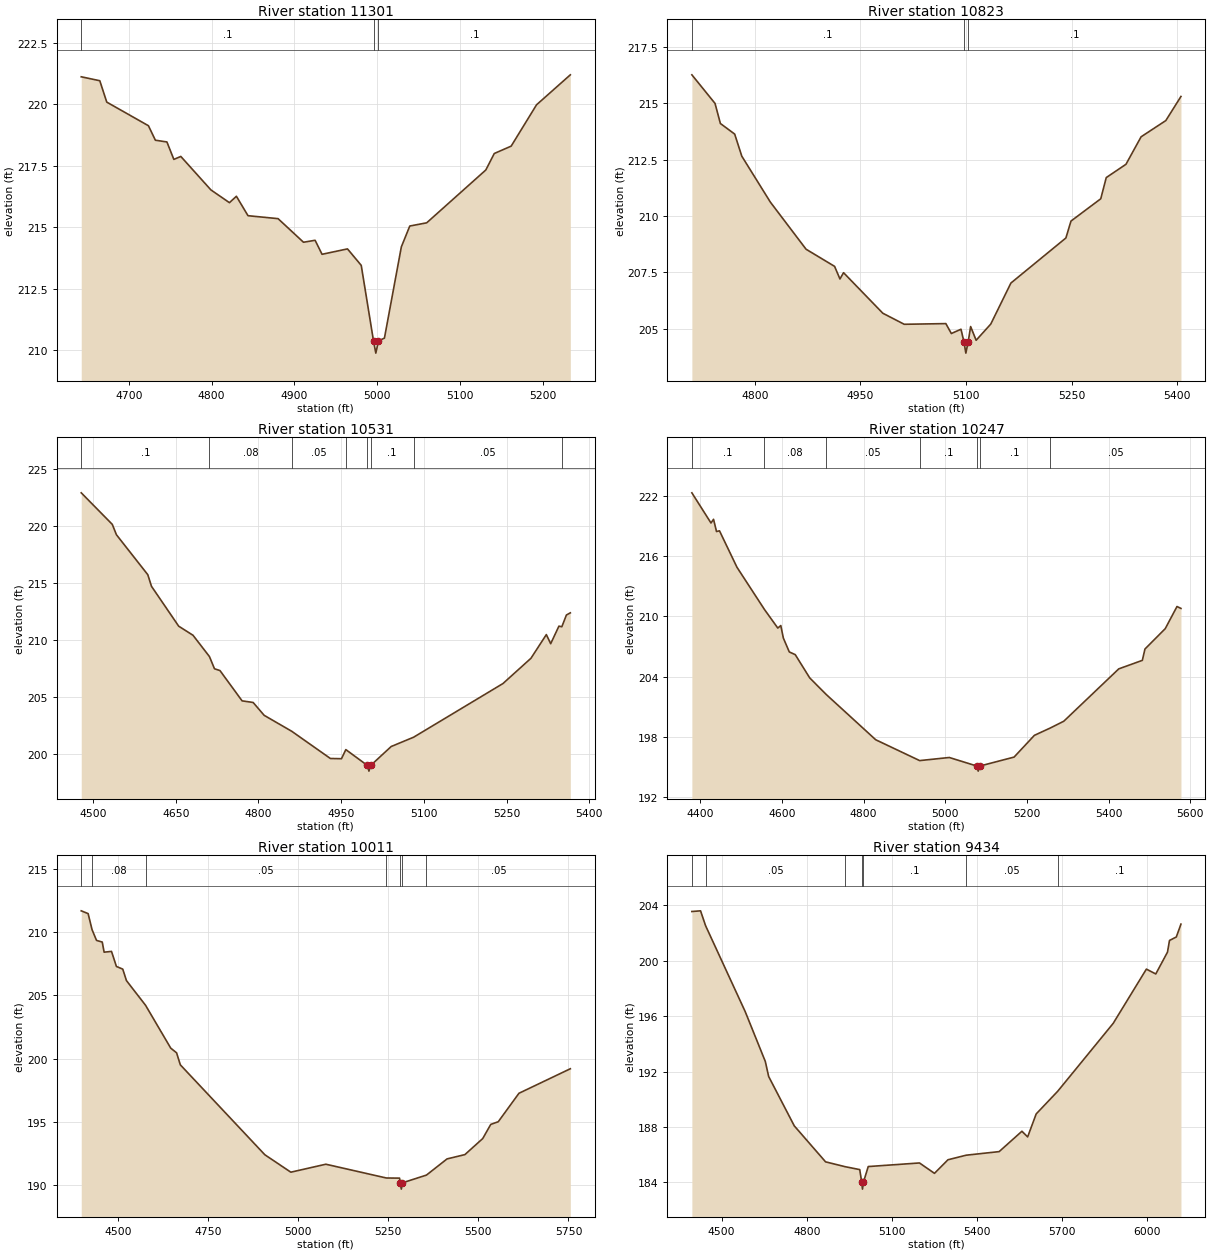
Type RM Length L Ch R = 1,11301,478,478,478
BEGIN DESCRIPTION:
UNT021 IN SPCR 13.0
END DESCRIPTION:
XS GIS Cut Line= 3
      2238737.71     13276696.86      2239037.72     13276546.85
      2239087.73     13276296.83
#Sta/Elev= 30
  4642.7  221.12  4665.1  220.96  4673.5  220.09  4723.8  219.13  4732.2  218.54
  4746.1  218.47  4754.5  217.76  4762.9  217.88  4799.2  216.52  4821.6  216.00
  4830.0  216.26  4844.0  215.47  4880.3  215.35  4911.0  214.39  4925.0  214.47
  4933.4  213.90  4964.1  214.12  4980.7  213.45  4995.5  210.38  4998.3  209.88
  5001.5  210.38  5008.7  210.49  5029.1  214.20  5039.3  215.05  5059.7  215.18
  5131.1  217.33  5141.3  218.00  5161.7  218.30  5192.3  219.98  5233.1  221.20
#Mann=3,-1,0
  4642.7     0.1       0  4995.5    0.07       0  5001.5     0.1       0
Bank Sta=4995.5,5001.5
Exp/Cntr=0.3,0.1

Type RM Length L Ch R = 1,10823,292,292,292
BEGIN DESCRIPTION:
UNT021 IN SPCR 12.0
END DESCRIPTION:
XS GIS Cut Line= 3
      2238937.76     13276896.86      2239237.72     13276946.85
      2239537.71     13276696.86
#Sta/Elev= 30
  4710.7  216.27  4743.6  215.00  4751.2  214.11  4771.5  213.64  4781.6  212.66
  4822.2  210.62  4872.9  208.53  4913.4  207.77  4921.0  207.21  4926.1  207.49
  4981.9  205.69  5012.3  205.20  5071.4  205.23  5079.2  204.79  5092.9  204.98
  5097.1  204.42  5099.8  203.92  5103.1  204.42  5106.6  205.10  5114.4  204.49
  5135.2  205.21  5163.8  207.03  5241.9  209.03  5249.1  209.78  5291.4  210.77
  5299.2  211.71  5327.2  212.30  5348.7  213.52  5383.8  214.24  5405.3  215.31
#Mann=3,-1,0
  4710.7     0.1       0  5097.1    0.07       0  5103.1     0.1       0
Bank Sta=5097.1,5103.1
Exp/Cntr=0.3,0.1

Type RM Length L Ch R = 1,10531,284,284,284
BEGIN DESCRIPTION:
UNT021 IN SPCR 11.0
END DESCRIPTION:
XS GIS Cut Line= 4
      2238806.18     13277078.41      2238955.06     13277210.28
      2239478.23     13277235.80      2239613.56     13277142.77
#Sta/Elev= 30
  4478.6  222.90  4534.9  220.13  4542.4  219.22  4599.3  215.71  4606.0  214.69
  4655.3  211.19  4681.3  210.39  4711.1  208.52  4720.2  207.45  4730.2  207.29
  4770.3  204.63  4790.3  204.49  4810.3  203.36  4860.3  201.96  4930.4  199.57
  4950.5  199.55  4958.4  200.35  4997.5  198.96  5000.3  198.46  5003.5  198.96
  5040.6  200.62  5081.4  201.44  5243.3  206.15  5294.1  208.37  5322.0  210.45
  5329.9  209.65  5344.8  211.19  5350.1  211.14  5358.4  212.17  5365.5  212.36
#Mann=8,-1,0
  4478.6     0.1       0  4711.1    0.08       0  4860.3    0.05       0
  4958.4     0.1       0  4997.5    0.07       0  5003.5     0.1       0
  5081.4    0.05       0  5350.1    0.08       0
Bank Sta=4997.5,5003.5
Exp/Cntr=0.3,0.1

Type RM Length L Ch R = 1,10247,236,236,236
BEGIN DESCRIPTION:
Mapping XS 7625c2f6
END DESCRIPTION:
XS GIS Cut Line= 4
      2238741.51     13277188.63      2238956.34     13277475.07
      2239379.52     13277516.30      2239637.74     13277192.99
#Sta/Elev= 30
  4379.9  222.33  4426.7  219.32  4432.9  219.69  4440.2  218.47  4447.5  218.54
  4490.2  214.91  4557.6  210.69  4590.2  208.84  4597.5  209.09  4603.8  207.84
  4618.3  206.46  4632.9  206.19  4668.3  203.87  4708.3  202.23  4829.8  197.70
  4937.4  195.62  5009.9  195.93  5077.9  195.07  5080.7  194.57  5083.9  195.07
  5168.5  195.97  5218.2  198.14  5257.0  198.87  5290.2  199.55  5424.7  204.77
  5482.4  205.62  5488.8  206.75  5538.4  208.78  5567.2  210.99  5576.9  210.80
#Mann=7,-1,0
  4379.9     0.1       0  4557.6    0.08       0  4708.3    0.05       0
  4937.4     0.1       0  5077.9    0.07       0  5083.9     0.1       0
  5257.0    0.05       0
Bank Sta=5077.9,5083.9
Exp/Cntr=0.3,0.1

Type RM Length L Ch R = 1,10011,577,577,577
BEGIN DESCRIPTION:
UNT021 IN SPCR 10.0
END DESCRIPTION:
XS GIS Cut Line= 4
      2238716.88     13277405.99      2238784.92     13277648.39
      2239448.46     13277780.25      2239720.65     13277448.51
#Sta/Elev= 30
  4397.7  211.68  4416.8  211.46  4427.7  210.19  4440.1  209.34  4456.0  209.21
  4461.2  208.41  4481.7  208.47  4495.3  207.28  4512.9  207.07  4523.2  206.16
  4576.2  204.21  4646.1  200.82  4662.3  200.45  4672.7  199.50  4907.2  192.39
  4979.4  191.01  5076.6  191.64  5244.5  190.55  5281.1  190.54  5283.2  190.17
  5286.0  189.67  5289.2  190.17  5355.8  190.78  5413.0  192.06  5462.5  192.40
  5512.0  193.67  5534.3  194.79  5555.1  195.00  5612.5  197.25  5755.1  199.19
#Mann=7,-1,0
  4397.7     0.1       0  4427.7    0.08       0  4576.2    0.05       0
  5244.5     0.1       0  5283.2    0.03       0  5289.2     0.1       0
  5355.8    0.05       0
Bank Sta=5283.2,5289.2
Exp/Cntr=0.3,0.1

Type RM Length L Ch R = 1,9434,628,628,628
BEGIN DESCRIPTION:
UNT021 IN SPCR 9.0
END DESCRIPTION:
XS GIS Cut Line= 4
      2238478.68     13277848.33      2238610.53     13278154.55
      2239554.80     13278222.61      2239983.59     13278112.22
#Sta/Elev= 30
  4395.1  203.56  4425.7  203.61  4443.1  202.55  4583.2  196.32  4653.8  192.73
  4665.7  191.64  4755.8  188.08  4866.1  185.48  4935.1  185.13  4986.4  184.92
  4993.4  184.01  4996.1  183.51  4999.4  184.01  5016.4  185.14  5196.9  185.40
  5249.7  184.65  5297.2  185.63  5361.2  185.96  5477.6  186.22  5557.8  187.69
  5577.9  187.28  5608.0  188.94  5683.9  190.58  5879.2  195.48  5996.2  199.40
  6029.3  199.05  6070.6  200.63  6077.6  201.47  6101.6  201.72  6118.0  202.65
#Mann=7,-1,0
  4395.1    0.08       0  4443.1    0.05       0  4935.1     0.1       0
  4993.4    0.07       0  4999.4     0.1       0  5361.2    0.05       0
  5683.9     0.1       0
Bank Sta=4993.4,4999.4
Exp/Cntr=0.3,0.1

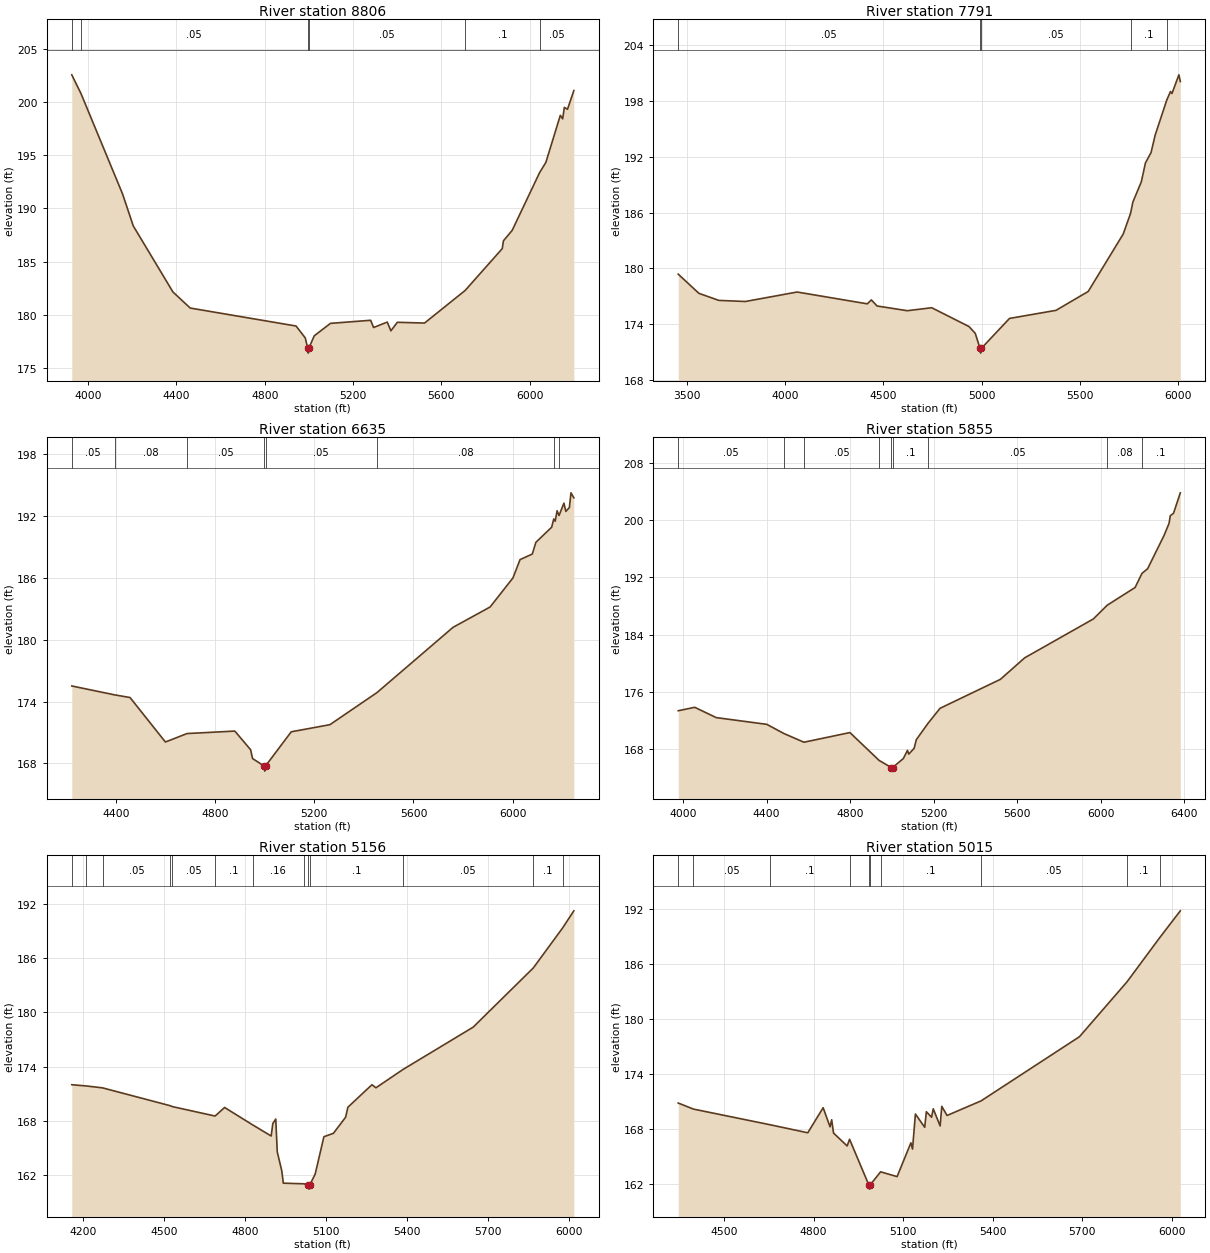
Type RM Length L Ch R = 1,8806,1015,1015,1015
BEGIN DESCRIPTION:
UNT021 IN SPCR 8.0
END DESCRIPTION:
XS GIS Cut Line= 4
      2238176.67     13278175.81      2238308.53     13278643.70
      2239171.98     13278822.35      2240004.22     13278465.68
#Sta/Elev= 30
  3926.4  202.57  3967.9  200.82  4156.1  191.38  4204.8  188.36  4384.6  182.14
  4462.8  180.63  4942.0  178.94  4983.6  177.82  4994.3  176.89  4997.0  176.39
  5000.3  176.89  5024.4  178.02  5097.7  179.19  5279.7  179.48  5293.0  178.80
  5354.9  179.31  5371.4  178.49  5400.5  179.29  5523.8  179.22  5707.8  182.29
  5875.5  186.22  5881.0  186.96  5920.6  187.94  6044.4  193.36  6073.0  194.33
  6138.5  198.76  6149.1  198.43  6156.6  199.51  6170.9  199.33  6199.7  201.09
#Mann=6,-1,0
  3926.4    0.08       0  3967.9    0.05       0  4994.3    0.03       0
  5000.3    0.05       0  5707.8     0.1       0  6044.4    0.05       0
Bank Sta=4994.3,5000.3
Exp/Cntr=0.3,0.1

Type RM Length L Ch R = 1,7791,1156,1156,1156
BEGIN DESCRIPTION:
Mapping XS 1f5aecaf
END DESCRIPTION:
XS GIS Cut Line= 4
      2238164.75     13279061.58      2238989.43     13279701.79
      2239781.53     13279256.91      2240237.24     13278866.31
#Sta/Elev= 30
  3457.6  179.38  3562.6  177.32  3663.8  176.56  3798.7  176.44  4062.1  177.46
  4418.7  176.19  4439.5  176.61  4468.5  175.96  4622.1  175.45  4746.4  175.77
  4935.8  173.75  4967.7  173.02  4992.1  171.39  4994.8  170.89  4998.1  171.39
  5141.9  174.62  5378.3  175.49  5542.1  177.52  5719.9  183.69  5757.1  185.90
  5769.3  187.14  5812.1  189.31  5832.9  191.33  5861.5  192.45  5882.3  194.32
  5941.8  198.12  5960.3  199.01  5967.9  198.80  6003.1  200.81  6010.3  200.09
#Mann=5,-1,0
  3457.6    0.05       0  4992.1    0.03       0  4998.1    0.05       0
  5757.1     0.1       0  5941.8    0.05       0
Bank Sta=4992.1,4998.1
Exp/Cntr=0.3,0.1

Type RM Length L Ch R = 1,6635,780,780,780
BEGIN DESCRIPTION:
Mapping XS 69961f2a
END DESCRIPTION:
XS GIS Cut Line= 3
      2239217.27     13280472.19      2239662.18     13280559.00
      2240682.13     13279365.43
#Sta/Elev= 30
  4222.9  175.51  4395.2  174.65  4457.7  174.39  4600.3  170.08  4687.5  170.90
  4880.0  171.14  4943.7  169.33  4951.4  168.48  4997.8  167.76  5000.5  167.26
  5003.8  167.76  5107.3  171.07  5263.2  171.76  5453.0  174.87  5759.4  181.19
  5908.7  183.16  6000.9  185.98  6029.4  187.75  6078.8  188.29  6093.1  189.42
  6156.8  190.89  6165.3  191.69  6171.1  191.47  6178.6  192.48  6186.5  192.02
  6206.2  193.22  6213.9  192.42  6228.2  192.79  6234.7  194.22  6246.2  193.74
#Mann=8,-1,0
  4222.9    0.05       0  4395.2    0.08       0  4687.5    0.05       0
  4997.8    0.03       0  5003.8    0.05       0  5453.0    0.08       0
  6165.3     0.1       0  6186.5    0.08       0
Bank Sta=4997.8,5003.8
Exp/Cntr=0.3,0.1

Type RM Length L Ch R = 1,5855,699,699,699
BEGIN DESCRIPTION:
UNT021 IN SPCR 7.0
END DESCRIPTION:
XS GIS Cut Line= 4
      2240074.07     13281637.89      2240413.13     13280943.37
      2240872.51     13279630.87      2240960.00     13279406.67
#Sta/Elev= 30
  3977.0  173.35  4056.0  173.83  4159.0  172.39  4401.0  171.45  4482.8  170.17
  4578.8  168.95  4799.1  170.30  4938.8  166.41  4997.4  165.41  5000.2  164.91
  5003.4  165.41  5055.0  166.67  5074.6  167.82  5080.8  167.29  5106.4  168.09
  5117.1  169.31  5173.6  171.61  5230.6  173.69  5519.6  177.74  5636.1  180.75
  5964.7  186.18  6031.0  188.10  6164.7  190.58  6197.7  192.56  6224.4  193.19
  6303.2  197.85  6327.2  199.54  6333.1  200.61  6348.7  200.96  6381.1  203.81
#Mann=9,-1,0
  3977.0    0.05       0  4482.8    0.08       0  4578.8    0.05       0
  4938.8     0.1       0  4997.4    0.07       0  5003.4     0.1       0
  5173.6    0.05       0  6031.0    0.08       0  6197.7     0.1       0
Bank Sta=4997.4,5003.4
Exp/Cntr=0.3,0.1

Type RM Length L Ch R = 1,5156,141,141,141
BEGIN DESCRIPTION:
UNT021 IN SPCR 6.0
END DESCRIPTION:
XS GIS Cut Line= 3
      2240538.93     13281785.53      2240981.88     13281255.09
      2241495.97     13280205.05
#Sta/Elev= 30
  4158.8  171.99  4213.3  171.85  4273.0  171.64  4524.0  169.66  4531.0  169.57
  4689.8  168.52  4725.1  169.47  4830.2  167.52  4897.6  166.31  4903.6  167.68
  4914.6  168.19  4920.1  164.56  4937.0  162.44  4942.6  161.09  5017.7  161.02
  5035.2  160.93  5038.0  160.43  5041.2  160.93  5060.7  162.10  5092.9  166.23
  5128.3  166.61  5173.3  168.39  5181.9  169.50  5271.0  171.99  5285.8  171.65
  5386.2  173.68  5645.9  178.36  5868.9  184.92  5977.3  189.34  6019.0  191.24
#Mann=13,-1,0
  4158.8    0.05       0  4213.3    0.08       0  4273.0    0.05       0
  4524.0    0.08       0  4531.0    0.05       0  4689.8     0.1       0
  4830.2    0.16       0  5017.7     0.1       0  5035.2    0.07       0
  5041.2     0.1       0  5386.2    0.05       0  5868.9     0.1       0
  5977.3    0.08       0
Bank Sta=5035.2,5041.2
Exp/Cntr=0.3,0.1

Type RM Length L Ch R = 1,5015,113,113,113
BEGIN DESCRIPTION:
Mapping XS 41198456
END DESCRIPTION:
XS GIS Cut Line= 4
      2240774.04     13281741.85      2241058.44     13281419.15
      2241512.35     13280412.90      2241583.02     13280282.44
#Sta/Elev= 30
  4346.3  170.84  4397.1  170.18  4653.6  168.47  4780.4  167.59  4831.9  170.33
  4855.0  168.24  4860.5  169.01  4866.7  167.56  4912.3  166.15  4920.4  166.88
  4984.4  161.93  4987.1  161.43  4990.4  161.93  5024.4  163.32  5079.7  162.80
  5125.9  166.49  5131.4  165.81  5141.0  169.64  5172.2  168.19  5177.7  169.89
  5195.3  169.29  5200.8  170.21  5223.9  168.34  5229.4  170.48  5247.1  169.48
  5361.3  171.08  5690.8  178.09  5849.9  184.08  5959.3  188.90  6028.7  191.85
#Mann=10,-1,0
  4346.3    0.08       0  4397.1    0.05       0  4653.6     0.1       0
  4920.4    0.16       0  4984.4    0.07       0  4990.4    0.16       0
  5024.4     0.1       0  5361.3    0.05       0  5849.9     0.1       0
  5959.3    0.08       0
Bank Sta=4984.4,4990.4
Exp/Cntr=0.3,0.1

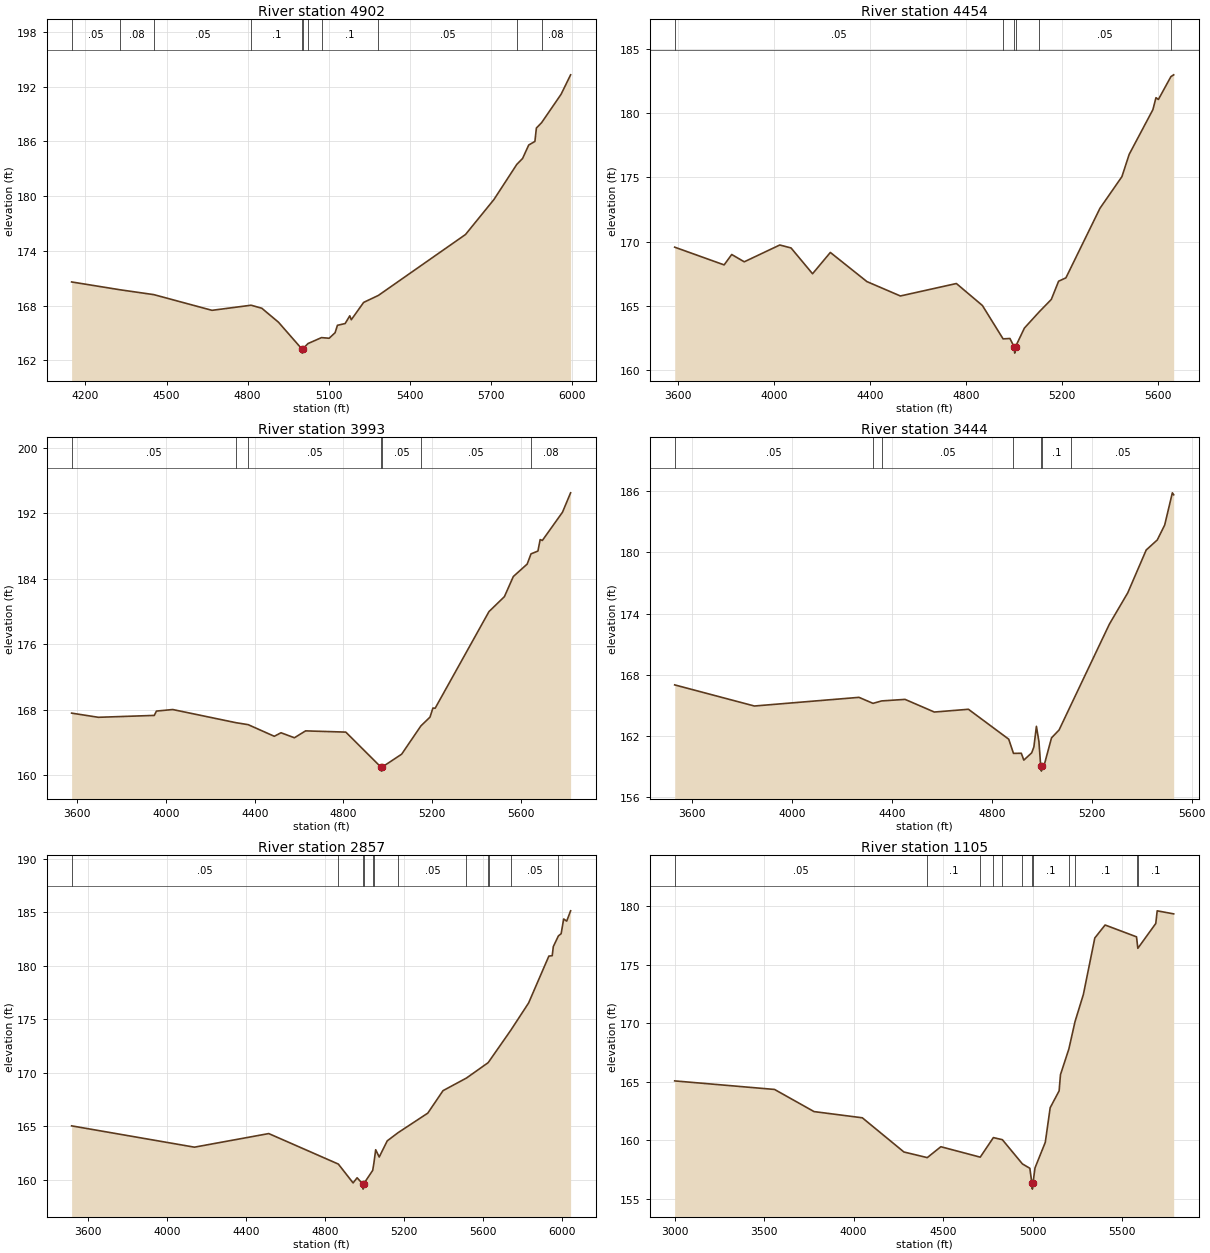
Type RM Length L Ch R = 1,4902,448,448,448
BEGIN DESCRIPTION:
Mapping XS cf817a5d
END DESCRIPTION:
XS GIS Cut Line= 4
      2240774.08     13281944.14      2241140.47     13281495.72
      2241556.10     13280604.31      2241676.41     13280347.29
#Sta/Elev= 30
  4148.9  170.59  4328.7  169.73  4453.2  169.20  4668.4  167.48  4813.1  168.04
  4852.6  167.71  4914.3  166.18  4999.6  163.29  5002.3  162.79  5005.6  163.29
  5023.6  163.84  5073.6  164.49  5101.9  164.42  5123.9  165.03  5132.5  165.84
  5160.9  166.03  5178.2  166.88  5183.8  166.45  5229.5  168.35  5283.8  169.11
  5606.4  175.79  5711.5  179.62  5796.1  183.47  5817.5  184.12  5840.4  185.60
  5863.2  185.99  5868.7  187.46  5887.8  188.04  5960.1  191.16  5995.3  193.29
#Mann=11,-1,0
  4148.9    0.05       0  4328.7    0.08       0  4453.2    0.05       0
  4813.1     0.1       0  4999.6    0.07       0  5005.6     0.1       0
  5023.6    0.16       0  5073.6     0.1       0  5283.8    0.05       0
  5796.1     0.1       0  5887.8    0.08       0
Bank Sta=4999.6,5005.6
Exp/Cntr=0.3,0.1

Type RM Length L Ch R = 1,4454,461,461,461
BEGIN DESCRIPTION:
UNT021 IN SPCR 5.0
END DESCRIPTION:
XS GIS Cut Line= 3
      2241309.48     13282752.36      2241580.75     13281938.55
      2241786.92     13280734.10
#Sta/Elev= 30
  3584.6  169.56  3790.7  168.18  3822.3  168.99  3874.6  168.42  4022.6  169.73
  4069.6  169.50  4159.2  167.49  4233.4  169.15  4385.8  166.88  4525.3  165.76
  4758.7  166.73  4867.1  165.02  4953.4  162.42  4981.9  162.45  4999.2  161.81
  5001.9  161.31  5005.2  161.81  5042.2  163.26  5103.7  164.52  5154.3  165.49
  5184.8  166.91  5215.2  167.17  5357.2  172.59  5448.6  175.05  5479.0  176.79
  5577.8  180.27  5590.6  181.20  5600.7  181.06  5652.8  182.84  5664.4  182.98
#Mann=6,-1,0
  3584.6    0.05       0  4953.4     0.1       0  4999.2    0.07       0
  5005.2     0.1       0  5103.7    0.05       0  5652.8     0.1       0
Bank Sta=4999.2,5005.2
Exp/Cntr=0.3,0.1

Type RM Length L Ch R = 1,3993,549,549,549
BEGIN DESCRIPTION:
Mapping XS 6b9b3d2b
END DESCRIPTION:
XS GIS Cut Line= 3
      2241743.51     13283001.92      2241993.08     13282198.97
      2242155.69     13280800.53
#Sta/Elev= 30
  3574.8  167.58  3695.3  167.07  3947.3  167.30  3957.1  167.83  4030.4  168.02
  4315.6  166.41  4370.5  166.17  4488.2  164.75  4518.4  165.18  4578.8  164.57
  4629.2  165.41  4810.4  165.26  4968.5  160.99  4971.2  160.49  4974.5  160.99
  5062.1  162.56  5148.6  166.01  5189.8  167.09  5203.0  168.20  5213.1  168.18
  5455.6  179.99  5525.2  181.82  5565.4  184.28  5627.8  185.80  5645.1  187.05
  5676.2  187.39  5686.3  188.79  5696.3  188.69  5786.9  192.14  5823.5  194.51
#Mann=7,-1,0
  3574.8    0.05       0  4315.6    0.08       0  4370.5    0.05       0
  4968.5    0.07       0  4974.5    0.05       0  5148.6    0.05       0
  5645.1    0.08       0
Bank Sta=4968.5,4974.5
Exp/Cntr=0.3,0.1

Type RM Length L Ch R = 1,3444,587,587,587
BEGIN DESCRIPTION:
UNT021 IN SPCR 4.0
END DESCRIPTION:
XS GIS Cut Line= 3
      2242232.66     13283316.62      2242461.83     13282309.65
      2242586.79     13281351.58
#Sta/Elev= 30
  3529.1  167.01  3848.4  164.94  4267.3  165.79  4323.6  165.20  4358.3  165.44
  4451.9  165.59  4569.2  164.35  4705.8  164.62  4867.2  161.69  4886.2  160.30
  4917.6  160.31  4927.7  159.64  4959.1  160.35  4968.0  160.93  4978.1  162.95
  4988.2  161.46  4995.3  159.06  4998.0  158.56  5001.3  159.06  5008.4  159.07
  5038.6  161.82  5068.9  162.59  5117.0  165.07  5270.6  172.97  5344.0  176.03
  5418.0  180.23  5462.2  181.21  5491.9  182.67  5522.7  185.83  5528.0  185.64
#Mann=7,-1,0
  3529.1    0.05       0  4323.6    0.08       0  4358.3    0.05       0
  4886.2     0.1       0  4995.3    0.07       0  5001.3     0.1       0
  5117.0    0.05       0
Bank Sta=4995.3,5001.3
Exp/Cntr=0.3,0.1

Type RM Length L Ch R = 1,2857,1752,1752,1752
BEGIN DESCRIPTION:
UNT021 IN SPCR 3.0
END DESCRIPTION:
XS GIS Cut Line= 3
      2242744.51     13283618.26      2243078.42     13281867.51
      2242753.54     13281195.19
#Sta/Elev= 30
  3515.9  165.04  4138.3  163.05  4515.0  164.32  4867.8  161.47  4942.5  159.71
  4962.9  160.19  4990.5  159.63  4993.2  159.13  4996.5  159.63  5041.9  160.88
  5048.1  161.58  5057.0  162.81  5074.9  162.13  5115.6  163.64  5171.0  164.41
  5321.1  166.23  5398.3  168.33  5517.2  169.51  5626.7  170.94  5628.8  170.99
  5742.0  173.98  5832.0  176.52  5934.7  180.90  5951.7  180.94  5957.3  181.79
  5983.1  182.79  5996.9  182.99  6009.7  184.37  6025.1  184.17  6044.9  185.13
#Mann=12,-1,0
  3515.9    0.05       0  4867.8     0.1       0  4990.5    0.07       0
  4996.5     0.1       0  5041.9    0.05       0  5048.1     0.1       0
  5171.0    0.05       0  5517.2     0.1       0  5626.7    0.05       0
  5628.8     0.1       0  5742.0    0.05       0  5983.1    0.08       0
Bank Sta=4990.5,4996.5
Exp/Cntr=0.3,0.1

Type RM Length L Ch R = 1,1105,0,0,0
BEGIN DESCRIPTION:
UNT021 IN SPCR 1.0
END DESCRIPTION:
XS GIS Cut Line= 3
      2242865.90     13284086.59      2243882.55     13283509.13
      2244899.19     13282248.50
#Sta/Elev= 30
  3000.0  165.08  3558.1  164.35  3778.7  162.46  4048.6  161.93  4281.2  159.01
  4411.6  158.53  4487.5  159.46  4707.6  158.57  4781.1  160.24  4831.4  160.06
  4943.5  157.99  4984.9  157.62  4996.3  156.34  4999.0  155.84  5002.3  156.34
  5013.7  157.65  5071.2  159.84  5098.5  162.79  5148.5  164.23  5156.0  165.61
  5203.0  167.81  5237.3  170.14  5284.0  172.46  5347.9  177.28  5405.4  178.39
  5581.0  177.38  5588.4  176.40  5688.6  178.52  5696.6  179.60  5788.7  179.34
#Mann=12,-1,0
  3000.0    0.05       0  4411.6     0.1       0  4707.6    0.05       0
  4781.1    0.08       0  4831.4    0.05       0  4943.5     0.1       0
  4996.3    0.07       0  5002.3     0.1       0  5203.0    0.08       0
  5237.3     0.1       0  5581.0    0.08       0  5588.4     0.1       0
Bank Sta=4996.3,5002.3
Exp/Cntr=0.3,0.1

Chan Stop Cuts=-1