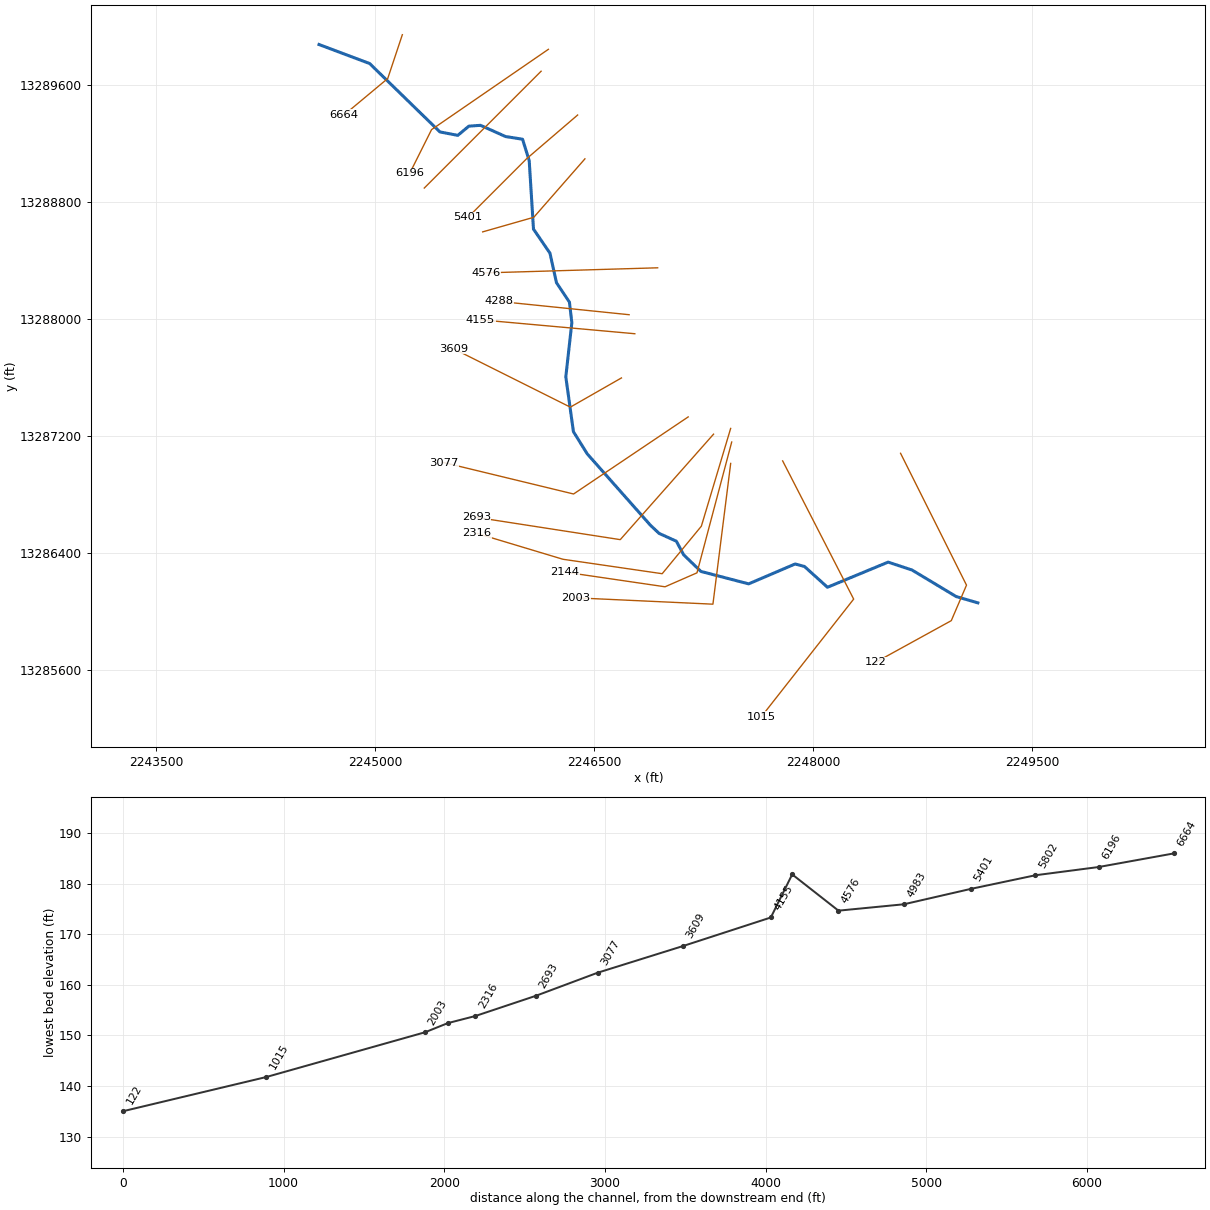
--- UNT022 IN SPCR.prj (project) ---

Proj Title=UNT022 IN SPCR Base Level Engineering
Current Plan=p01
Default Exp/Contr=0.3,0.1
English Units
Geom File=g01
Flow File=f01
Plan File=p01
BEGIN DESCRIPTION:
UNT022 IN SPCR
END DESCRIPTION:

--- UNT022 IN SPCR.p01 (plan) ---

Plan Title=Multiple Run
Short Identifier=Multiple
Geom File=g01
Flow File=f01
Subcritical Flow
K Sum by GR= 0
Std Step Tol= 0.01
Critical Tol= 0.01
Num of Std Step Trials= 20
Max Error Tol= 0.3
Flow Tol Ratio= 0.001
Split Flow NTrial= 30
Split Flow Tol= 0.02
Split Flow Ratio= 0.02
Log Output Level= 0
Friction Slope Method= 1
Unsteady Friction Slope Method= 2
Unsteady Bridges Friction Slope Method= 1
Parabolic Critical Depth
Global Vel Dist=  1 , 1 , 1
Global Log Level= 0
CheckData=True
Encroach Param= -1, 0, 0, 0
BEGIN DESCRIPTION:
Multiple Run
END DESCRIPTION:

--- UNT022 IN SPCR.f01 (steady flow) ---

Flow Title=Multiple
Number of Profiles=7
Profile Names=10-year,25-year,50-year,1pct_min,100-year,1pct_plu,500-year
River Rch & RM= UNT022 IN SPCR,Reach-1,6664
     356     508     638     589     797    1078    1263
River Rch & RM= UNT022 IN SPCR,Reach-1,122
     439     632     799     742    1004    1358    1610
Boundary for River Rch & Prof#=UNT022 IN SPCR,Reach-1,1
Up Type=0
Dn Type=3
Dn Slope=0.005
Boundary for River Rch & Prof#=UNT022 IN SPCR,Reach-1,2
Up Type=0
Dn Type=3
Dn Slope=0.005
Boundary for River Rch & Prof#=UNT022 IN SPCR,Reach-1,3
Up Type=0
Dn Type=3
Dn Slope=0.005
Boundary for River Rch & Prof#=UNT022 IN SPCR,Reach-1,4
Up Type=0
Dn Type=3
Dn Slope=0.005
Boundary for River Rch & Prof#=UNT022 IN SPCR,Reach-1,5
Up Type=0
Dn Type=3
Dn Slope=0.005
Boundary for River Rch & Prof#=UNT022 IN SPCR,Reach-1,6
Up Type=0
Dn Type=3
Dn Slope=0.005
Boundary for River Rch & Prof#=UNT022 IN SPCR,Reach-1,7
Up Type=0
Dn Type=3
Dn Slope=0.005

--- UNT022 IN SPCR.g01 (geometry) ---

Geom Title=Existing Conditions

River Reach=UNT022 IN SPCR,Reach-1
Reach XY= 30
      2244617.13     13289879.61      2244964.02     13289749.33
      2245444.79     13289281.20      2245567.29     13289257.64
      2245643.06     13289320.58      2245722.50     13289326.38
      2245894.53     13289249.56      2246010.64     13289231.11
      2246056.21     13289084.63      2246085.51     13288615.88
      2246198.35     13288450.95      2246242.84     13288249.12
      2246331.82     13288115.66      2246348.09     13287974.60
      2246306.86     13287604.59      2246358.94     13287229.16
      2246453.35     13287077.25      2246885.19     13286589.43
      2246945.19     13286532.66      2247063.60     13286479.04
      2247113.86     13286385.65      2247231.77     13286272.13
      2247558.64     13286186.94      2247877.13     13286323.04
      2247940.84     13286306.03      2248098.22     13286163.62
      2248513.54     13286335.80      2248677.07     13286281.74
      2248979.13     13286100.26      2249127.72     13286056.85

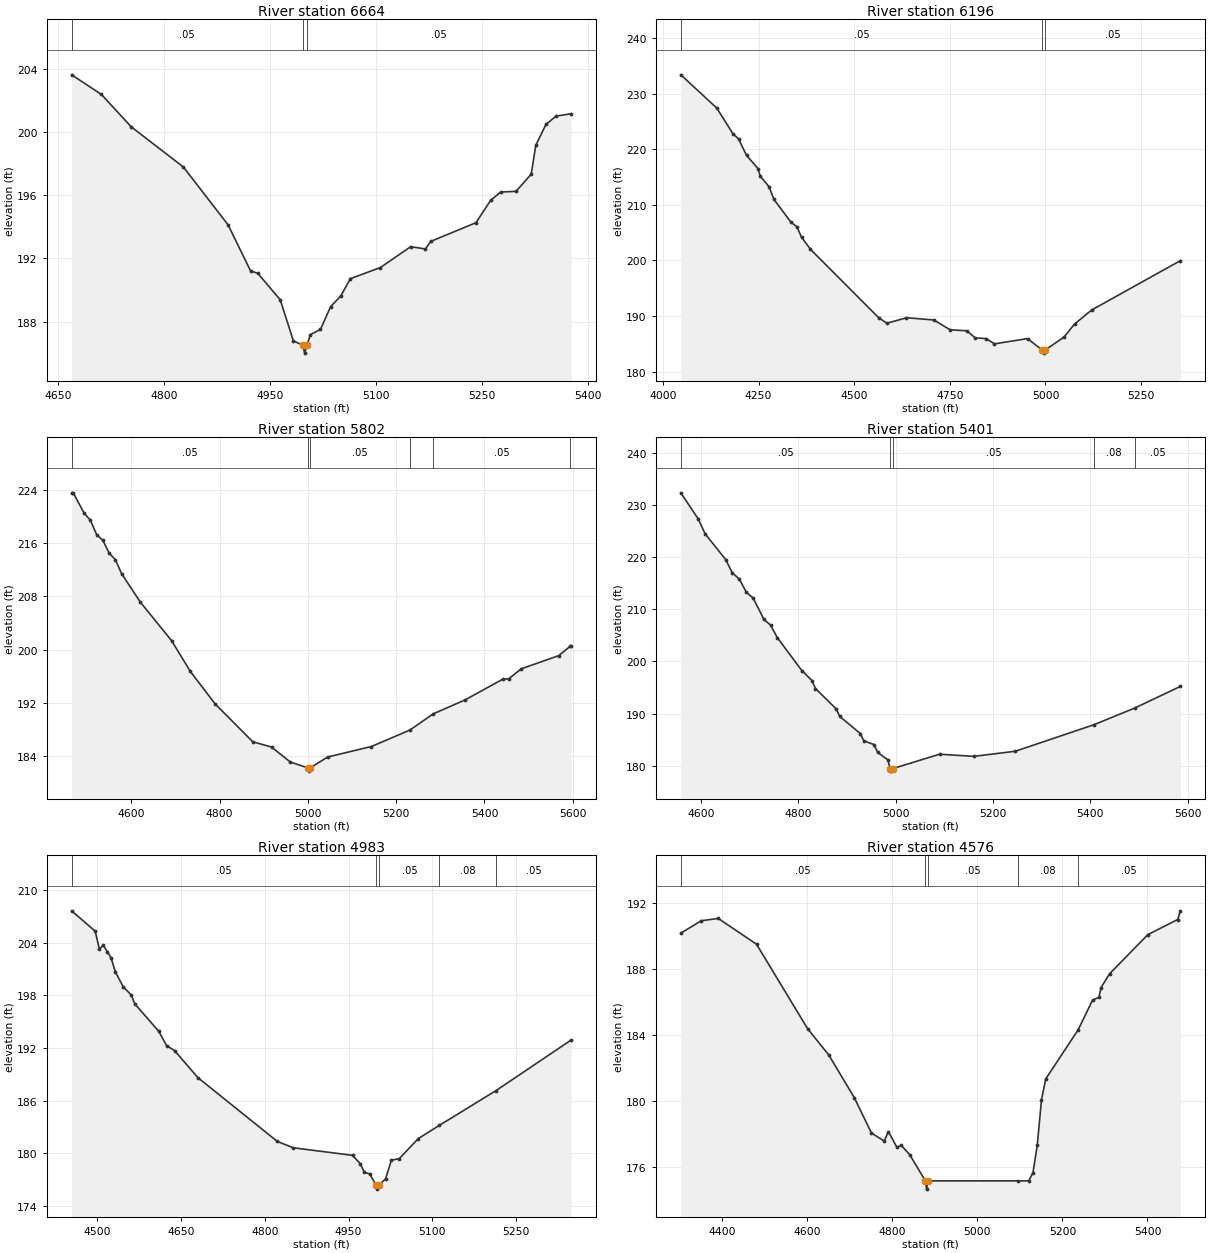
Type RM Length L Ch R = 1,6664,468,468,468
BEGIN DESCRIPTION:
UNT022 IN SPCR 12.0
END DESCRIPTION:
XS GIS Cut Line= 3
      2245187.71     13289946.83      2245087.72     13289646.85
      2244787.73     13289396.86
#Sta/Elev= 30
  4669.7  203.60  4711.8  202.36  4754.0  200.31  4827.8  197.77  4891.0  194.11
  4922.7  191.21  4933.2  191.04  4964.8  189.37  4983.3  186.78  4996.6  186.50
  4999.3  186.00  5002.6  186.50  5007.4  187.17  5021.7  187.50  5036.0  188.94
  5050.3  189.61  5064.0  190.71  5106.3  191.41  5149.3  192.73  5170.1  192.59
  5177.9  193.07  5241.7  194.25  5262.5  195.67  5276.8  196.19  5298.3  196.23
  5319.8  197.32  5326.3  199.15  5340.6  200.46  5354.9  200.99  5376.4  201.14
#Mann=3,-1,0
  4669.7    0.05       0  4996.6    0.03       0  5002.6    0.05       0
Bank Sta=4996.6,5002.6
Exp/Cntr=0.3,0.1

Type RM Length L Ch R = 1,6196,394,394,394
BEGIN DESCRIPTION:
UNT022 IN SPCR 11.0
END DESCRIPTION:
XS GIS Cut Line= 3
      2246187.70     13289846.84      2245387.72     13289296.85
      2245237.72     13288996.86
#Sta/Elev= 30
  4046.7  233.43  4140.7  227.44  4182.6  222.85  4197.5  221.89  4218.5  218.92
  4248.3  216.56  4254.4  215.17  4277.2  213.29  4290.2  210.98  4334.9  206.86
  4349.8  206.10  4362.2  204.20  4385.6  202.01  4564.9  189.62  4585.9  188.70
  4636.6  189.68  4708.3  189.28  4750.5  187.52  4794.9  187.33  4815.9  186.07
  4845.7  185.91  4866.6  184.98  4953.2  185.93  4992.2  183.81  4994.9  183.31
  4998.2  183.81  5048.2  186.18  5076.2  188.56  5120.9  191.08  5352.9  199.97
#Mann=3,-1,0
  4046.7    0.05       0  4992.2    0.03       0  4998.2    0.05       0
Bank Sta=4992.2,4998.2
Exp/Cntr=0.3,0.1

Type RM Length L Ch R = 1,5802,401,401,401
BEGIN DESCRIPTION:
UNT022 IN SPCR 10.0
END DESCRIPTION:
XS GIS Cut Line= 3
      2246137.75     13289696.88      2245737.72     13289296.85
      2245337.73     13288896.86
#Sta/Elev= 30
  4465.1  223.61  4468.7  223.61  4493.4  220.54  4507.6  219.48  4521.7  217.31
  4535.8  216.45  4550.0  214.53  4564.1  213.54  4578.3  211.42  4620.7  207.14
  4691.4  201.34  4733.8  196.71  4790.4  191.78  4875.3  186.10  4917.7  185.31
  4960.1  183.06  4999.5  182.18  5002.3  181.68  5005.5  182.18  5045.0  183.81
  5144.0  185.39  5230.9  187.86  5284.3  190.32  5356.1  192.41  5440.9  195.51
  5455.1  195.60  5483.4  197.10  5568.2  199.08  5594.2  200.49  5596.5  200.49
#Mann=6,-1,0
  4465.1    0.05       0  4999.5    0.03       0  5005.5    0.05       0
  5230.9    0.08       0  5284.3    0.05       0  5594.2     0.1       0
Bank Sta=4999.5,5005.5
Exp/Cntr=0.3,0.1

Type RM Length L Ch R = 1,5401,418,418,418
BEGIN DESCRIPTION:
UNT022 IN SPCR 9.0
END DESCRIPTION:
XS GIS Cut Line= 3
      2246387.73     13289396.87      2246037.72     13289096.85
      2245637.71     13288696.84
#Sta/Elev= 30
  4558.4  232.32  4594.1  227.32  4608.4  224.46  4650.6  219.52  4664.3  216.97
  4678.6  215.80  4692.9  213.28  4707.1  212.14  4729.1  208.07  4742.8  206.97
  4756.5  204.59  4807.0  198.27  4827.9  196.34  4835.0  194.82  4877.3  190.95
  4884.9  189.48  4927.2  186.19  4934.3  184.79  4955.2  184.09  4962.9  182.58
  4983.7  181.17  4988.4  179.49  4991.2  178.99  4994.4  179.49  5090.1  182.23
  5160.8  181.82  5245.7  182.80  5407.0  187.87  5490.7  191.06  5585.1  195.23
#Mann=5,-1,0
  4558.4    0.05       0  4988.4    0.03       0  4994.4    0.05       0
  5407.0    0.08       0  5490.7    0.05       0
Bank Sta=4988.4,4994.4
Exp/Cntr=0.3,0.1

Type RM Length L Ch R = 1,4983,407,407,407
BEGIN DESCRIPTION:
UNT022 IN SPCR 8.0
END DESCRIPTION:
XS GIS Cut Line= 3
      2246437.70     13289096.83      2246087.72     13288696.85
      2245737.71     13288596.85
#Sta/Elev= 30
  4453.7  207.64  4495.9  205.32  4503.5  203.26  4510.1  203.72  4517.7  202.99
  4524.4  202.27  4532.0  200.69  4546.2  198.98  4560.0  198.09  4567.1  197.03
  4609.8  193.92  4624.0  192.28  4638.3  191.71  4680.0  188.64  4822.4  181.37
  4850.9  180.65  4957.2  179.79  4971.4  178.81  4978.1  177.87  4987.8  177.67
  4999.1  176.44  5001.8  175.94  5005.1  176.44  5016.4  177.11  5026.8  179.23
  5041.1  179.42  5074.9  181.69  5113.0  183.21  5214.3  187.16  5349.2  192.93
#Mann=5,-1,0
  4453.7    0.05       0  4999.1    0.03       0  5005.1    0.05       0
  5113.0    0.08       0  5214.3    0.05       0
Bank Sta=4999.1,5005.1
Exp/Cntr=0.3,0.1

Type RM Length L Ch R = 1,4576,288,288,288
BEGIN DESCRIPTION:
UNT022 IN SPCR 7.0
END DESCRIPTION:
XS GIS Cut Line= 2
      2246935.68     13288350.87      2245761.09     13288316.19
#Sta/Elev= 30
  4302.4  190.17  4350.4  190.92  4390.4  191.06  4480.4  189.50  4600.5  184.39
  4650.5  182.79  4710.5  180.21  4750.6  178.08  4780.6  177.59  4790.6  178.16
  4810.6  177.21  4820.6  177.33  4840.6  176.77  4877.6  175.18  4880.4  174.68
  4883.6  175.18  5096.1  175.18  5120.7  175.18  5130.7  175.68  5140.7  177.33
  5150.7  180.09  5160.7  181.35  5236.7  184.31  5270.8  186.12  5285.7  186.28
  5290.8  186.88  5310.8  187.71  5400.8  190.08  5470.9  190.99  5477.5  191.52
#Mann=5,-1,0
  4302.4    0.05       0  4877.6   0.033       0  4883.6    0.05       0
  5096.1    0.08       0  5236.7    0.05       0
Bank Sta=4877.6,4883.6
Exp/Cntr=0.3,0.1

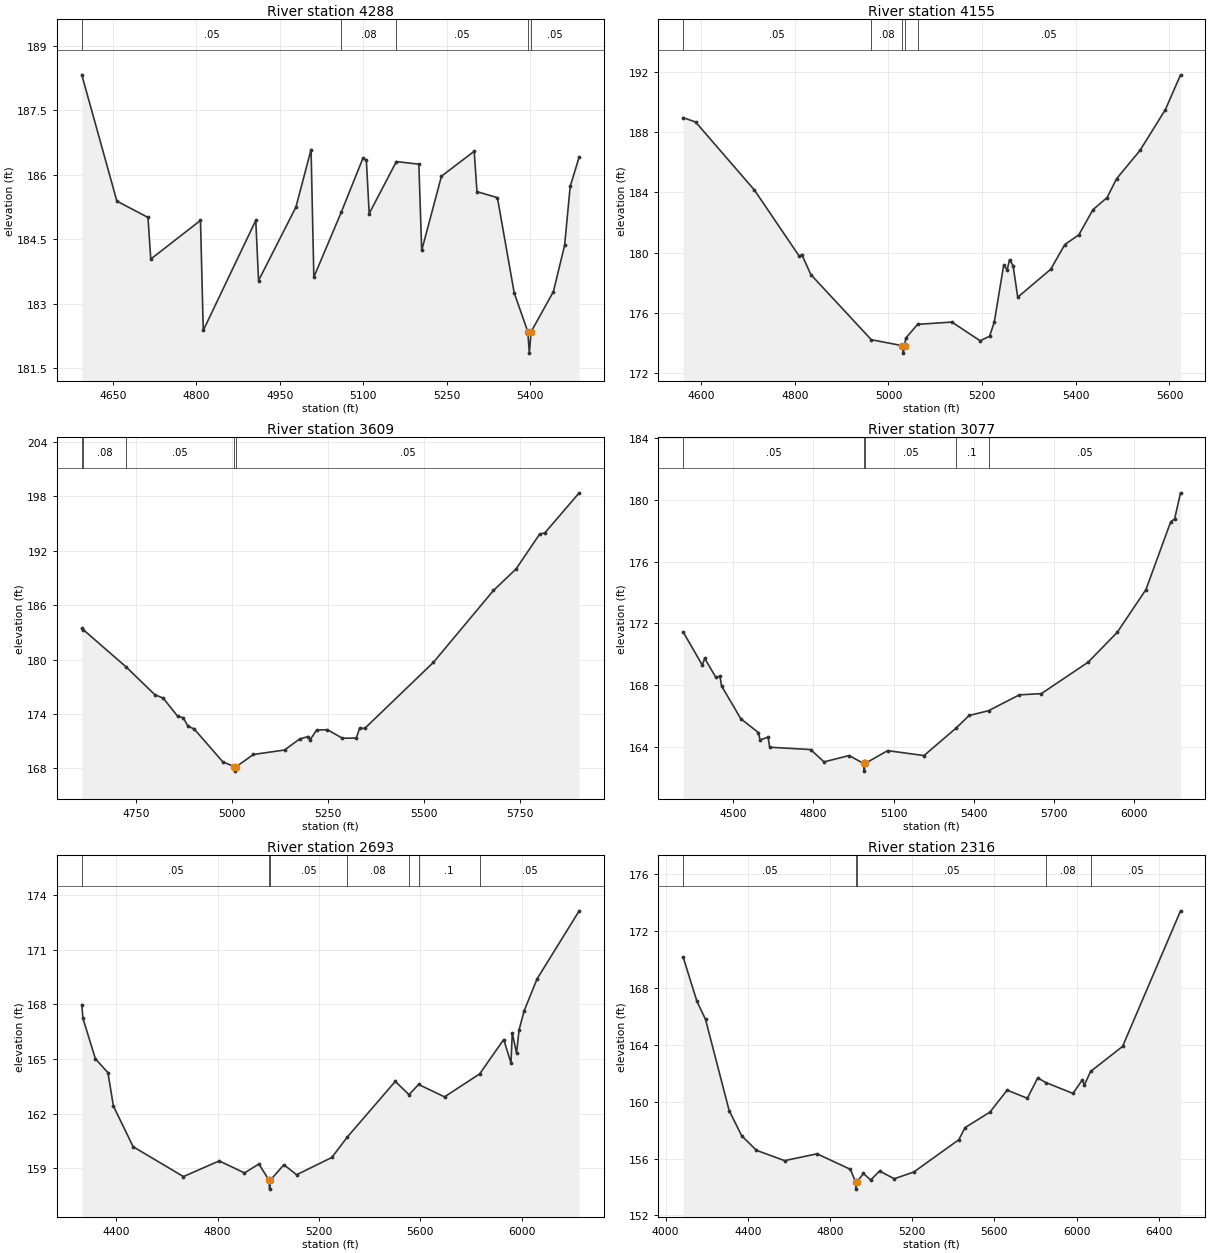
Type RM Length L Ch R = 1,4288,133,133,133
BEGIN DESCRIPTION:
Mapping XS 2d851acb
END DESCRIPTION:
XS GIS Cut Line= 2
      2246740.36     13288029.68      2245851.61     13288120.72
#Sta/Elev= 30
  4594.5  188.33  4657.5  185.39  4713.4  185.01  4718.4  184.04  4807.7  184.94
  4812.7  182.38  4907.0  184.94  4912.0  183.54  4979.1  185.25  5006.3  186.59
  5011.3  183.62  5060.5  185.13  5099.8  186.40  5105.6  186.34  5110.7  185.10
  5159.5  186.31  5199.9  186.25  5205.0  184.24  5240.5  185.97  5299.3  186.55
  5304.3  185.61  5341.0  185.47  5371.2  183.25  5395.6  182.35  5398.3  181.85
  5401.6  182.35  5441.5  183.28  5461.7  184.36  5471.7  185.73  5487.9  186.42
#Mann=5,-1,0
  4594.5    0.05       0  5060.5    0.08       0  5159.5    0.05       0
  5395.6    0.03       0  5401.6    0.05       0
Bank Sta=5395.6,5401.6
Exp/Cntr=0.3,0.1

Type RM Length L Ch R = 1,4155,546,546,546
BEGIN DESCRIPTION:
UNT022 IN SPCR 6.0
END DESCRIPTION:
XS GIS Cut Line= 2
      2246779.35     13287899.48      2245721.54     13287994.86
#Sta/Elev= 30
  4561.5  188.95  4588.1  188.66  4713.7  184.15  4809.9  179.74  4814.9  179.87
  4834.2  178.54  4963.3  174.22  5028.7  173.83  5031.5  173.33  5034.7  173.83
  5036.7  174.32  5062.2  175.24  5135.4  175.39  5195.7  174.15  5215.8  174.45
  5225.8  175.38  5245.9  179.15  5253.5  178.87  5258.5  179.53  5266.0  179.14
  5276.0  177.04  5346.3  178.89  5376.4  180.53  5406.5  181.18  5436.7  182.85
  5466.8  183.65  5486.9  184.89  5537.1  186.78  5591.2  189.48  5623.6  191.79
#Mann=5,-1,0
  4561.5    0.05       0  4963.3    0.08       0  5028.7    0.07       0
  5034.7    0.08       0  5062.2    0.05       0
Bank Sta=5028.7,5034.7
Exp/Cntr=0.3,0.1

Type RM Length L Ch R = 1,3609,532,532,532
BEGIN DESCRIPTION:
UNT022 IN SPCR 5.0
END DESCRIPTION:
XS GIS Cut Line= 3
      2246687.71     13287596.85      2246337.72     13287396.85
      2245537.74     13287796.84
#Sta/Elev= 30
  4607.5  183.44  4611.9  183.28  4723.1  179.19  4798.2  176.12  4819.8  175.75
  4857.3  173.76  4872.4  173.57  4884.6  172.64  4900.5  172.35  4975.3  168.72
  5004.7  168.19  5007.5  167.69  5010.7  168.19  5055.3  169.53  5136.4  170.02
  5175.5  171.23  5197.9  171.51  5203.5  171.17  5220.2  172.23  5248.2  172.26
  5287.3  171.32  5323.6  171.34  5332.0  172.41  5346.0  172.42  5524.9  179.70
  5681.4  187.63  5740.1  189.99  5801.6  193.83  5815.6  193.99  5905.0  198.40
#Mann=5,-1,0
  4607.5    0.05       0  4611.9    0.08       0  4723.1    0.05       0
  5004.7    0.03       0  5010.7    0.05       0
Bank Sta=5004.7,5010.7
Exp/Cntr=0.3,0.1

Type RM Length L Ch R = 1,3077,384,384,384
BEGIN DESCRIPTION:
UNT022 IN SPCR 4.0
END DESCRIPTION:
XS GIS Cut Line= 3
      2247144.85     13287330.04      2246360.12     13286802.25
      2245472.00     13287017.34
#Sta/Elev= 30
  4313.5  171.45  4385.1  169.29  4394.1  169.73  4436.1  168.49  4451.1  168.57
  4457.1  167.94  4529.1  165.81  4595.1  164.91  4601.1  164.43  4631.1  164.62
  4637.1  163.96  4790.1  163.81  4840.3  163.01  4934.0  163.42  4988.0  162.91
  4990.8  162.41  4994.0  162.91  5078.0  163.74  5213.9  163.42  5333.0  165.19
  5382.5  166.02  5455.1  166.33  5570.3  167.36  5652.7  167.44  5827.6  169.48
  5936.4  171.42  6043.6  174.19  6136.2  178.59  6150.7  178.77  6173.0  180.47
#Mann=5,-1,0
  4313.5    0.05       0  4988.0    0.03       0  4994.0    0.05       0
  5333.0     0.1       0  5455.1    0.05       0
Bank Sta=4988,4994
Exp/Cntr=0.3,0.1

Type RM Length L Ch R = 1,2693,377,377,377
BEGIN DESCRIPTION:
UNT022 IN SPCR 3.0
END DESCRIPTION:
XS GIS Cut Line= 3
      2247318.44     13287211.96      2246679.57     13286489.75
      2245693.46     13286642.53
#Sta/Elev= 30
  4264.3  167.98  4268.7  167.24  4318.0  165.01  4367.4  164.25  4389.1  162.41
  4466.9  160.18  4665.2  158.54  4806.5  159.40  4906.1  158.74  4962.9  159.23
  5002.4  158.35  5005.2  157.85  5008.4  158.35  5061.6  159.19  5111.8  158.64
  5250.6  159.59  5312.2  160.72  5501.0  163.77  5554.9  163.04  5593.0  163.60
  5695.1  162.92  5833.7  164.18  5928.6  166.07  5957.3  164.78  5962.4  166.44
  5979.2  165.32  5989.3  166.61  6009.6  167.66  6060.2  169.40  6226.4  173.14
#Mann=7,-1,0
  4264.3    0.05       0  5002.4    0.03       0  5008.4    0.05       0
  5312.2    0.08       0  5554.9    0.05       0  5593.0     0.1       0
  5833.7    0.05       0
Bank Sta=5002.4,5008.4
Exp/Cntr=0.3,0.1

Type RM Length L Ch R = 1,2316,172,172,172
BEGIN DESCRIPTION:
Mapping XS 27010bb2
END DESCRIPTION:
XS GIS Cut Line= 5
      2247435.50     13287251.28      2247234.97     13286581.97
      2246966.74     13286256.45      2246287.06     13286355.41
      2245699.53     13286532.19
#Sta/Elev= 30
  4085.2  170.15  4152.5  167.03  4194.2  165.77  4309.1  159.37  4370.0  157.60
  4441.4  156.58  4579.0  155.85  4737.0  156.33  4899.1  155.24  4924.8  154.35
  4927.5  153.85  4930.8  154.35  4962.9  154.95  4998.1  154.49  5041.1  155.12
  5112.8  154.58  5207.7  155.05  5427.0  157.32  5457.3  158.17  5578.6  159.26
  5662.1  160.80  5760.5  160.23  5811.0  161.66  5851.0  161.33  5982.5  160.57
  6027.6  161.51  6038.1  161.16  6068.1  162.11  6224.0  163.87  6506.1  173.39
#Mann=5,-1,0
  4085.2    0.05       0  4924.8    0.03       0  4930.8    0.05       0
  5851.0    0.08       0  6068.1    0.05       0
Bank Sta=4924.8,4930.8
Exp/Cntr=0.3,0.1

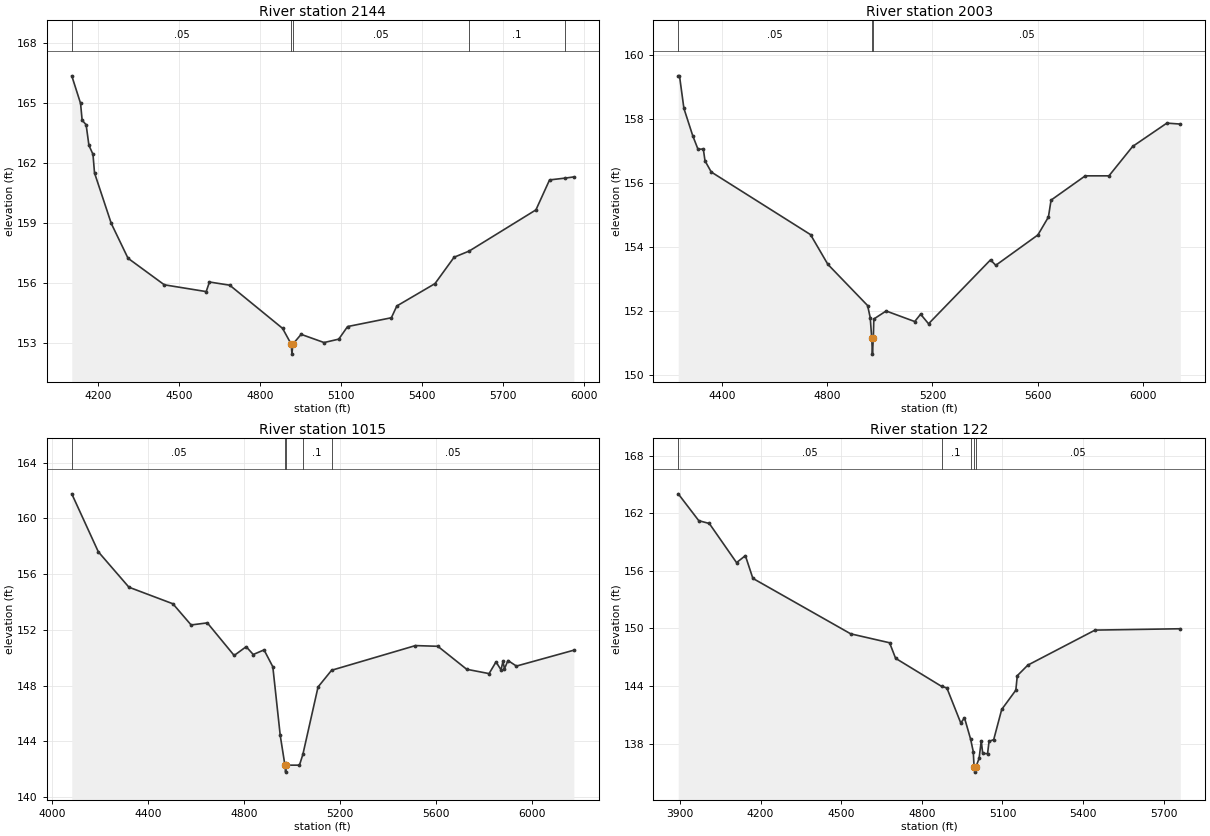
Type RM Length L Ch R = 1,2144,141,141,141
BEGIN DESCRIPTION:
Mapping XS 79b43b68
END DESCRIPTION:
XS GIS Cut Line= 4
      2247442.77     13287158.32      2247204.91     13286262.44
      2246986.16     13286166.95      2246298.69     13286267.64
#Sta/Elev= 30
  4102.6  166.37  4135.2  164.99  4141.0  164.15  4155.8  163.92  4166.2  162.89
  4181.2  162.44  4186.9  161.51  4249.0  158.98  4311.0  157.24  4445.5  155.91
  4600.7  155.57  4612.8  156.05  4688.0  155.89  4883.7  153.73  4915.7  152.94
  4918.5  152.44  4921.7  152.94  4952.5  153.43  5037.4  153.02  5091.9  153.19
  5124.6  153.82  5286.8  154.26  5307.1  154.85  5448.5  155.97  5519.3  157.29
  5575.3  157.60  5822.5  159.66  5873.0  161.16  5930.6  161.25  5963.0  161.31
#Mann=5,-1,0
  4102.6    0.05       0  4915.7    0.03       0  4921.7    0.05       0
  5575.3     0.1       0  5930.6    0.05       0
Bank Sta=4915.7,4921.7
Exp/Cntr=0.3,0.1

Type RM Length L Ch R = 1,2003,988,988,988
BEGIN DESCRIPTION:
Mapping XS 4ccc5288
END DESCRIPTION:
XS GIS Cut Line= 3
      2247435.64     13287011.46      2247314.11     13286047.91
      2246376.60     13286091.32
#Sta/Elev= 30
  4232.9  159.35  4237.7  159.35  4254.5  158.33  4287.9  157.48  4308.1  157.05
  4328.3  157.06  4334.7  156.69  4358.5  156.34  4736.1  154.38  4802.0  153.45
  4953.2  152.16  4963.2  151.78  4968.9  151.14  4971.6  150.64  4974.9  151.14
  4976.9  151.74  5023.7  151.99  5132.4  151.66  5154.8  151.89  5185.0  151.59
  5420.7  153.59  5440.7  153.42  5600.9  154.37  5640.9  154.93  5651.0  155.46
  5781.1  156.22  5871.2  156.22  5961.3  157.14  6091.4  157.87  6142.6  157.84
#Mann=3,-1,0
  4232.9    0.05       0  4968.9    0.03       0  4974.9    0.05       0
Bank Sta=4968.9,4974.9
Exp/Cntr=0.3,0.1

Type RM Length L Ch R = 1,1015,893,893,893
BEGIN DESCRIPTION:
UNT022 IN SPCR 2.0
END DESCRIPTION:
XS GIS Cut Line= 3
      2247791.56     13287028.78      2248277.66     13286082.63
      2247643.98     13285275.34
#Sta/Elev= 30
  4082.3  161.76  4192.8  157.60  4320.2  155.06  4503.3  153.87  4579.1  152.35
  4646.6  152.50  4758.3  150.16  4808.3  150.79  4837.7  150.23  4882.7  150.56
  4919.2  149.35  4950.1  144.42  4969.6  142.29  4972.4  141.79  4975.6  142.29
  5030.1  142.29  5044.3  143.06  5107.5  147.90  5163.9  149.10  5513.0  150.87
  5606.1  150.82  5726.3  149.17  5819.4  148.86  5848.3  149.70  5869.1  149.13
  5877.2  149.73  5883.6  149.21  5898.0  149.80  5933.3  149.40  6172.3  150.54
#Mann=5,-1,0
  4082.3    0.05       0  4969.6    0.03       0  4975.6    0.05       0
  5044.3     0.1       0  5163.9    0.05       0
Bank Sta=4969.6,4975.6
Exp/Cntr=0.3,0.1

Type RM Length L Ch R = 1,122,0,0,0
BEGIN DESCRIPTION:
UNT022 IN SPCR 1.0
END DESCRIPTION:
XS GIS Cut Line= 4
      2248598.83     13287080.91      2249050.23     13286178.12
      2248946.06     13285935.07      2248425.22     13285648.61
#Sta/Elev= 30
  3893.5  164.02  3970.0  161.22  4009.1  160.93  4110.5  156.85  4143.3  157.58
  4171.2  155.21  4535.3  149.43  4679.9  148.50  4702.3  146.88  4873.2  143.96
  4893.1  143.79  4944.8  140.14  4958.6  140.68  4981.4  138.46  4991.3  137.15
  4994.4  135.52  4997.1  135.02  5000.4  135.52  5013.0  136.45  5021.0  138.27
  5026.4  136.97  5044.5  136.94  5050.0  138.22  5067.4  138.41  5097.1  141.55
  5149.7  143.56  5155.1  145.07  5194.3  146.17  5444.4  149.82  5761.7  149.96
#Mann=5,-1,0
  3893.5    0.05       0  4873.2     0.1       0  4981.4    0.05       0
  4994.4    0.03       0  5000.4    0.05       0
Bank Sta=4994.4,5000.4
Exp/Cntr=0.3,0.1

Chan Stop Cuts=-1