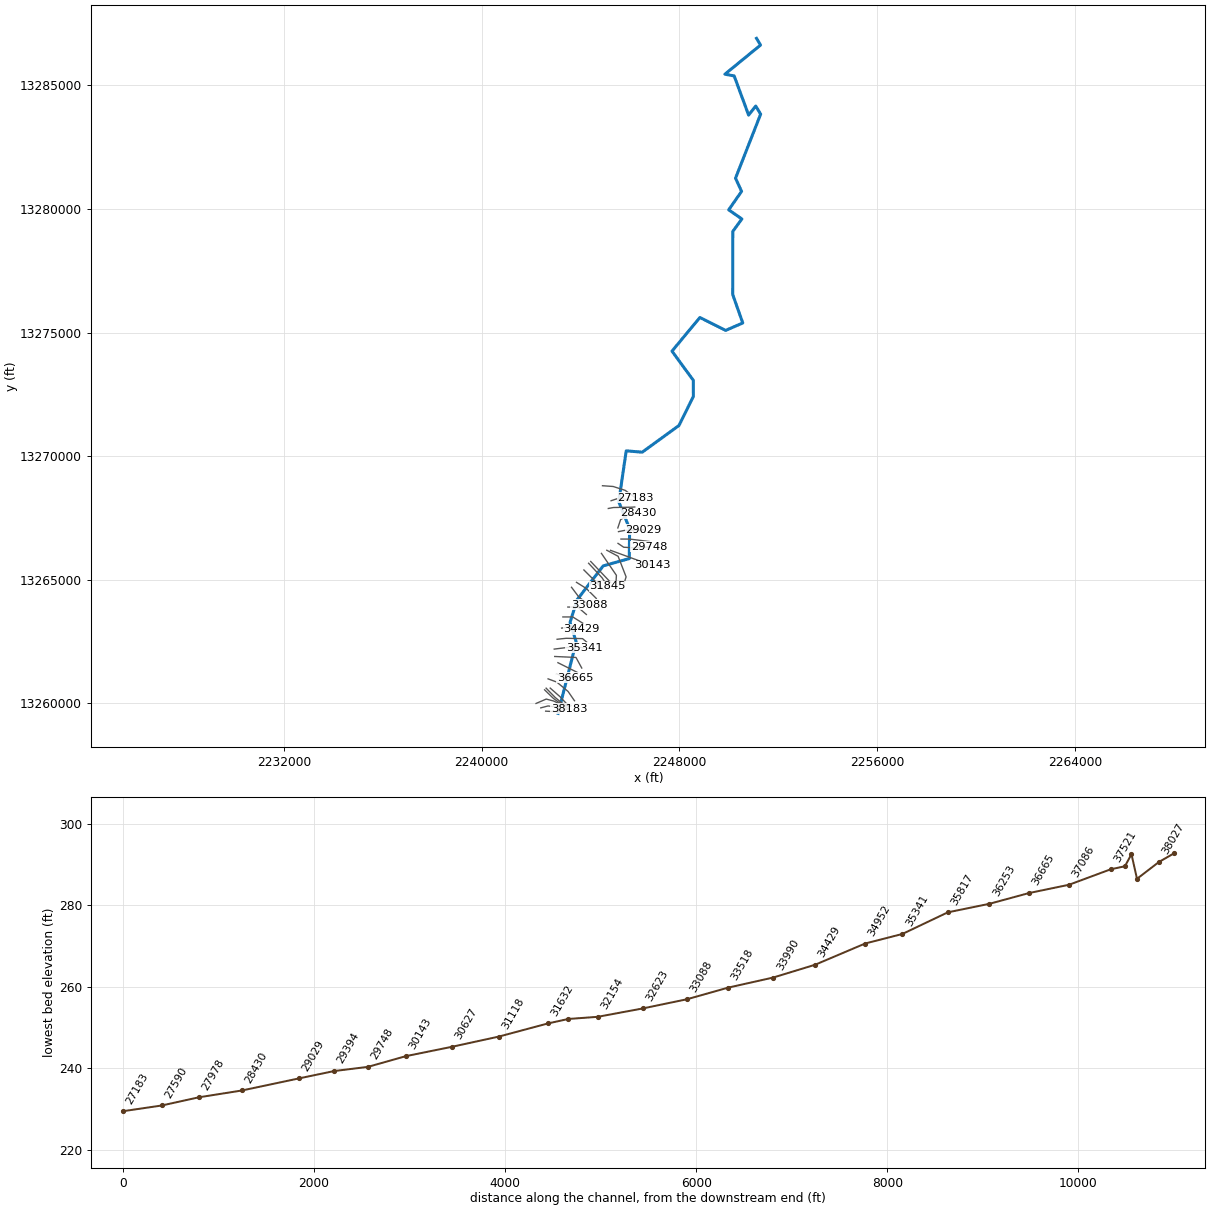
--- UNT023 IN SPCR.prj (project) ---

Proj Title=UNT023 IN SPCR Base Level Engineering
Current Plan=p01
Default Exp/Contr=0.3,0.1
English Units
Geom File=g01
Flow File=f01
Plan File=p01
Y Axis Title=Elevation
X Axis Title(PF)=Main Channel Distance
X Axis Title(XS)=Station
BEGIN DESCRIPTION:
UNT023 IN SPCR
END DESCRIPTION:
DSS Export Rating Curves= 0
DSS Export Rating Curve Sorted= 0
DSS Export Volume Flow Curves= 0
DXF OffsetX= 0
DXF OffsetY= 0
DXF ScaleX= 1
DXF ScaleY= 10

--- UNT023 IN SPCR.p01 (plan) ---

Plan Title=Multiple Run
Short Identifier=Multiple
Geom File=g01
Flow File=f01
Subcritical Flow
K Sum by GR= 0
Std Step Tol= 0.01
Critical Tol= 0.01
Num of Std Step Trials= 20
Max Error Tol= 0.3
Flow Tol Ratio= 0.001
Split Flow NTrial= 30
Split Flow Tol= 0.02
Split Flow Ratio= 0.02
Log Output Level= 0
Friction Slope Method= 1
Unsteady Friction Slope Method= 2
Unsteady Bridges Friction Slope Method= 1
Parabolic Critical Depth
Global Vel Dist=  1 , 1 , 1
Global Log Level= 0
CheckData=True
Encroach Param= -1, 0, 0, 0
BEGIN DESCRIPTION:
Multiple Run
END DESCRIPTION:

--- UNT023 IN SPCR.f01 (steady flow) ---

Flow Title=Multiple
Program Version=4.10
Number of Profiles= 7
Profile Names=10-year,25-year,50-year,1pct_min,100-year,1pct_plu,500-year
River Rch & RM=UNT023 IN SPCR,Reach-1         ,38183
     269     380     474     436     589     797     923
River Rch & RM=UNT023 IN SPCR,Reach-1         ,37797
     343     487     610     562     760    1028    1199
River Rch & RM=UNT023 IN SPCR,Reach-1         ,30143
     581     846    1076    1005    1359    1837    2202
River Rch & RM=UNT023 IN SPCR,Reach-1         ,29748
     581     846    1076    1005    1359    1837    2202
River Rch & RM=UNT023 IN SPCR,Reach-1         ,23004
     631     921    1173    1097    1483    2006    2409
River Rch & RM=UNT023 IN SPCR,Reach-1         ,19630
     912    1350    1737    1639    2217    2998    3666
River Rch & RM=UNT023 IN SPCR,Reach-1         ,19186
     912    1350    1737    1639    2217    2998    3666
River Rch & RM=UNT023 IN SPCR,Reach-1         ,15966
     914    1353    1740    1642    2220    3003    3671
River Rch & RM=UNT023 IN SPCR,Reach-1         ,15024
    1141    1703    2204    2091    2828    3824    4726
River Rch & RM=UNT023 IN SPCR,Reach-1         ,14522
    1140    1700    2199    2083    2817    3810    4701
River Rch & RM=UNT023 IN SPCR,Reach-1         ,10921
    1170    1738    2242    2118    2864    3874    4750
River Rch & RM=UNT023 IN SPCR,Reach-1         ,8960
    1170    1738    2242    2118    2864    3874    4750
Boundary for River Rch & Prof#=UNT023 IN SPCR,Reach-1         , 1
Up Type= 0
Dn Type= 3
Dn Slope=0.005
Boundary for River Rch & Prof#=UNT023 IN SPCR,Reach-1         , 2
Up Type= 0
Dn Type= 3
Dn Slope=0.005
Boundary for River Rch & Prof#=UNT023 IN SPCR,Reach-1         , 3
Up Type= 0
Dn Type= 3
Dn Slope=0.005
Boundary for River Rch & Prof#=UNT023 IN SPCR,Reach-1         , 4
Up Type= 0
Dn Type= 3
Dn Slope=0.005
Boundary for River Rch & Prof#=UNT023 IN SPCR,Reach-1         , 5
Up Type= 0
Dn Type= 3
Dn Slope=0.005
Boundary for River Rch & Prof#=UNT023 IN SPCR,Reach-1         , 6
Up Type= 0
Dn Type= 3
Dn Slope=0.005
Boundary for River Rch & Prof#=UNT023 IN SPCR,Reach-1         , 7
Up Type= 0
Dn Type= 3
Dn Slope=0.005
DSS Import GetInterval= 0
DSS Import GetPeak= 0
DSS Import FillOption= 0

--- UNT023 IN SPCR.g01 (geometry) ---

Geom Title=Existing Conditions
Program Version=4.10

River Reach=UNT023 IN SPCR  ,Reach-1
Reach XY= 30
      2243094.14     13259597.24      2243826.39     13262482.22
      2243577.81     13263276.69      2243863.63     13264192.74
      2244916.43     13265561.01      2245972.65     13265857.67
      2245986.31     13267061.16      2245548.11     13268156.38
      2245848.97     13270214.18      2246496.21     13270160.65
       2247981.7     13271238.05       2248565.3     13272412.66
      2248563.75     13273065.21      2247700.12     13274245.86
      2248829.74     13275608.36      2249870.54     13275084.92
      2250563.25     13275386.14      2250155.79     13276536.14
       2250159.2     13279086.52      2250526.97     13279591.91
      2249994.29     13279960.82      2250515.09      13280708.1
      2250269.94     13281241.09      2251286.29      13283831.8
      2251087.83     13284157.14      2250799.41     13283792.82
      2250215.39     13285376.14      2249840.03     13285445.43
      2251283.17     13286625.34      2251117.72     13286896.85

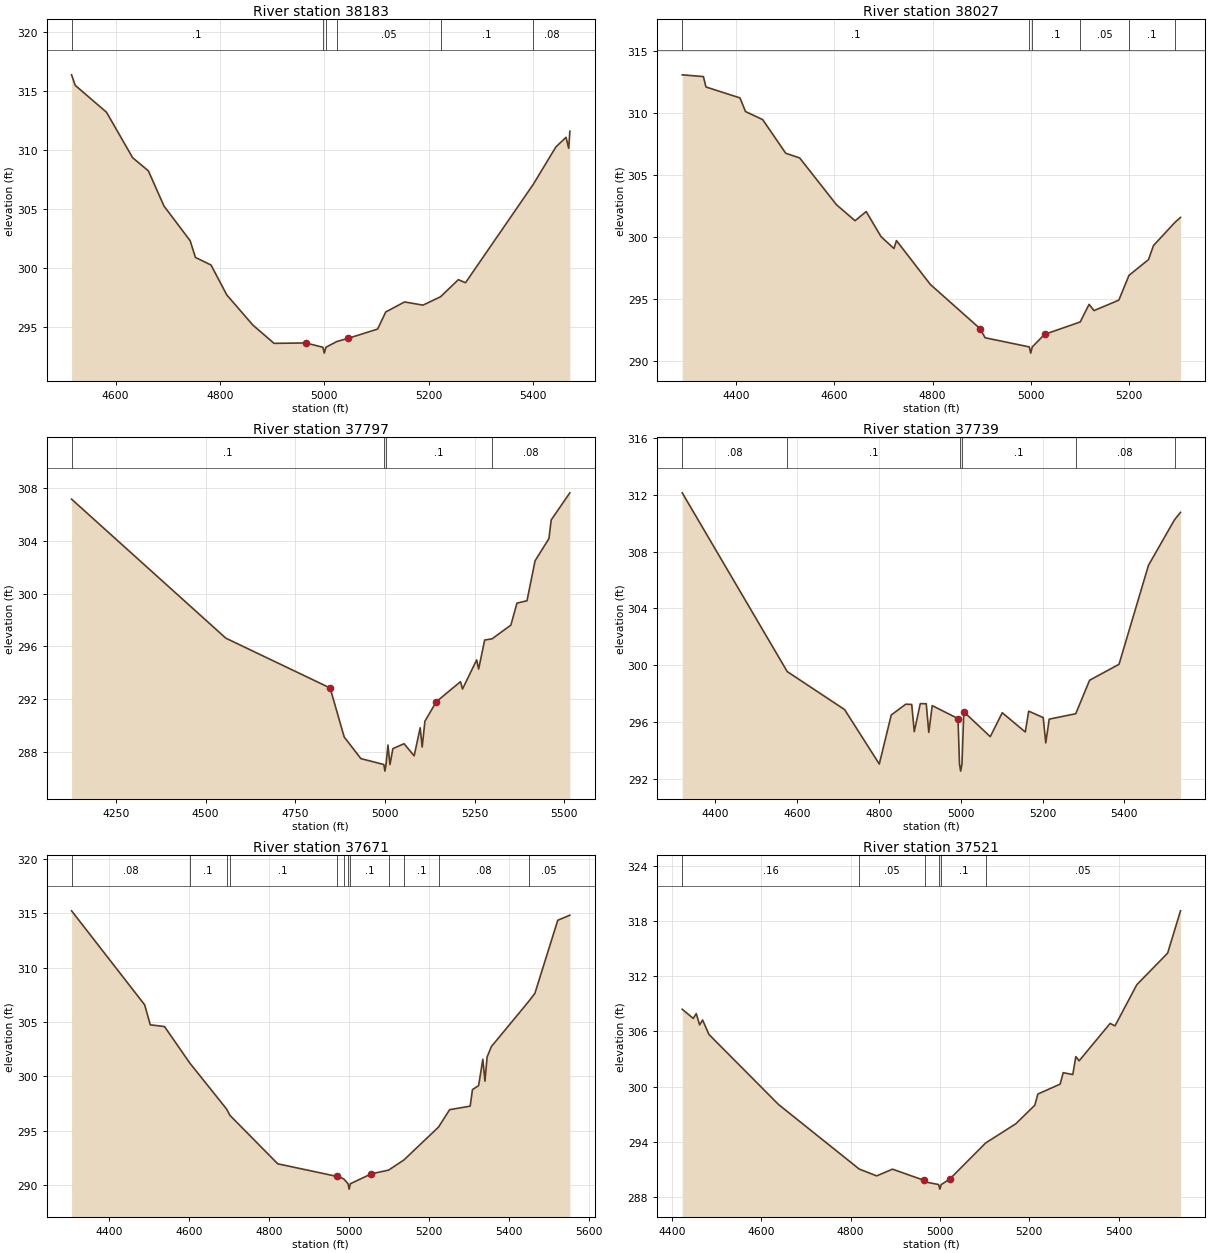
Type RM Length L Ch R = 1 ,38183   ,156,156,156
BEGIN DESCRIPTION:
UNT023 IN SPCR 68.0
END DESCRIPTION:
XS GIS Cut Line= 3
      2242590.87     13259686.88      2242948.46     13259668.19
      2243533.93     13259782.48
#Sta/Elev= 30
  4515.6  316.36  4522.5  315.47  4582.5  313.19  4632.6  309.33  4662.7  308.22
  4692.7  305.23  4742.8  302.29  4752.8  300.88  4782.8  300.23  4812.9   297.7
  4862.9  295.14  4903.5  293.59  4964.6  293.62    4997  293.26  4999.8  292.76
    5003  293.26  5023.6  293.74  5045.2  294.01  5101.9   294.8  5117.5  296.25
  5153.5   297.1  5188.8  296.83  5222.5  297.54  5256.6  298.99  5270.3  298.73
  5400.5   307.1  5443.5  310.25  5462.9  311.06    5468  310.13  5470.2  311.58
#Mann= 6 ,-1 , 0
  4515.6      .1       0    4997     .07       0    5003      .1       0
  5023.6     .05       0  5222.5      .1       0  5400.5     .08       0
Bank Sta=4964.6,5045.2
XS Rating Curve= 0 ,0
Exp/Cntr=0.3,0.1

Type RM Length L Ch R = 1 ,38027   ,230,230,230
BEGIN DESCRIPTION:
Mapping XS 70151d92
END DESCRIPTION:
XS GIS Cut Line= 3
      2242393.99     13259820.03      2242689.16     13259898.16
      2243392.25     13259807.02
#Sta/Elev= 30
  4290.4  313.09  4333.5  312.95  4338.7  312.11    4408  311.23  4419.2  310.13
  4454.2  309.48  4501.1  306.77  4529.5  306.39  4604.4  302.62  4642.2  301.33
  4664.9  302.07  4695.1  300.05  4721.4  299.09  4726.5  299.73  4795.6  296.19
  4896.8  292.63  4906.9   291.9    4997  291.16  4999.8  290.66    5003  291.16
  5027.9  292.17  5100.5  293.17  5118.6  294.59  5128.7  294.09  5179.1  294.93
  5199.9  296.93  5239.6   298.2  5249.7  299.33  5293.4   301.2  5304.7   301.6
#Mann= 6 ,-1 , 0
  4290.4      .1       0    4997     .07       0    5003      .1       0
  5100.5     .05       0  5199.9      .1       0  5293.4     .08       0
Bank Sta=4896.8,5027.9
XS Rating Curve= 0 ,0
Exp/Cntr=0.3,0.1

Type RM Length L Ch R = 1 ,37797   ,58,58,58
BEGIN DESCRIPTION:
Mapping XS cf3187eb
END DESCRIPTION:
XS GIS Cut Line= 4
      2242202.84     13259998.85      2242614.75     13260175.77
      2242918.82     13260095.61      2243479.97     13259819.18
#Sta/Elev= 30
  4126.8  307.16  4556.6  296.61  4847.1  292.83  4886.4  289.11  4932.9  287.47
    4997  287.02  4999.8  286.52    5003  287.02  5008.3   288.5  5013.9  287.02
  5022.1  288.23  5053.2   288.6  5081.3  287.68  5098.1  289.81  5103.7  288.35
  5111.3  290.31  5143.1  291.79  5210.5  293.31    5216  292.75  5255.4  294.96
    5261  294.27  5277.8  296.47  5298.3  296.56  5350.8   297.6  5367.7  299.27
  5395.7  299.45  5418.2  302.48  5456.9  304.17  5463.1  305.58  5515.1  307.64
#Mann= 4 ,-1 , 0
  4126.8      .1       0    4997     .07       0    5003      .1       0
  5298.3     .08       0
Bank Sta=4847.1,5143.1
XS Rating Curve= 0 ,0
Exp/Cntr=0.3,0.1

Type RM Length L Ch R = 1 ,37739   ,68,68,68
BEGIN DESCRIPTION:
Mapping XS 846619e3
END DESCRIPTION:
XS GIS Cut Line= 4
       2242548.8     13260549.28      2242901.72     13260205.71
      2243252.28      13259946.3      2243533.87     13259878.81
#Sta/Elev= 30
  4319.1  312.12  4575.8  299.57  4716.1   296.9  4800.9  293.08  4830.1  296.52
  4865.6  297.28  4880.2  297.26  4886.4  295.35  4901.1  297.32  4915.7  297.31
  4921.9   295.3  4930.3  297.18  4993.3  296.27    4997  293.08  4999.8  292.58
    5003  293.08  5007.5  296.75  5072.2     295  5101.5  296.68  5157.8  295.33
  5166.2  296.79  5201.6  296.34  5207.9  294.56  5216.3  296.23  5281.2  296.61
    5315  298.96    5387  300.08    5459  307.03  5522.7  310.23  5537.3  310.75
#Mann= 6 ,-1 , 0
  4319.1     .08       0  4575.8      .1       0    4997     .07       0
    5003      .1       0  5281.2     .08       0  5522.7     .05       0
Bank Sta=4993.3,5007.5
XS Rating Curve= 0 ,0
Exp/Cntr=0.3,0.1

Type RM Length L Ch R = 1 ,37671   ,150,150,150
BEGIN DESCRIPTION:
Mapping XS 47e8e494
END DESCRIPTION:
XS GIS Cut Line= 4
       2242609.6     13260617.02      2242976.51     13260240.77
      2243261.63     13260007.06      2243593.15     13259892.67
#Sta/Elev= 30
  4306.3  315.22  4488.9  306.57    4503  304.73  4538.5  304.57  4601.3  301.23
  4693.8  296.97  4701.7  296.41  4821.4  291.94  4968.2  290.79  4970.6  290.84
  4986.5  290.54    4997  290.11  4999.8  289.61    5003  290.11  5055.3  291.02
  5098.4  291.36  5136.8   292.3  5223.1  295.32  5250.8  296.92  5302.2  297.25
  5307.9  298.77  5323.3  299.14  5333.8  301.56  5339.1  299.55  5344.5  301.77
    5355  302.72  5448.3  306.88  5463.9  307.63    5521  314.35  5551.2  314.82
#Mann= 12 ,-1 , 0
  4306.3     .08       0  4601.3      .1       0  4693.8     .08       0
  4701.7      .1       0  4968.2     .08       0  4986.5      .1       0
    4997     .07       0    5003      .1       0  5098.4     .08       0
  5136.8      .1       0  5223.1     .08       0  5448.3     .05       0
Bank Sta=4970.6,5055.3
XS Rating Curve= 0 ,0
Exp/Cntr=0.3,0.1

Type RM Length L Ch R = 1 ,37521   ,435,435,435
BEGIN DESCRIPTION:
UNT023 IN SPCR 67.0
END DESCRIPTION:
XS GIS Cut Line= 4
      2242775.53     13260619.37      2243172.82     13260271.15
      2243434.57      13259990.7       2243624.5     13259916.58
#Sta/Elev= 30
  4422.9  308.41  4447.6  307.41  4454.3  307.93  4461.9  306.71  4468.5  307.24
  4482.7  305.67  4638.6  298.05  4819.3  291.03  4858.5  290.29  4893.7  291.02
  4964.8   289.8  4967.3  289.63    4997  289.35  4999.8  288.85    5003  289.35
  5021.5  289.92  5102.2  293.86    5170  295.96  5212.5  297.98  5219.3  299.19
  5269.2  300.27    5276  301.51  5297.5  301.31  5304.3  303.26  5311.7   302.8
  5381.1  306.87    5392   306.6  5440.9  311.08  5509.9  314.51  5538.7  319.11
#Mann= 6 ,-1 , 0
  4422.9     .16       0  4819.3     .05       0  4967.3      .1       0
    4997     .07       0    5003      .1       0  5102.2     .05       0
Bank Sta=4964.8,5021.5
XS Rating Curve= 0 ,0
Exp/Cntr=0.3,0.1

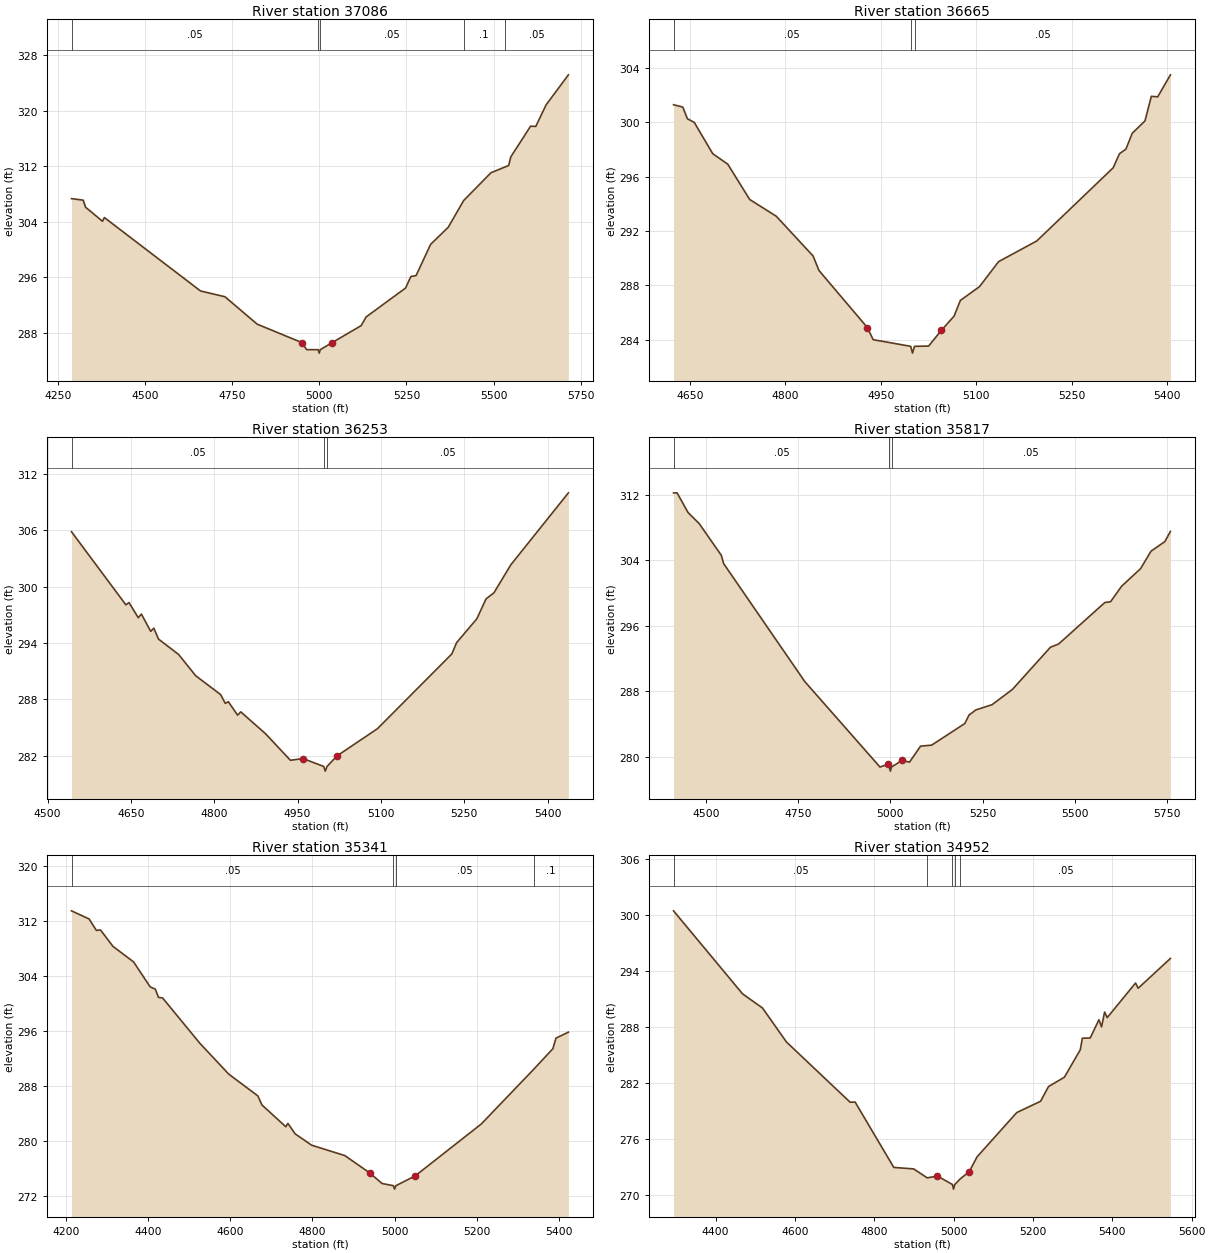
Type RM Length L Ch R = 1 ,37086   ,421,421,421
BEGIN DESCRIPTION:
Mapping XS 3a0afcfd
END DESCRIPTION:
XS GIS Cut Line= 4
      2242690.01     13260992.99      2243041.61     13260862.76
      2243497.34     13260485.16      2243757.77     13260107.53
#Sta/Elev= 30
  4289.2  307.31  4322.7  307.09  4329.4  306.08  4378.1  304.05  4383.4  304.59
  4659.4  294.01  4729.4  293.18  4821.9  289.23  4949.5  286.59  4963.8  285.56
    4997  285.56  4999.8  285.06    5003  285.56  5035.5  286.53  5120.1  289.02
  5134.4  290.27  5247.7  294.44  5262.7  296.09  5277.6  296.22  5319.5  300.73
  5370.2   303.2  5414.1  307.03  5492.6  311.04  5531.6  311.84  5543.3  312.08
  5549.4  313.32  5606.2  317.74  5621.1  317.71  5650.8  320.82  5714.7  325.14
#Mann= 5 ,-1 , 0
  4289.2     .05       0    4997     .03       0    5003     .05       0
  5414.1      .1       0  5531.6     .05       0
Bank Sta=4949.5,5035.5
XS Rating Curve= 0 ,0
Exp/Cntr=0.3,0.1

Type RM Length L Ch R = 1 ,36665   ,412,412,412
BEGIN DESCRIPTION:
UNT023 IN SPCR 65.0
END DESCRIPTION:
XS GIS Cut Line= 3
      2243037.73     13261196.85      2243387.72     13261046.85
      2243787.74     13261046.85
#Sta/Elev= 30
  4624.3  301.28  4638.8  301.11  4646.1  300.25  4656.9  299.98  4685.9  297.68
  4709.5  296.91    4744  294.31  4785.7  293.08  4843.7  290.15  4852.8  289.09
  4928.9  284.89    4938     284    4997  283.51  4999.8  283.01    5003  283.51
  5025.1  283.53  5045.1  284.68  5065.1  285.73  5075.1  286.89  5105.1   287.9
  5135.1  289.74  5195.1  291.26  5315.1  296.64  5325.1  297.68  5335.1  298.01
  5345.1  299.18  5365.1  300.09  5375.1   301.9  5385.1  301.86  5405.1  303.48
#Mann= 3 ,-1 , 0
  4624.3     .05       0    4997     .03       0    5003     .05       0
Bank Sta=4928.9,5045.1
XS Rating Curve= 0 ,0
Exp/Cntr=0.3,0.1

Type RM Length L Ch R = 1 ,36253   ,436,436,436
BEGIN DESCRIPTION:
UNT023 IN SPCR 64.0
END DESCRIPTION:
XS GIS Cut Line= 3
      2243087.69     13261646.87      2243487.72     13261446.85
      2243887.75     13261246.84
#Sta/Elev= 30
    4543  305.83  4640.9  298.06  4646.5   298.3  4663.2  296.69  4668.8  297.08
  4685.6  295.24  4691.2  295.58  4699.6  294.42  4735.9  292.78  4766.6  290.52
  4811.4  288.52  4819.8  287.59  4825.3  287.76  4842.1  286.33  4847.7  286.68
  4892.4  284.35  4937.1  281.53  4959.5  281.72    4997  280.88  4999.8  280.38
    5003  280.88    5021     282  5093.7  284.89  5227.8  292.85  5236.2  294.04
  5272.6  296.57  5289.3   298.7  5303.3  299.33    5334  302.33  5437.5  309.97
#Mann= 3 ,-1 , 0
    4543     .05       0    4997     .03       0    5003     .05       0
Bank Sta=4959.5,5021
XS Rating Curve= 0 ,0
Exp/Cntr=0.3,0.1

Type RM Length L Ch R = 1 ,35817   ,476,476,476
BEGIN DESCRIPTION:
UNT023 IN SPCR 63.0
END DESCRIPTION:
XS GIS Cut Line= 3
      2242958.15     13261898.09      2243817.52     13261859.03
      2244051.22     13261430.58
#Sta/Elev= 30
  4411.5  312.24  4421.1  312.25  4451.1  309.83  4481.1   308.5  4541.2  304.62
  4547.5  303.61  4767.7  289.21  4971.7  278.78  4992.9  279.11    4997  278.78
  4999.8  278.28    5003  278.78  5031.7   279.6  5051.7  279.37  5081.8  281.33
  5111.8  281.45  5201.9  284.09  5213.2  285.12  5231.9  285.75  5275.8  286.39
  5331.2  288.26  5434.1   293.4  5456.5   293.8  5581.8  298.86  5597.4  298.96
  5627.3  300.85    5679     303  5707.1  305.13  5744.5  306.29  5759.8  307.54
#Mann= 3 ,-1 , 0
  4411.5     .05       0    4997     .03       0    5003     .05       0
Bank Sta=4992.9,5031.7
XS Rating Curve= 0 ,0
Exp/Cntr=0.3,0.1

Type RM Length L Ch R = 1 ,35341   ,389,389,389
BEGIN DESCRIPTION:
UNT023 IN SPCR 62.0
END DESCRIPTION:
XS GIS Cut Line= 3
      2242937.69     13262196.85      2243737.72     13262296.85
      2244137.75     13262246.85
#Sta/Elev= 30
  4213.5  313.51  4256.4  312.32    4274  310.66  4284.1  310.72  4314.3  308.34
  4364.7  306.06    4405  302.43  4417.6  302.09  4425.2   300.9  4435.2  300.82
  4525.9  294.21  4596.5   289.7    4667  286.55  4677.1  285.22  4735.1  282.05
  4740.1  282.54  4757.7  281.02    4798  279.36  4878.7  277.85  4939.1  275.33
  4969.4  273.78    4997  273.46  4999.8  272.96    5003  273.46    5050  274.89
  5211.2  282.47  5338.3  290.41  5385.1  293.42  5392.6  294.96  5422.9  295.83
#Mann= 4 ,-1 , 0
  4213.5     .05       0    4997     .03       0    5003     .05       0
  5338.3      .1       0
Bank Sta=4939.1,5050
XS Rating Curve= 0 ,0
Exp/Cntr=0.3,0.1

Type RM Length L Ch R = 1 ,34952   ,523,523,523
BEGIN DESCRIPTION:
UNT023 IN SPCR 61.0
END DESCRIPTION:
XS GIS Cut Line= 4
      2243054.68     13262594.54      2243419.21      13262633.6
      2244083.28     13262620.58      2244252.51     13262477.38
#Sta/Elev= 30
    4294  300.49    4468  291.58  4518.3  290.06  4578.7  286.41  4739.1  279.95
  4751.8  279.96  4849.2  272.95  4899.2  272.79  4933.5  271.83  4959.2  272.02
    4997  271.12  4999.8  270.62    5003  271.12    5017  271.73  5039.2  272.49
  5059.2  274.09  5159.2  278.84  5219.2  280.05  5239.2  281.63  5279.2  282.63
  5319.3  285.58  5324.5  286.82  5344.3  286.84  5366.3   288.8  5372.9  288.03
  5380.6  289.63  5387.2  289.03  5458.6  292.74  5465.2  292.18  5546.5  295.38
#Mann= 5 ,-1 , 0
    4294     .05       0  4933.5      .1       0    4997     .07       0
    5003      .1       0    5017     .05       0
Bank Sta=4959.2,5039.2
XS Rating Curve= 0 ,0
Exp/Cntr=0.3,0.1

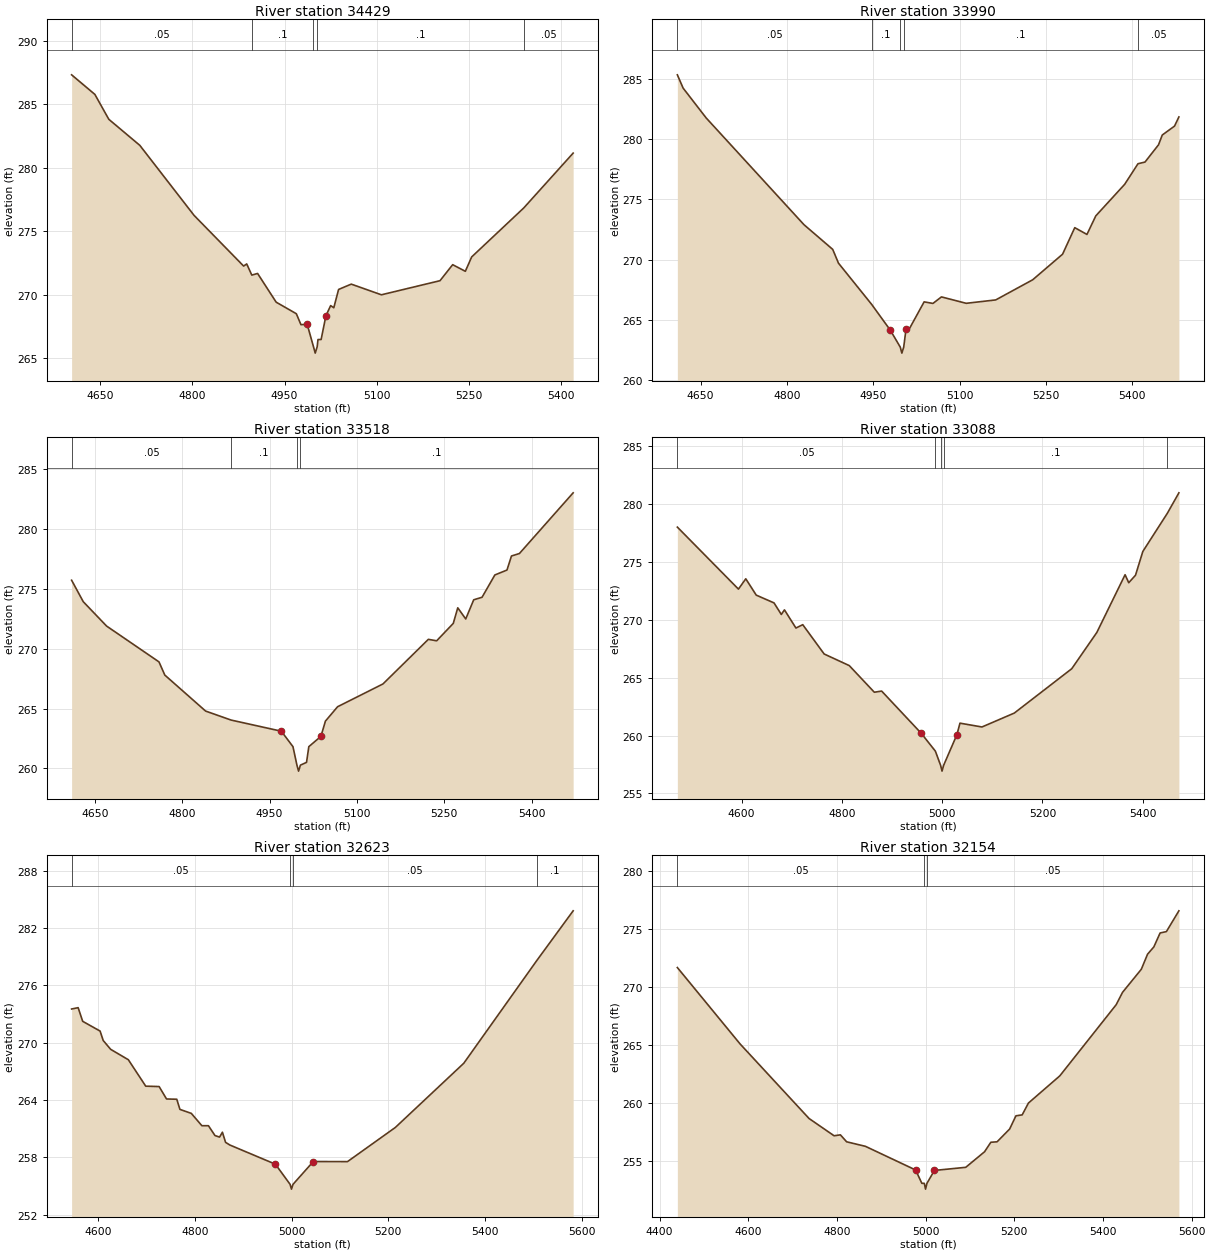
Type RM Length L Ch R = 1 ,34429   ,439,439,439
BEGIN DESCRIPTION:
UNT023 IN SPCR 60.0
END DESCRIPTION:
XS GIS Cut Line= 3
      2243237.68     13263046.85      2243637.72     13263096.85
      2244037.76     13262996.85
#Sta/Elev= 30
  4603.7  287.31  4641.5  285.77  4664.2  283.81  4714.6  281.76  4802.8  276.25
  4883.4  272.26  4888.4  272.43  4896.7  271.55  4906.1  271.68  4936.3  269.42
  4969.1  268.51  4976.6  267.65  4986.7  267.68    4997  265.91  4999.8  265.41
    5003  265.91  5004.3  266.48  5009.4  266.48  5017.2  268.35  5024.9  269.15
    5030  268.98  5037.8  270.42  5058.4  270.84  5107.4     270  5202.7  271.11
  5223.3  272.37  5243.9  271.85  5254.2  272.98  5338.8  276.83  5419.2  281.15
#Mann= 5 ,-1 , 0
  4603.7     .05       0  4896.7      .1       0    4997     .07       0
    5003      .1       0  5338.8     .05       0
Bank Sta=4986.7,5017.2
XS Rating Curve= 0 ,0
Exp/Cntr=0.3,0.1

Type RM Length L Ch R = 1 ,33990   ,472,472,472
BEGIN DESCRIPTION:
UNT023 IN SPCR 59.0
END DESCRIPTION:
XS GIS Cut Line= 3
      2243287.69     13263496.85      2243687.72     13263496.85
       2244087.7     13263246.87
#Sta/Elev= 30
  4609.6  285.33  4619.6  284.23  4659.6  281.76  4829.6  272.91  4879.6  270.86
  4889.6  269.72  4947.3   266.3  4979.6  264.17    4997  262.76  4999.8  262.26
    5003  262.76  5007.1  264.26  5012.6  264.26  5038.5  266.51  5053.8  266.38
  5068.6  266.92  5111.6  266.39  5162.9  266.67  5227.2  268.34  5279.1  270.46
  5300.3  272.66  5321.5   272.1  5336.9  273.64    5387  276.25  5410.2  277.96
  5422.4   278.1  5445.9  279.53  5452.4  280.34  5473.7  281.08  5481.3  281.84
#Mann= 5 ,-1 , 0
  4609.6     .05       0  4947.3      .1       0    4997     .07       0
    5003      .1       0  5410.2     .05       0
Bank Sta=4979.6,5007.1
XS Rating Curve= 0 ,0
Exp/Cntr=0.3,0.1

Type RM Length L Ch R = 1 ,33518   ,430,430,430
BEGIN DESCRIPTION:
UNT023 IN SPCR 58.0
END DESCRIPTION:
XS GIS Cut Line= 3
      2243487.68     13263896.85      2243887.72     13263896.85
      2244237.71     13263596.86
#Sta/Elev= 30
  4610.2   275.7  4630.2  273.91  4670.2  271.88  4760.2  268.89  4770.2  267.79
  4840.2  264.79  4883.9  264.04  4970.2  263.11  4990.2  261.82    4997  260.28
  4999.8  259.78    5003  260.28  5013.5  260.51  5017.4  261.82  5038.2  262.68
  5045.9  263.95  5066.8  265.15  5144.7  267.05  5222.6  270.77  5236.9  270.65
  5265.4   272.1  5273.1   273.4  5286.8  272.47  5300.5  274.07  5314.8  274.28
  5336.8  276.14  5357.6  276.55  5365.3  277.72    5379  277.93  5471.2  282.99
#Mann= 4 ,-1 , 0
  4610.2     .05       0  4883.9      .1       0    4997     .07       0
    5003      .1       0
Bank Sta=4970.2,5038.2
XS Rating Curve= 0 ,0
Exp/Cntr=0.3,0.1

Type RM Length L Ch R = 1 ,33088   ,465,465,465
BEGIN DESCRIPTION:
UNT023 IN SPCR 57.0
END DESCRIPTION:
XS GIS Cut Line= 3
      2243637.74     13264696.83      2243937.72     13264296.85
      2244337.74     13263996.84
#Sta/Elev= 30
  4472.1  277.99  4593.9  272.64  4608.5  273.53  4629.4  272.12  4664.8  271.45
  4679.4  270.45  4685.6  270.85  4708.5  269.28  4722.1  269.57  4764.8  267.04
  4814.8  266.04  4864.8  263.74  4879.4  263.84  4958.5  260.19  4986.6  258.65
    4997  257.43  4999.8  256.93    5003  257.43  5029.4  260.07  5035.6  261.07
  5079.4  260.74  5143.9  261.94  5258.5  265.77  5308.5   268.9  5364.8  273.88
  5372.1  273.19  5385.6  273.84  5400.2  275.89    5449  279.18  5472.1  280.95
#Mann= 5 ,-1 , 0
  4472.1     .05       0  4986.6      .1       0    4997     .07       0
    5003      .1       0    5449     .05       0
Bank Sta=4958.5,5029.4
XS Rating Curve= 0 ,0
Exp/Cntr=0.3,0.1

Type RM Length L Ch R = 1 ,32623   ,469,469,469
BEGIN DESCRIPTION:
UNT023 IN SPCR 56.0
END DESCRIPTION:
XS GIS Cut Line= 3
      2243837.76     13264896.83      2244237.72     13264646.85
      2244637.69     13264246.88
#Sta/Elev= 30
  4545.1  273.52  4558.6  273.66    4568  272.23    4604  271.21  4610.5  270.22
  4625.8   269.3  4662.4  268.21  4698.4  265.44  4726.1   265.4  4741.4   264.1
  4762.6  264.07  4769.1  263.01  4792.7  262.59  4814.5   261.3  4828.1   261.3
  4841.6  260.27  4851.1  260.11    4857  260.62  4863.5  259.56  4872.3  259.28
  4966.6  257.27    4997  255.16  4999.8  254.66    5003  255.16    5045  257.55
  5115.7  257.54  5214.7  261.12  5356.2  267.84    5507  278.58  5582.4   283.8
#Mann= 4 ,-1 , 0
  4545.1     .05       0    4997     .03       0    5003     .05       0
    5507      .1       0
Bank Sta=4966.6,5045
XS Rating Curve= 0 ,0
Exp/Cntr=0.3,0.1

Type RM Length L Ch R = 1 ,32154   ,309,309,309
BEGIN DESCRIPTION:
UNT023 IN SPCR 55.0
END DESCRIPTION:
XS GIS Cut Line= 3
      2244137.74     13265396.84      2244537.72     13264996.85
      2244937.69     13264596.89
#Sta/Elev= 30
    4440  271.71  4581.4  265.13    4737   258.7  4793.5  257.21  4807.7  257.29
  4821.8  256.69  4864.2   256.3  4977.4  254.26  4991.5  253.11    4997  253.11
  4999.8  252.61    5003  253.11  5019.8  254.22  5090.5  254.49  5132.9  255.83
  5147.1  256.65  5161.2  256.69  5189.5  257.79  5203.7  258.93  5217.8  259.01
  5231.9  260.03  5302.6  262.37  5429.9  268.51  5444.1  269.57  5486.5  271.56
  5500.6  272.86  5514.8  273.49  5528.9  274.69  5543.1  274.81  5571.3   276.6
#Mann= 3 ,-1 , 0
    4440     .05       0    4997     .03       0    5003     .05       0
Bank Sta=4977.4,5019.8
XS Rating Curve= 0 ,0
Exp/Cntr=0.3,0.1

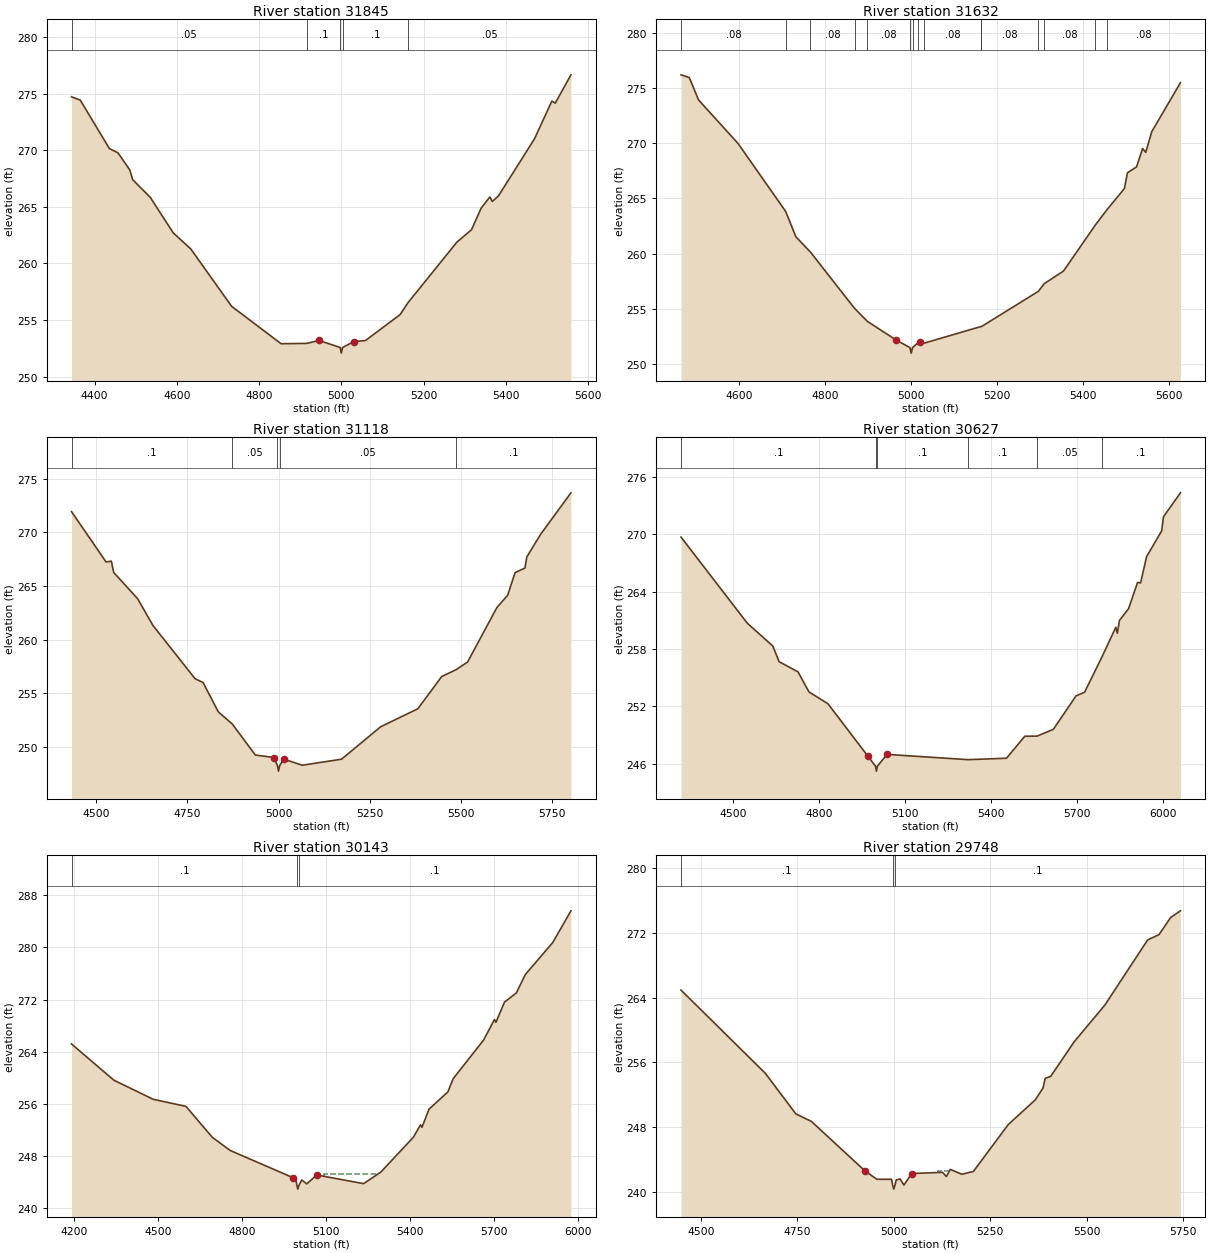
Type RM Length L Ch R = 1 ,31845   ,213,213,213
BEGIN DESCRIPTION:
UNT023 IN SPCR 54.0
END DESCRIPTION:
XS GIS Cut Line= 3
      2244329.03     13265668.17      2244871.58     13265082.21
      2245099.46     13264734.97
#Sta/Elev= 30
  4344.1  274.71  4365.3  274.42  4436.2  270.14  4457.1  269.76  4485.5  268.27
  4492.9  267.39  4535.4  265.84  4591.5  262.69    4634  261.28  4733.3  256.21
  4853.5  252.91  4916.4  252.94  4945.5   253.2    4997  252.58  4999.8  252.08
    5003  252.58  5030.4   253.1  5058.7  253.19  5142.7  255.48  5162.1  256.54
  5280.6  261.87  5316.5  262.98  5339.9  264.89  5360.9  265.87  5366.9  265.47
    5382  265.97  5469.4     271  5511.6  274.33  5519.9  274.15    5558  276.65
#Mann= 5 ,-1 , 0
  4344.1     .05       0  4916.4      .1       0    4997     .07       0
    5003      .1       0  5162.1     .05       0
Bank Sta=4945.5,5030.4
XS Rating Curve= 0 ,0
Exp/Cntr=0.3,0.1

Type RM Length L Ch R = 1 ,31632   ,514,514,514
BEGIN DESCRIPTION:
Mapping XS 935c4a0f
END DESCRIPTION:
XS GIS Cut Line= 2
      2244413.71     13265740.32        2245214.      13264898.8
#Sta/Elev= 30
  4464.6  276.18  4483.9  275.93  4505.3  273.91  4597.1  269.97    4708  263.81
  4731.6  261.52  4765.6  260.13    4868  255.04  4898.1  253.85  4965.2  252.16
    4997  251.48  4999.8  250.98    5003  251.48    5015   251.9  5021.4     252
  5030.6  251.89  5162.1  253.39  5163.1  253.38  5295.7  256.58  5309.2  257.27
  5353.9  258.41  5428.2  262.59  5456.2  264.02  5495.5  265.88  5502.7  267.31
  5523.8  267.84  5537.9  269.51  5545.2  269.16  5559.3  271.04  5625.9  275.47
#Mann= 15 ,-1 , 0
  4464.6     .08       0    4708      .1       0  4765.6     .08       0
    4868     .05       0  4898.1     .08       0    4997     .07       0
    5003     .08       0    5015     .05       0  5030.6     .08       0
  5162.1     .05       0  5163.1     .08       0  5295.7      .1       0
  5309.2     .08       0  5428.2      .1       0  5456.2     .08       0
Bank Sta=4965.2,5021.4
XS Rating Curve= 0 ,0
Exp/Cntr=0.3,0.1

Type RM Length L Ch R = 1 ,31118   ,491,491,491
BEGIN DESCRIPTION:
UNT023 IN SPCR 53.0
END DESCRIPTION:
XS GIS Cut Line= 3
      2244847.23     13266067.12      2245452.72     13265179.51
      2245435.52     13264883.67
#Sta/Elev= 30
  4431.7  271.94  4526.5  267.25    4541  267.32  4547.5  266.27  4613.2  263.82
  4655.2  261.33    4771  256.36  4792.7  256.01  4834.7  253.27  4872.8  252.15
  4936.3  249.25  4987.2  249.02    4997  248.25  4999.8  247.75    5003  248.25
  5014.2  248.87    5065   248.3  5172.7  248.86  5280.5  251.89  5382.1  253.56
  5447.9  256.57  5487.6  257.21  5518.8  257.92    5599  262.98    5629  264.16
  5649.1  266.25  5676.3  266.68  5681.3  267.71  5719.2  269.82  5802.5  273.69
#Mann= 5 ,-1 , 0
  4431.7      .1       0  4872.8     .05       0    4997     .03       0
    5003     .05       0  5487.6      .1       0
Bank Sta=4987.2,5014.2
XS Rating Curve= 0 ,0
Exp/Cntr=0.3,0.1

Type RM Length L Ch R = 1 ,30627   ,484,484,484
BEGIN DESCRIPTION:
UNT023 IN SPCR 52.0
END DESCRIPTION:
XS GIS Cut Line= 4
      2245063.98     13266194.42      2245521.53     13265950.16
      2245844.93     13265117.59      2245745.17     13264804.54
#Sta/Elev= 30
  4318.9  269.71  4549.9  260.71  4638.9  258.32  4660.8  256.68  4726.7  255.62
  4764.9  253.52  4830.8  252.29  4969.8  246.82    4997  245.74  4999.8  245.24
    5003  245.74  5036.9  246.99  5318.8  246.44  5453.2  246.59    5517  248.89
  5559.8   248.9  5616.5  249.61  5695.5  253.11  5725.4  253.49  5784.8  257.12
    5834  260.28  5839.3  259.67    5847  261.01  5878.5  262.22  5909.9  264.97
  5920.4  264.92  5941.4  267.67  5993.9  270.36  6000.3  271.84  6059.3  274.34
#Mann= 6 ,-1 , 0
  4318.9      .1       0    4997     .07       0    5003      .1       0
  5318.8      .1       0  5559.8     .05       0  5784.8      .1       0
Bank Sta=4969.8,5036.9
XS Rating Curve= 0 ,0
Exp/Cntr=0.3,0.1

Type RM Length L Ch R = 1 ,30143   ,395,395,395
BEGIN DESCRIPTION:
UNT023 IN SPCR 51.0
END DESCRIPTION:
XS GIS Cut Line= 2
      2245215.34     13266190.99      2246890.84     13265578.59
#Sta/Elev= 30
  4191.5   265.2  4343.1  259.63  4483.5  256.71  4600.4  255.62  4694.4  250.88
  4758.3  248.86  4981.9   244.7  4992.6  244.41    4997  243.43  4999.8  242.93
    5003  243.43  5013.9  244.33  5031.8  243.73  5067.6   245.1  5234.9  243.77
    5296  245.53  5412.8   250.9    5438  252.79  5443.3  252.41  5468.5   255.2
  5535.6  257.83  5554.8  259.87  5663.3  265.79  5702.2  268.95  5707.5  268.52
    5738  271.61  5780.4  273.03  5812.4  275.84  5910.6  280.77  5975.4  285.62
#Mann= 3 ,-1 , 0
  4191.5      .1       0    4997     .07       0    5003      .1       0
#XS Ineff= 1 ,-1
 5093.35 5287.56   245.2
Permanent Ineff=
       F
Bank Sta=4981.9,5067.6
XS Rating Curve= 0 ,0
Exp/Cntr=0.3,0.1

Type RM Length L Ch R = 1 ,29748   ,354,354,354
BEGIN DESCRIPTION:
UNT023 IN SPCR 50.0
END DESCRIPTION:
XS GIS Cut Line= 4
      2245517.86     13266471.96      2245747.89     13266315.72
       2246255.7     13266289.67      2246763.15     13266328.71
#Sta/Elev= 30
  4447.9  264.94  4666.5  254.65  4745.8  249.62  4785.9   248.7  4926.1  242.52
  4956.1  241.53  4993.9  241.53    4997  240.81  4999.8  240.31    5003  240.81
  5006.2  241.46  5016.2  241.57  5026.2  240.81  5046.2  242.24  5126.3  242.39
  5136.3  241.87  5146.4  242.75  5176.4  242.15  5206.4   242.5  5296.7   248.3
  5366.9  251.36  5386.9  252.82  5392.6  254.02    5407  254.27  5467.2  258.51
  5547.4  263.09  5658.4  271.15  5687.8   271.8  5717.9  273.92  5743.4  274.75
#Mann= 3 ,-1 , 0
  4447.9      .1       0    4997     .07       0    5003      .1       0
#XS Ineff= 1 ,-1
 5114.22 5151.41   242.6
Permanent Ineff=
       F
Bank Sta=4926.1,5046.2
XS Rating Curve= 0 ,0
Exp/Cntr=0.3,0.1

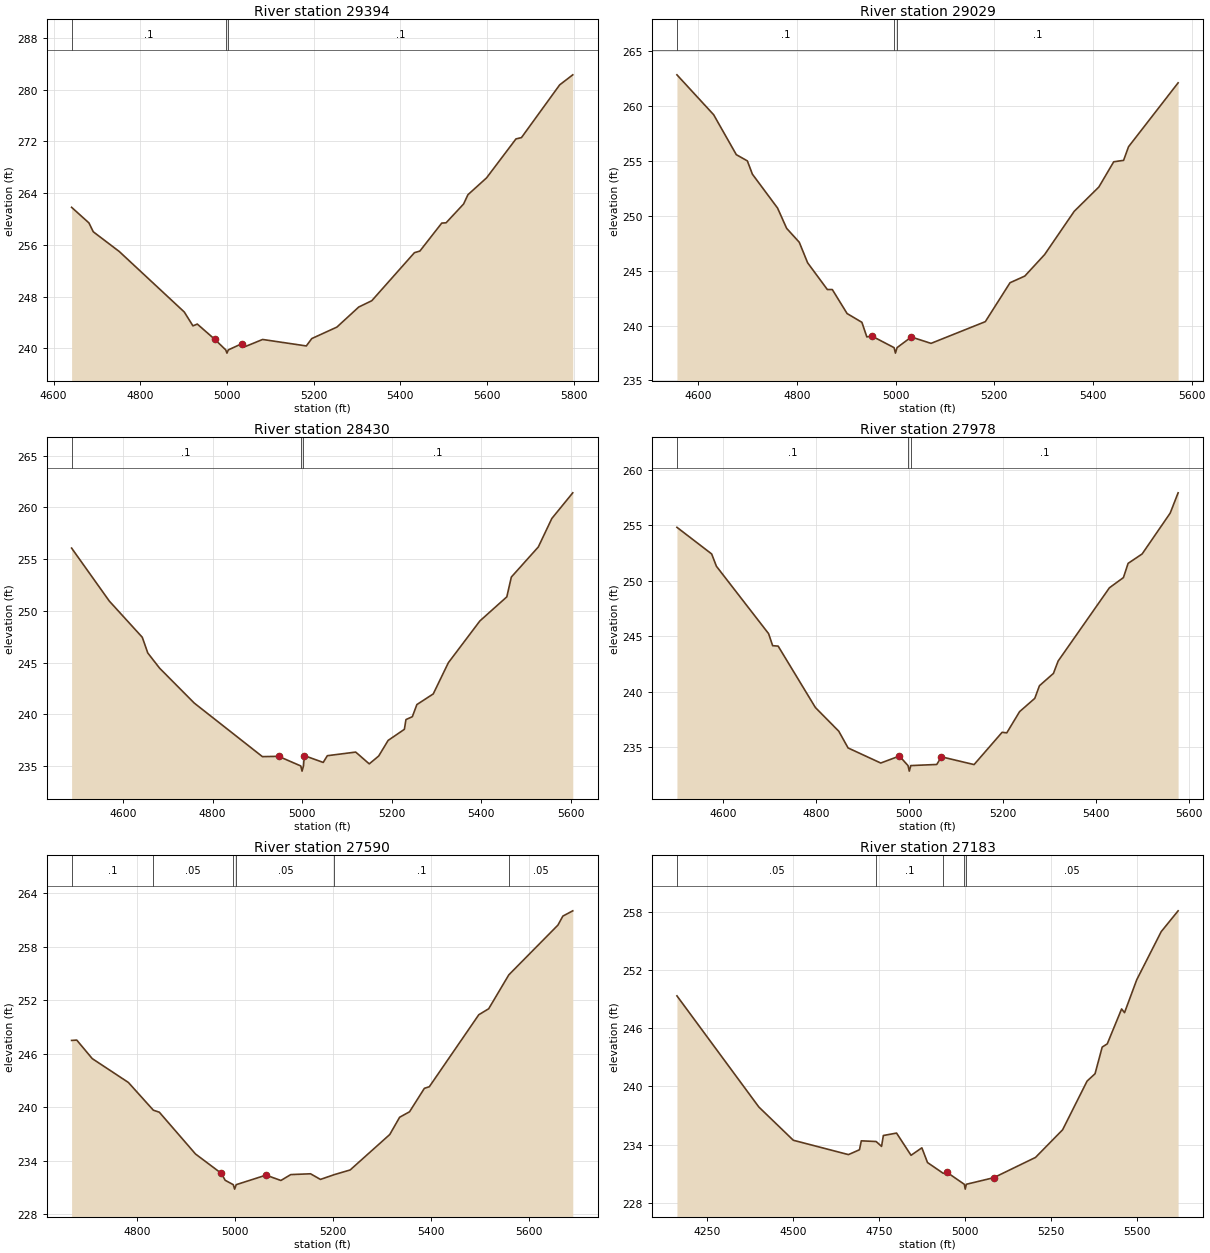
Type RM Length L Ch R = 1 ,29394   ,365,365,365
BEGIN DESCRIPTION:
UNT023 IN SPCR 49.0
END DESCRIPTION:
XS GIS Cut Line= 3
      2245637.73     13266646.85      2245987.72     13266646.85
       2246787.7     13266546.86
#Sta/Elev= 30
  4641.4  261.81  4681.4   259.4  4691.4  258.03  4751.4  254.98  4901.4  245.63
  4921.4  243.49  4931.4  243.77  4971.4  241.43    4997  239.78  4999.8  239.28
    5003  239.78  5034.2  240.74  5041.8  240.29  5082.1  241.39  5182.9  240.39
  5195.5  241.53  5253.4   243.3  5303.8   246.4    5334  247.38  5432.3   254.8
  5444.9  255.05  5495.3  259.37  5505.4  259.42  5545.7  262.32  5555.8  263.76
  5598.6  266.35  5666.6  272.38  5679.2  272.58  5767.4  280.73  5797.6  282.28
#Mann= 3 ,-1 , 0
  4641.4      .1       0    4997     .07       0    5003      .1       0
Bank Sta=4971.4,5034.2
XS Rating Curve= 0 ,0
Exp/Cntr=0.3,0.1

Type RM Length L Ch R = 1 ,29029   ,599,599,599
BEGIN DESCRIPTION:
UNT023 IN SPCR 48.0
END DESCRIPTION:
XS GIS Cut Line= 3
      2245537.79     13266947.66      2245780.87     13266996.27
      2246548.19     13267020.58
#Sta/Elev= 30
    4557  262.87  4631.4  259.23  4677.3  255.59  4699.7  255.02  4709.9  253.81
  4760.9  250.72  4779.3  248.87  4804.9   247.6  4821.8  245.73  4861.8  243.29
  4871.8  243.29  4901.8   241.1  4931.8   240.3  4941.8  238.97  4951.8  239.05
    4997  237.99  4999.8  237.49    5003  237.99  5031.9  238.96  5071.9  238.38
  5181.9  240.36    5232  243.91    5262  244.52  5302.1  246.48    5362  250.42
    5412  252.64  5442.1  254.94  5462.1  255.07  5472.1  256.31  5572.6  262.14
#Mann= 3 ,-1 , 0
    4557      .1       0    4997     .07       0    5003      .1       0
Bank Sta=4951.8,5031.9
XS Rating Curve= 0 ,0
Exp/Cntr=0.3,0.1

Type RM Length L Ch R = 1 ,28430   ,452,452,452
BEGIN DESCRIPTION:
UNT023 IN SPCR 47.0
END DESCRIPTION:
XS GIS Cut Line= 4
      2245510.02     13267096.92      2245621.15      13267430.3
      2245954.48     13267645.58      2246324.32      13267683.6
#Sta/Elev= 30
  4484.8  256.06  4569.1  250.94  4642.8  247.44    4655  245.93  4681.4  244.46
  4758.8  241.09  4911.2  235.91  4947.4  235.94    4997  235.01  4999.8  234.51
    5003  235.01  5004.9  236.01  5047.1  235.35  5056.3     236  5119.7  236.35
    5150  235.21  5171.1  235.97  5192.2  237.48  5228.5  238.55    5232  239.49
  5246.3  239.77  5256.4  240.94    5293  241.97  5326.7  244.98  5397.2  249.02
  5457.4  251.35  5467.5  253.26  5527.8  256.17    5558  258.92  5604.8   261.4
#Mann= 3 ,-1 , 0
  4484.8      .1       0    4997     .07       0    5003      .1       0
Bank Sta=4947.4,5004.9
XS Rating Curve= 0 ,0
Exp/Cntr=0.3,0.1

Type RM Length L Ch R = 1 ,27978   ,388,388,388
BEGIN DESCRIPTION:
UNT023 IN SPCR 46.0
END DESCRIPTION:
XS GIS Cut Line= 4
      2245124.58     13267883.42      2245332.95     13267922.49
      2246062.12     13267935.51      2246194.65     13267944.06
#Sta/Elev= 30
  4501.8  254.81  4576.2  252.41  4586.4   251.3  4698.3  245.22  4706.9  244.14
  4718.7   244.1  4798.6  238.56  4848.6  236.43  4868.6  234.92  4938.6  233.56
  4978.6  234.19    4997  233.33  4999.8  232.83    5003  233.33  5058.6  233.43
  5068.6  234.12  5138.6  233.42  5198.7  236.33  5208.7  236.28  5236.1  238.19
  5268.7  239.39  5278.7  240.53  5308.7  241.64  5318.7  242.75  5428.7  249.36
  5458.7  250.28  5468.7  251.56  5498.8  252.41  5558.9  256.09  5575.9  257.92
#Mann= 3 ,-1 , 0
  4501.8      .1       0    4997     .07       0    5003      .1       0
Bank Sta=4978.6,5068.6
XS Rating Curve= 0 ,0
Exp/Cntr=0.3,0.1

Type RM Length L Ch R = 1 ,27590   ,407,407,407
BEGIN DESCRIPTION:
UNT023 IN SPCR 45.0
END DESCRIPTION:
XS GIS Cut Line= 3
      2245237.73     13268196.86      2245537.72     13268296.85
       2246237.7     13268196.86
#Sta/Elev= 30
  4666.9  247.49  4677.4  247.53  4709.1  245.45  4782.8  242.78  4833.8  239.67
  4846.1  239.44  4919.9  234.76  4972.6  232.59  4980.5  231.81    4997  231.32
  4999.8  230.82    5003  231.32  5063.9  232.39  5094.2  231.79  5114.4  232.45
  5154.8  232.54    5175  231.91  5203.6  232.45  5235.7  232.97  5316.5  236.94
  5336.7  238.88  5356.9  239.49  5387.2  242.12  5397.3   242.3  5498.3  250.37
  5518.5  251.04  5559.6  254.84  5659.9  260.42    5670  261.43  5690.2  262.02
#Mann= 6 ,-1 , 0
  4666.9      .1       0  4833.8     .05       0    4997     .03       0
    5003     .05       0  5203.6      .1       0  5559.6     .05       0
Bank Sta=4972.6,5063.9
XS Rating Curve= 0 ,0
Exp/Cntr=0.3,0.1

Type RM Length L Ch R = 1 ,27183   ,563,563,563
BEGIN DESCRIPTION:
UNT023 IN SPCR 44.0
END DESCRIPTION:
XS GIS Cut Line= 4
      2244890.22     13268803.57      2245319.93     13268773.18
      2245806.04     13268616.93      2246222.74     13268313.09
#Sta/Elev= 30
  4161.6  249.34  4399.7  237.88  4499.9  234.45  4660.2  232.97  4692.3  233.47
  4697.6  234.39  4740.7  234.32  4756.5  233.82  4761.7  234.94  4800.1  235.19
  4842.2   232.9  4873.7  233.67  4890.1  232.15  4935.8  231.04  4947.2  231.13
    4997  229.91  4999.8  229.41    5003  229.91  5082.7  230.59  5204.1  232.68
  5282.9  235.53    5354  240.55  5377.2  241.31    5398  244.06  5412.7  244.39
  5454.4  247.99  5462.9  247.61  5498.5  251.01  5569.5  255.96  5618.7  258.11
#Mann= 5 ,-1 , 0
  4161.6     .05       0  4740.7      .1       0  4935.8     .05       0
    4997     .03       0    5003     .05       0
Bank Sta=4947.2,5082.7
XS Rating Curve= 0 ,0
Exp/Cntr=0.3,0.1