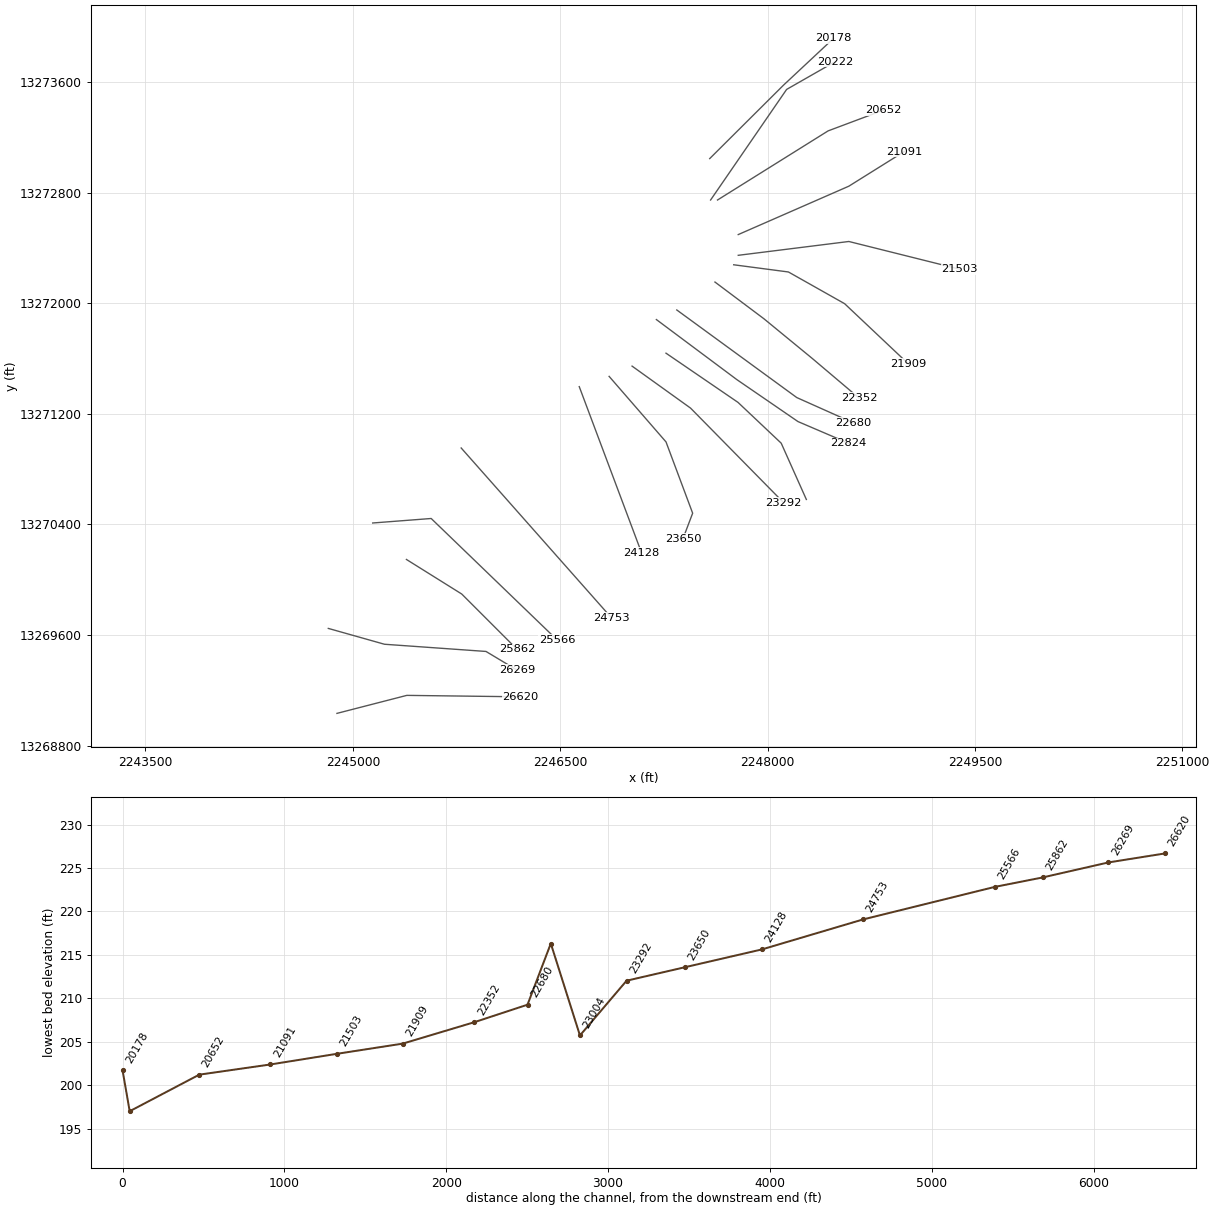
HEC-RAS study UNT023 IN SPCR.prj: UNT023 IN SPCR Base Level Engineering

--- UNT023 IN SPCR.g01 (geometry) --- (continued)

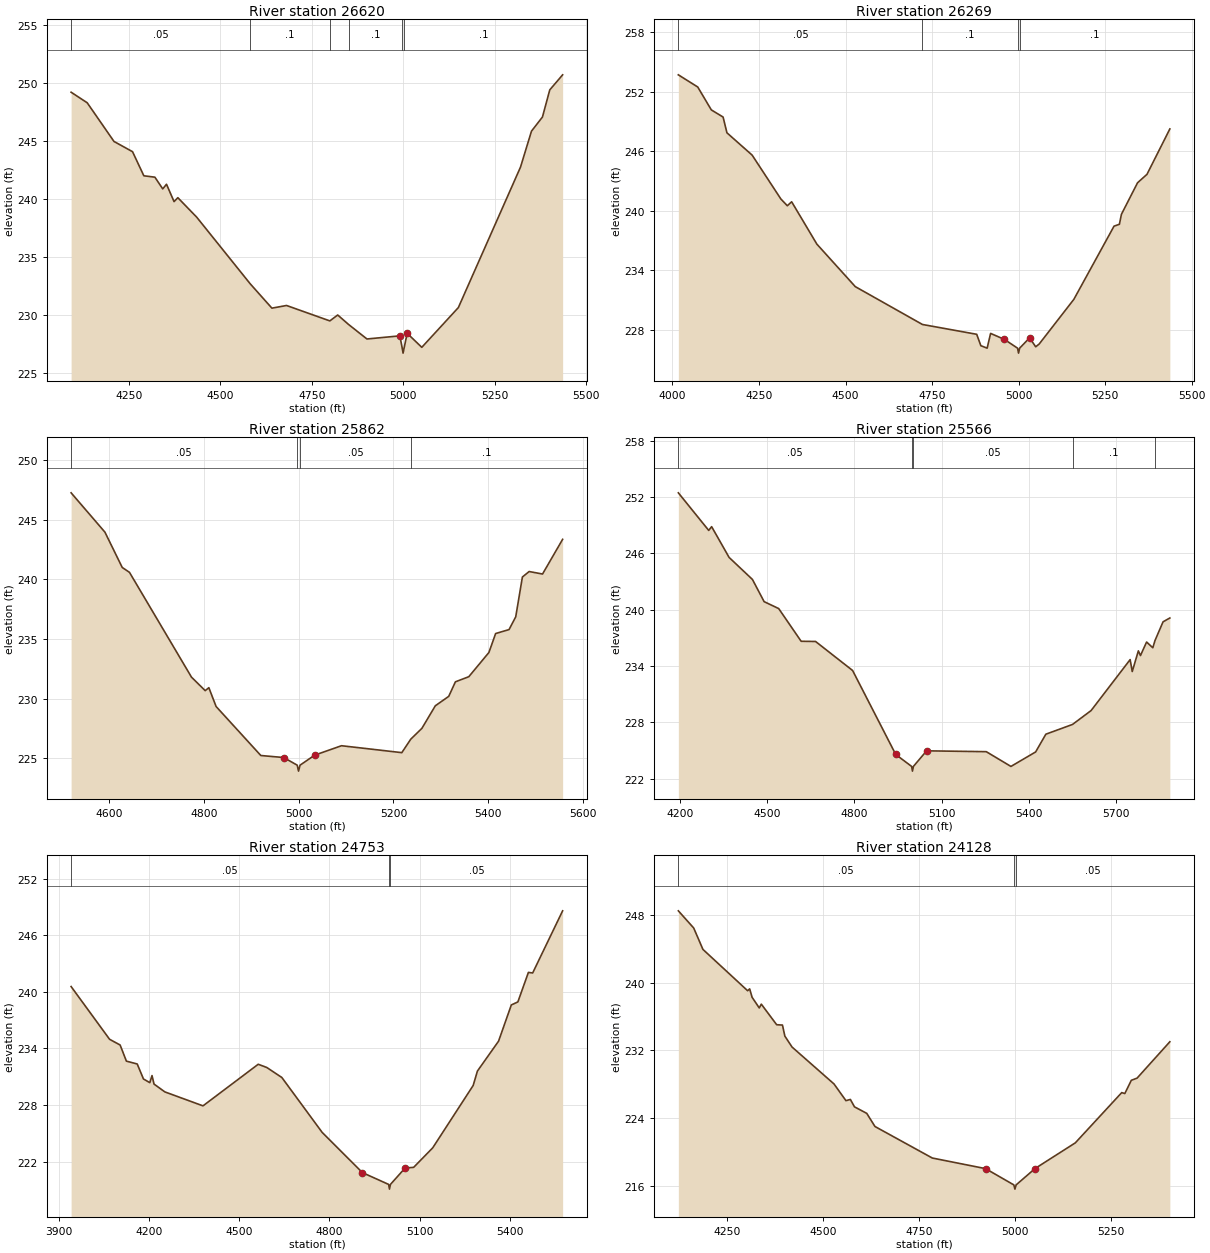
Type RM Length L Ch R = 1 ,26620   ,351,351,351
BEGIN DESCRIPTION:
UNT023 IN SPCR 43.0
END DESCRIPTION:
XS GIS Cut Line= 3
      2244885.08     13269033.61      2245390.25     13269163.81
       2246212.9     13269153.39
#Sta/Elev= 30
  4091.8  249.19  4135.8  248.28  4209.1  244.94  4259.8  244.06  4290.7  241.98
  4320.9  241.86  4342.4  240.85  4352.7  241.25  4373.4  239.75  4383.7  240.09
  4435.3  238.41  4581.7  232.66    4641  230.56    4681  230.79  4799.5  229.46
    4821  229.97  4850.8  229.15    4901   227.9    4991  228.17    4997  227.18
  4999.8  226.68    5003  227.18    5011  228.39    5051  227.18    5151  230.61
    5321  242.73    5351  245.83    5381  247.05    5401  249.39  5436.2  250.69
#Mann= 6 ,-1 , 0
  4091.8     .05       0  4581.7      .1       0  4799.5     .05       0
  4850.8      .1       0    4997     .07       0    5003      .1       0
Bank Sta=4991,5011
XS Rating Curve= 0 ,0
Exp/Cntr=0.3,0.1

Type RM Length L Ch R = 1 ,26269   ,407,407,407
BEGIN DESCRIPTION:
UNT023 IN SPCR 42.0
END DESCRIPTION:
XS GIS Cut Line= 4
      2244822.57     13269648.17      2245228.79      13269533.6
      2245963.16     13269481.52       2246187.7     13269346.87
#Sta/Elev= 30
  4016.9  253.72    4073  252.49  4112.2  250.18  4146.2  249.46  4157.3  247.87
  4230.1  245.62  4313.2  241.19  4331.8  240.51  4344.3  240.91  4417.1  236.64
  4528.1  232.35  4722.2  228.53    4879  227.54  4890.9  226.39  4909.1  226.14
  4919.1  227.63  4959.2  227.02    4997  226.14  4999.8  225.64    5003  226.14
  5031.7  227.18  5049.4  226.28  5059.5  226.56  5159.7  231.07  5275.7  238.45
  5291.2  238.64  5297.1  239.65  5343.7  242.83  5370.9  243.68    5437  248.26
#Mann= 4 ,-1 , 0
  4016.9     .05       0  4722.2      .1       0    4997     .07       0
    5003      .1       0
Bank Sta=4959.2,5031.7
XS Rating Curve= 0 ,0
Exp/Cntr=0.3,0.1

Type RM Length L Ch R = 1 ,25862   ,296,296,296
BEGIN DESCRIPTION:
UNT023 IN SPCR 41.0
END DESCRIPTION:
XS GIS Cut Line= 3
      2245387.71     13270146.86      2245787.72     13269896.85
      2246187.72     13269496.85
#Sta/Elev= 30
  4519.8  247.25  4591.2  243.95  4627.7  240.99    4643  240.58  4773.9  231.79
  4802.8  230.66  4810.5  230.91  4825.8  229.33  4920.2  225.22  4968.5  225.05
    4997  224.41  4999.8  223.91    5003  224.41  5033.9  225.25  5090.5  226.04
  5217.8  225.46  5236.7  226.59  5260.2   227.5  5288.5  229.39  5316.8  230.18
  5330.9   231.4  5359.2  231.83  5401.6  233.86  5415.8  235.45  5444.1  235.78
  5458.2  236.85  5472.3  240.19  5486.5  240.65  5514.8  240.44  5557.2  243.35
#Mann= 4 ,-1 , 0
  4519.8     .05       0    4997     .03       0    5003     .05       0
  5236.7      .1       0
Bank Sta=4968.5,5033.9
XS Rating Curve= 0 ,0
Exp/Cntr=0.3,0.1

Type RM Length L Ch R = 1 ,25566   ,813,813,813
BEGIN DESCRIPTION:
UNT023 IN SPCR 40.0
END DESCRIPTION:
XS GIS Cut Line= 3
      2245143.55     13270410.69      2245566.68     13270443.23
      2246478.16      13269564.3
#Sta/Elev= 30
  4194.5  252.44    4299  248.44    4309  248.84  4369.2  245.56  4449.4  243.22
  4489.5  240.86  4539.7  240.12  4616.9  236.64  4666.5  236.62  4793.9  233.53
  4942.3  224.59    4997  223.32  4999.8  222.82    5003  223.32  5048.5  224.98
  5253.6  224.89  5338.5  223.32  5423.4  224.86  5458.6  226.75  5550.4  227.79
  5614.3  229.27  5748.5  234.69  5755.7  233.42  5776.8  235.62    5784  235.12
  5805.1  236.56  5826.5  235.95    5834  236.72  5861.7  238.71  5885.1  239.12
#Mann= 5 ,-1 , 0
  4194.5     .05       0    4997     .03       0    5003     .05       0
  5550.4      .1       0    5834     .08       0
Bank Sta=4942.3,5048.5
XS Rating Curve= 0 ,0
Exp/Cntr=0.3,0.1

Type RM Length L Ch R = 1 ,24753   ,625,625,625
BEGIN DESCRIPTION:
UNT023 IN SPCR 38.0
END DESCRIPTION:
XS GIS Cut Line= 2
      2245783.71      13270953.2      2246868.77     13269727.07
#Sta/Elev= 30
  3939.3  240.56  4067.4  234.97  4102.6  234.36  4123.5  232.65  4159.5  232.35
  4180.3  230.76  4201.5  230.37  4208.8  231.12  4215.5  230.22  4251.5  229.39
  4378.6  227.91  4562.6  232.32    4591  231.98  4641.2  230.92  4775.7  225.09
  4909.7  220.83    4997  219.58  4999.8  219.08    5003  219.58  5051.9  221.32
  5080.4  221.39  5143.9  223.46  5278.6  230.07  5292.8   231.6  5363.2  234.77
  5405.7  238.61  5427.5  238.93  5462.6  242.06  5476.8     242  5576.6  248.59
#Mann= 3 ,-1 , 0
  3939.3     .05       0    4997     .03       0    5003     .05       0
Bank Sta=4909.7,5051.9
XS Rating Curve= 0 ,0
Exp/Cntr=0.3,0.1

Type RM Length L Ch R = 1 ,24128   ,478,478,478
BEGIN DESCRIPTION:
UNT023 IN SPCR 37.0
END DESCRIPTION:
XS GIS Cut Line= 3
      2246637.71     13271396.89      2246937.72     13270596.85
      2247087.71     13270196.89
#Sta/Elev= 30
  4122.2  248.47  4162.3  246.44  4186.3  243.92  4302.9  239.04  4308.2  239.26
  4314.5  238.27  4333.2  237.01  4338.5  237.46  4378.6  235.03  4393.7  234.99
  4399.9  233.69  4418.6   232.4  4528.1  228.04  4559.2  226.07  4570.8  226.21
  4581.5  225.34  4613.5  224.57  4634.9  223.02  4784.4   219.3  4923.2  218.05
    4997  216.13  4999.8  215.63    5003  216.13  5052.3  218.06  5157.3  221.09
  5278.3  227.02  5286.4  226.91  5303.3  228.47  5318.4  228.73  5403.8  233.02
#Mann= 3 ,-1 , 0
  4122.2     .05       0    4997     .03       0    5003     .05       0
Bank Sta=4923.2,5052.3
XS Rating Curve= 0 ,0
Exp/Cntr=0.3,0.1

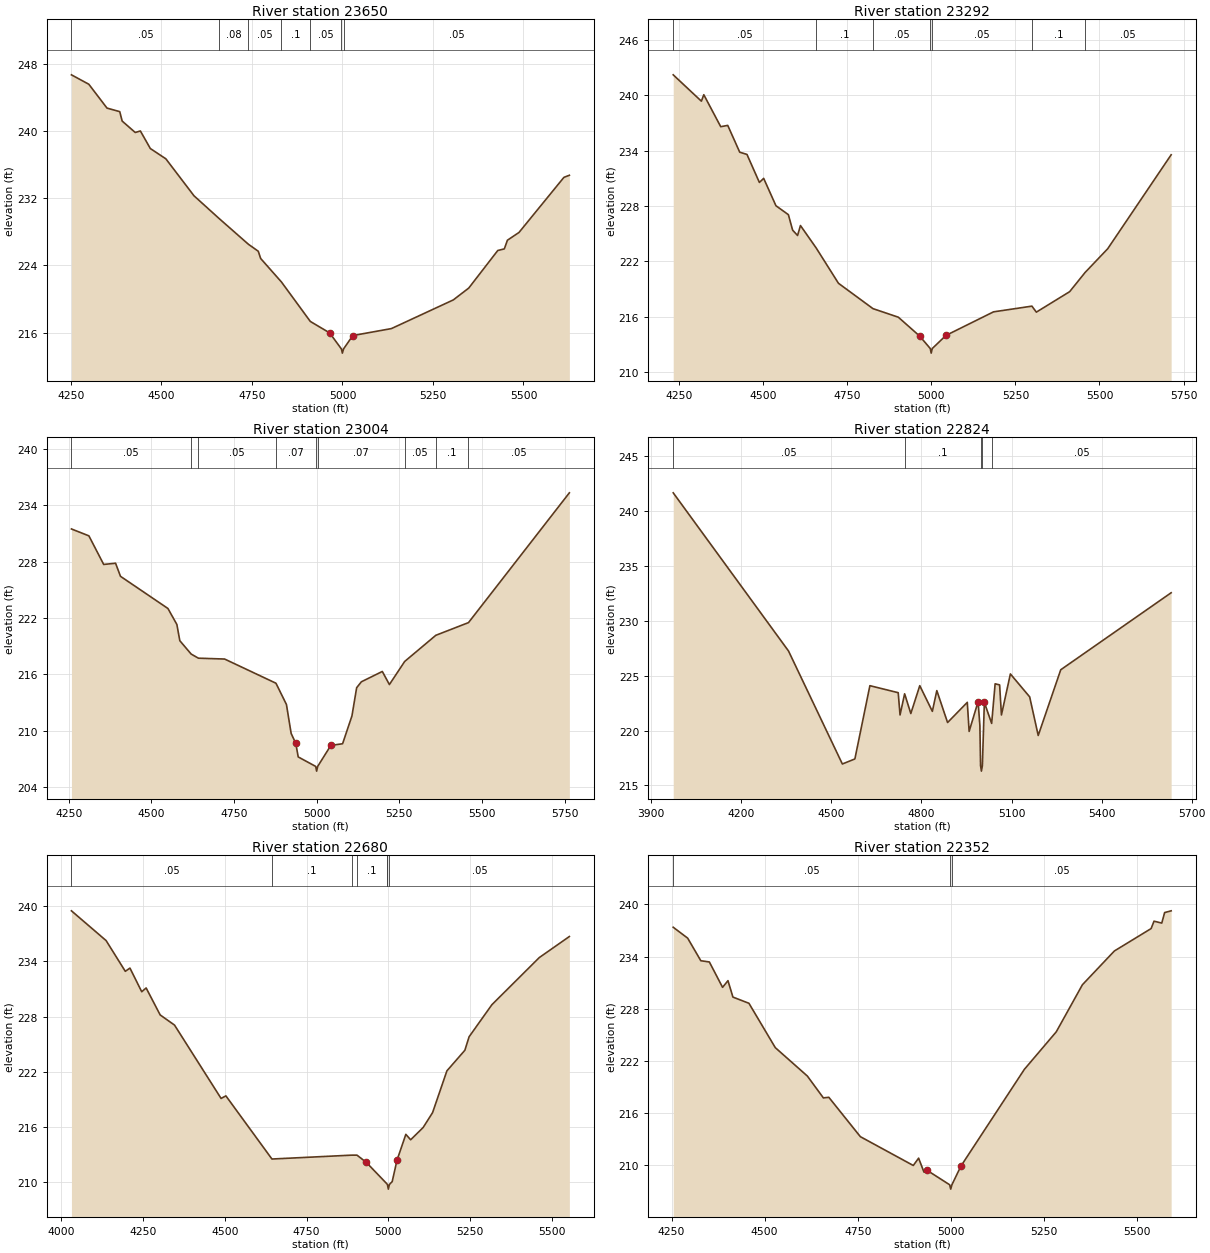
Type RM Length L Ch R = 1 ,23650   ,358,358,358
BEGIN DESCRIPTION:
UNT023 IN SPCR 36.0
END DESCRIPTION:
XS GIS Cut Line= 4
       2246853.8     13271471.09      2247265.25     13270997.14
      2247457.95     13270481.52       2247387.7     13270296.81
#Sta/Elev= 30
  4251.2  246.68  4299.2  245.56  4349.5  242.72  4384.7   242.3  4391.3  241.18
  4427.5  239.82  4441.7     240  4469.2  237.91    4512  236.69  4589.8  232.29
  4660.1  229.55  4740.2  226.52  4767.4  225.69    4774  224.83  4831.5  222.03
  4911.2  217.34  4964.5  215.98    4997  214.07  4999.8  213.57    5003  214.07
  5028.6  215.66  5135.3  216.49  5306.2   219.9  5348.9  221.31  5429.1  225.78
  5447.2  225.97  5455.7     227  5487.8  227.93  5611.8  234.48  5626.9  234.73
#Mann= 7 ,-1 , 0
  4251.2     .05       0  4660.1     .08       0  4740.2     .05       0
  4831.5      .1       0  4911.2     .05       0    4997     .03       0
    5003     .05       0
Bank Sta=4964.5,5028.6
XS Rating Curve= 0 ,0
Exp/Cntr=0.3,0.1

Type RM Length L Ch R = 1 ,23292   ,288,288,288
BEGIN DESCRIPTION:
UNT023 IN SPCR 35.0
END DESCRIPTION:
XS GIS Cut Line= 3
      2247019.69     13271545.42      2247442.85     13271241.62
      2248115.57     13270558.04
#Sta/Elev= 30
    4233  242.24  4316.7  239.38  4323.9  240.08  4374.2  236.61  4395.1  236.75
  4430.7  233.84  4452.2   233.6  4489.1  230.56  4501.9     231  4538.3  228.03
  4575.3  227.06  4587.9  225.38  4602.6   224.8  4611.2  225.88    4658  223.44
  4724.2  219.61  4826.7  216.86  4902.1  215.93  4965.8  213.87    4997  212.53
  4999.8  212.03    5003  212.53  5043.6  213.95    5185  216.51  5299.1  217.13
  5312.3  216.48  5411.3   218.7  5457.1  220.78  5524.4  223.36    5713  233.56
#Mann= 7 ,-1 , 0
    4233     .05       0    4658      .1       0  4826.7     .05       0
    4997     .03       0    5003     .05       0  5299.1      .1       0
  5457.1     .05       0
Bank Sta=4965.8,5043.6
XS Rating Curve= 0 ,0
Exp/Cntr=0.3,0.1

Type RM Length L Ch R = 1 ,23004   ,180,180,180
BEGIN DESCRIPTION:
Mapping XS 3450125e
END DESCRIPTION:
XS GIS Cut Line= 4
      2247265.13     13271638.96      2247785.97     13271283.06
      2248098.47     13270987.92      2248280.34     13270580.87
#Sta/Elev= 30
    4258  231.46  4310.8  230.73  4355.6  227.69  4391.5  227.82  4406.4  226.43
    4550  223.01    4577  221.31  4585.9  219.59  4620.2  218.17  4642.1  217.73
  4721.4  217.64  4876.8  215.07  4908.5  212.81  4922.7  209.74  4936.8  208.67
  4944.1  207.24    4997  206.23  4999.8  205.73    5003  206.23  5042.8  208.46
  5078.4  208.64  5106.7   211.6  5120.9  214.59  5135.1  215.22  5198.6  216.32
    5220  214.93  5266.2  217.38  5360.4  220.16  5459.3  221.51  5764.5   235.3
#Mann= 9 ,-1 , 0
    4258     .05       0  4620.2      .1       0  4642.1     .05       0
  4876.8     .07       0    4997     .07       0    5003     .07       0
  5266.2     .05       0  5360.4      .1       0  5459.3     .05       0
Bank Sta=4936.8,5042.8
XS Rating Curve= 0 ,0
Exp/Cntr=0.3,0.1

Type RM Length L Ch R = 1 ,22824   ,144,144,144
BEGIN DESCRIPTION:
UNT023 IN SPCR 34.0
END DESCRIPTION:
XS GIS Cut Line= 4
      2247195.68     13271882.02      2247777.29     13271447.99
        2248220.     13271144.17      2248583.67     13270988.31
#Sta/Elev= 30
  3973.4  241.68  4357.4  227.26  4536.7  216.96  4578.4  217.42  4628.4   224.1
  4722.7  223.46  4728.8  221.43  4744.1  223.36  4764.7  221.56  4794.5   224.1
  4836.4  221.76  4851.3  223.65  4887.1  220.74  4952.8  222.58  4958.9  219.93
  4988.7  222.64  4994.7  220.47    4997  216.81  4999.8  216.31    5003  216.81
  5009.6  222.57  5033.9  220.66  5045.5  224.27  5060.4  224.17  5066.5  221.43
  5096.3  225.17  5160.5  223.08    5189  219.56    5264  225.55  5631.7  232.57
#Mann= 5 ,-1 , 0
  3973.4     .05       0  4744.1      .1       0    4997     .07       0
    5003      .1       0  5033.9     .05       0
Bank Sta=4988.7,5009.6
XS Rating Curve= 0 ,0
Exp/Cntr=0.3,0.1

Type RM Length L Ch R = 1 ,22680   ,328,328,328
BEGIN DESCRIPTION:
Mapping XS a7fecc01
END DESCRIPTION:
XS GIS Cut Line= 3
      2247343.29     13271951.44      2248211.32     13271317.78
      2248619.33     13271135.48
#Sta/Elev= 30
  4031.4   239.5  4137.3  236.27    4196  232.93  4210.2  233.28  4246.2  230.71
  4259.7  231.12  4302.6  228.19  4346.4  227.09  4488.7  219.12  4503.4   219.4
  4644.1  212.54  4887.3  212.96    4904  212.96  4932.1  212.19  4994.2  209.89
    4997  209.77  4999.8  209.27    5003  209.77  5011.6  210.09  5026.3  212.41
  5053.3  215.22    5068  214.63  5106.1  215.96    5135  217.58  5178.8  222.12
  5233.6  224.35  5246.6  225.82  5316.2   229.3    5461  234.42    5553  236.71
#Mann= 7 ,-1 , 0
  4031.4     .05       0  4644.1      .1       0  4887.3     .05       0
    4904      .1       0  4994.2     .05       0    4997     .03       0
    5003     .05       0
Bank Sta=4932.1,5026.3
XS Rating Curve= 0 ,0
Exp/Cntr=0.3,0.1

Type RM Length L Ch R = 1 ,22352   ,443,443,443
BEGIN DESCRIPTION:
UNT023 IN SPCR 33.0
END DESCRIPTION:
XS GIS Cut Line= 4
      2247619.38     13272153.42      2247973.58     13271887.77
      2248322.54     13271601.31      2248661.08     13271314.85
#Sta/Elev= 30
  4254.3  237.37  4293.1  236.12  4328.5  233.52  4351.4  233.38  4386.9  230.46
  4401.4  231.23  4414.7  229.34  4457.7  228.63  4528.5  223.53  4614.7  220.26
  4657.7  217.75  4672.3  217.82  4757.1  213.29  4899.2  209.98  4913.6  210.82
  4927.9  209.22  4935.3  209.45    4997  207.76  4999.8  207.26    5003  207.76
    5027  209.89  5197.6  221.03  5283.4  225.35  5353.6  230.76  5439.4  234.64
  5538.2  237.22    5546  238.07  5566.8  237.85  5574.5  239.06    5592  239.26
#Mann= 3 ,-1 , 0
  4254.3     .05       0    4997     .03       0    5003     .05       0
Bank Sta=4935.3,5027
XS Rating Curve= 0 ,0
Exp/Cntr=0.3,0.1

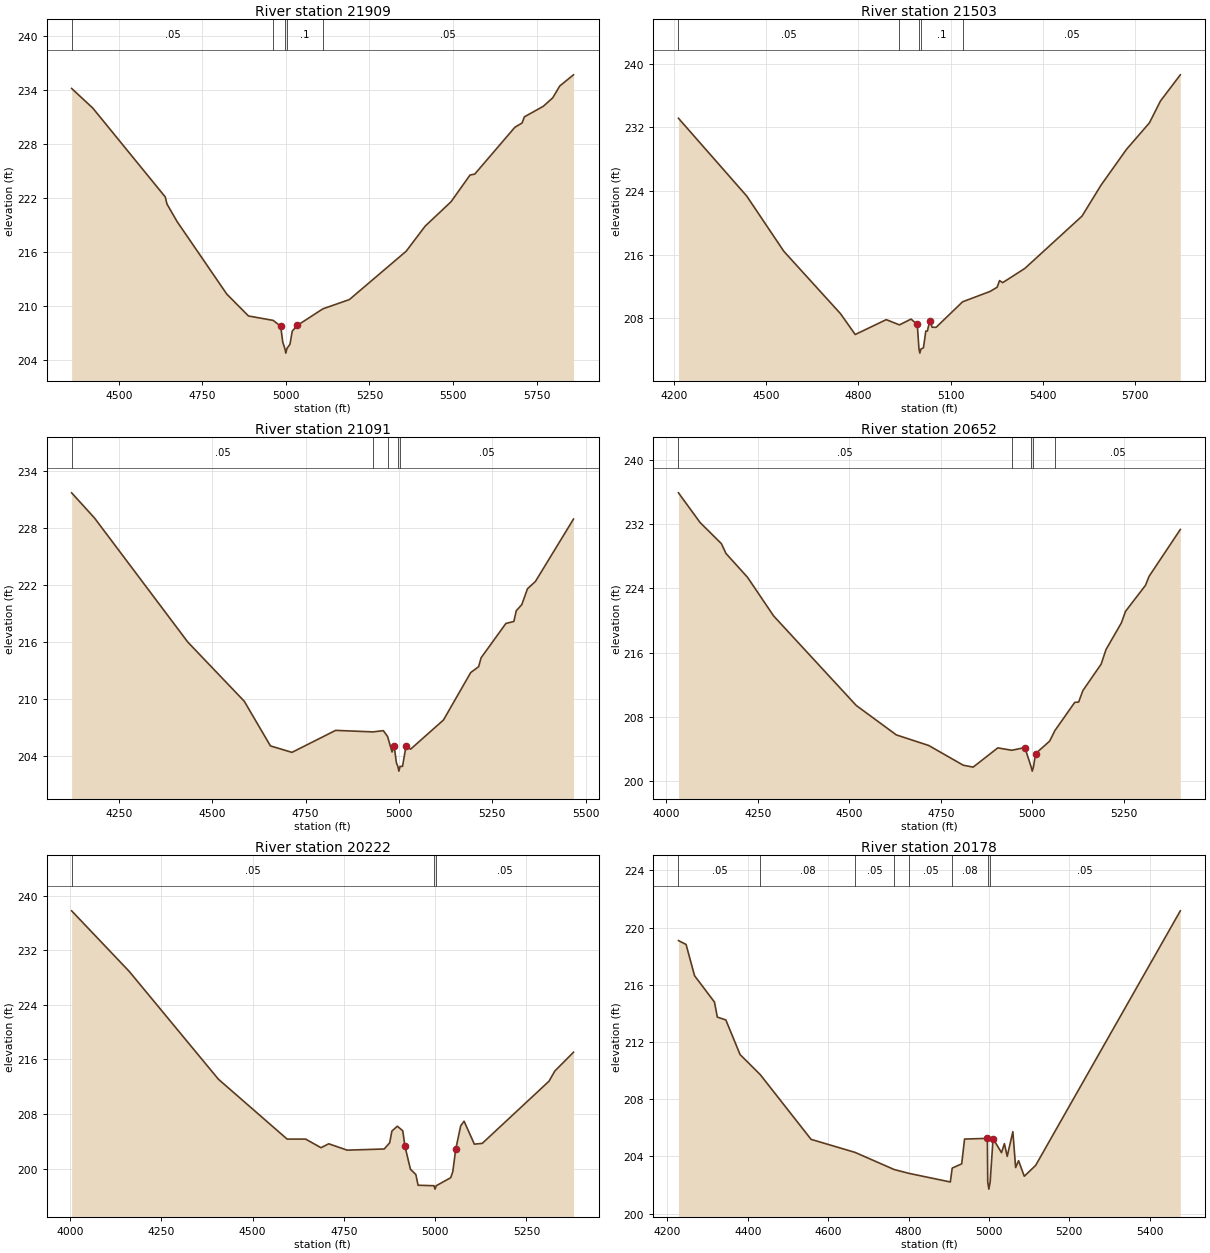
Type RM Length L Ch R = 1 ,21909   ,406,406,406
BEGIN DESCRIPTION:
UNT023 IN SPCR 32.0
END DESCRIPTION:
XS GIS Cut Line= 4
      2247754.87     13272278.38      2248150.66     13272226.31
      2248556.91     13271997.14      2249019.27     13271560.76
#Sta/Elev= 30
    4359  234.14  4422.4  231.96  4639.1  222.11  4644.3  221.32  4674.5  219.38
  4823.1  211.34  4888.1  208.91    4962  208.42  4984.4  207.77  4990.7     206
    4997  205.29  4999.8  204.79    5003  205.29  5012.3  205.78  5018.9  207.22
    5034  207.86  5110.6   209.7    5190  210.73  5359.9  216.09  5416.6  218.87
  5494.2  221.58  5550.9  224.54    5565  224.64  5685.2  229.84  5706.6  230.31
  5713.5  230.99  5770.1  232.16  5798.5  233.11  5819.5  234.42  5860.4  235.65
#Mann= 5 ,-1 , 0
    4359     .05       0    4962      .1       0    4997     .07       0
    5003      .1       0  5110.6     .05       0
Bank Sta=4984.4,5034
XS Rating Curve= 0 ,0
Exp/Cntr=0.3,0.1

Type RM Length L Ch R = 1 ,21503   ,412,412,412
BEGIN DESCRIPTION:
UNT023 IN SPCR 31.0
END DESCRIPTION:
XS GIS Cut Line= 3
      2247787.76     13272346.86      2248587.72     13272446.85
      2249387.71     13272246.86
#Sta/Elev= 30
  4215.4  233.14  4437.1  223.37    4558  216.41  4741.9  208.58  4789.8  205.96
  4890.6  207.83  4933.4  207.17  4971.2   207.9  4991.4  207.22    4997  204.12
  4999.8  203.62    5003  204.12  5011.5  204.29  5019.1  206.39  5024.2  206.39
  5031.9  207.69  5039.6  206.88  5052.5  206.86  5138.6  210.07  5227.7  211.37
  5250.9   211.9  5258.7  212.74    5269  212.48  5341.1  214.27  5526.7  220.84
  5588.5  224.73    5671  229.22  5745.7  232.56  5781.8  235.32  5846.2   238.6
#Mann= 5 ,-1 , 0
  4215.4     .05       0  4933.4      .1       0    4997     .07       0
    5003      .1       0  5138.6     .05       0
Bank Sta=4991.4,5031.9
XS Rating Curve= 0 ,0
Exp/Cntr=0.3,0.1

Type RM Length L Ch R = 1 ,21091   ,439,439,439
BEGIN DESCRIPTION:
UNT023 IN SPCR 30.0
END DESCRIPTION:
XS GIS Cut Line= 3
      2247787.76     13272496.87      2248587.72     13272846.85
      2248987.75     13273096.87
#Sta/Elev= 30
  4122.8  231.75    4184   229.1  4434.2     216  4585.5  209.76  4655.6  205.05
  4713.3  204.37  4830.3  206.69  4930.4  206.53  4958.2  206.66  4969.5  206.04
  4981.5  204.41    4987  205.08  4993.2  203.26    4997  202.89  4999.8  202.39
    5003  202.89  5009.5  202.89    5019  205.04  5031.3  204.71  5119.2  207.78
  5192.3  212.79  5213.5  213.41    5220  214.34  5286.6  217.97  5307.9  218.18
  5314.4  219.31  5329.1  219.95  5344.4  221.63  5365.7   222.4  5467.7  228.98
#Mann= 5 ,-1 , 0
  4122.8     .05       0  4930.4      .1       0  4969.5     .05       0
    4997     .03       0    5003     .05       0
Bank Sta=4987,5019
XS Rating Curve= 0 ,0
Exp/Cntr=0.3,0.1

Type RM Length L Ch R = 1 ,20652   ,430,430,430
BEGIN DESCRIPTION:
UNT023 IN SPCR 29.0
END DESCRIPTION:
XS GIS Cut Line= 3
      2247637.72     13272746.85      2248437.72     13273246.85
      2248837.72     13273396.85
#Sta/Elev= 30
  4033.6  235.93  4092.6  232.23  4150.9  229.59  4163.3  228.37  4222.3  225.39
  4293.6  220.57  4518.9  209.42  4628.5  205.74    4717  204.42  4811.3  201.96
  4838.4  201.72  4905.7  204.12  4943.9  203.82  4979.7  204.16    4997  201.72
  4999.8  201.22    5003  201.72    5009  203.41  5047.3  204.96  5061.4  206.26
  5115.8  209.79  5126.5  209.84  5138.1  211.27  5187.9  214.56  5201.3  216.39
  5243.1   219.7  5254.7  221.16    5309  224.39  5318.8  225.51  5404.2  231.36
#Mann= 5 ,-1 , 0
  4033.6     .05       0  4943.9      .1       0    4997     .07       0
    5003      .1       0  5061.4     .05       0
Bank Sta=4979.7,5009
XS Rating Curve= 0 ,0
Exp/Cntr=0.3,0.1

Type RM Length L Ch R = 1 ,20222   ,44,44,44
BEGIN DESCRIPTION:
UNT023 IN SPCR 28.0
END DESCRIPTION:
XS GIS Cut Line= 3
      2247587.69     13272746.82      2248137.72     13273546.85
      2248487.74     13273746.86
#Sta/Elev= 30
  4004.8  237.78  4162.6   228.9  4406.7  213.11  4594.8  204.34  4645.5  204.34
  4687.5  203.08  4708.7  203.65  4759.2  202.72  4860.7  202.89  4875.6   203.8
  4881.6  205.51  4896.5  206.23  4911.4  205.55  4917.5  203.26  4932.4  199.93
  4947.3  199.14  4953.3  197.58    4997  197.51  4999.8  197.01    5003  197.51
  5042.6  198.68  5048.4  199.57  5056.3  202.83    5070  206.28  5079.3  206.96
  5107.4   203.6    5129  203.71  5311.8  212.82  5327.7  214.31  5378.8  217.06
#Mann= 3 ,-1 , 0
  4004.8     .05       0    4997    .035       0    5003     .05       0
Bank Sta=4917.5,5056.3
XS Rating Curve= 0 ,0
Exp/Cntr=0.3,0.1

Type RM Length L Ch R = 1 ,20178   ,115,115,115
BEGIN DESCRIPTION:
Mapping XS 07e6c517
END DESCRIPTION:
XS GIS Cut Line= 3
      2247581.38     13273046.45      2248115.24     13273577.72
      2248477.24     13273916.27
#Sta/Elev= 30
  4227.4  219.09  4246.3  218.82  4267.5  216.63    4317  214.79  4324.1  213.74
  4345.3  213.54  4380.7  211.12  4430.8  209.72  4557.4  205.19  4666.7  204.28
  4764.2  203.08  4801.3  202.81  4903.9  202.21  4908.5  203.18  4932.2  203.48
  4939.3  205.21    4996  205.26    4997  202.21  4999.8  201.71    5003  202.21
  5010.2  205.24  5031.2  204.26  5038.5  204.89  5045.4     204  5059.5  205.73
  5066.4  203.22  5073.7   203.7  5087.9  202.61  5116.2  203.37  5476.2  221.17
#Mann= 8 ,-1 , 0
  4227.4     .05       0  4430.8     .08       0  4666.7     .05       0
  4764.2     .08       0  4801.3     .05       0  4908.5     .08       0
    4997     .07       0    5003     .05       0
Bank Sta=4996,5010.2
XS Rating Curve= 0 ,0
Exp/Cntr=0.3,0.1