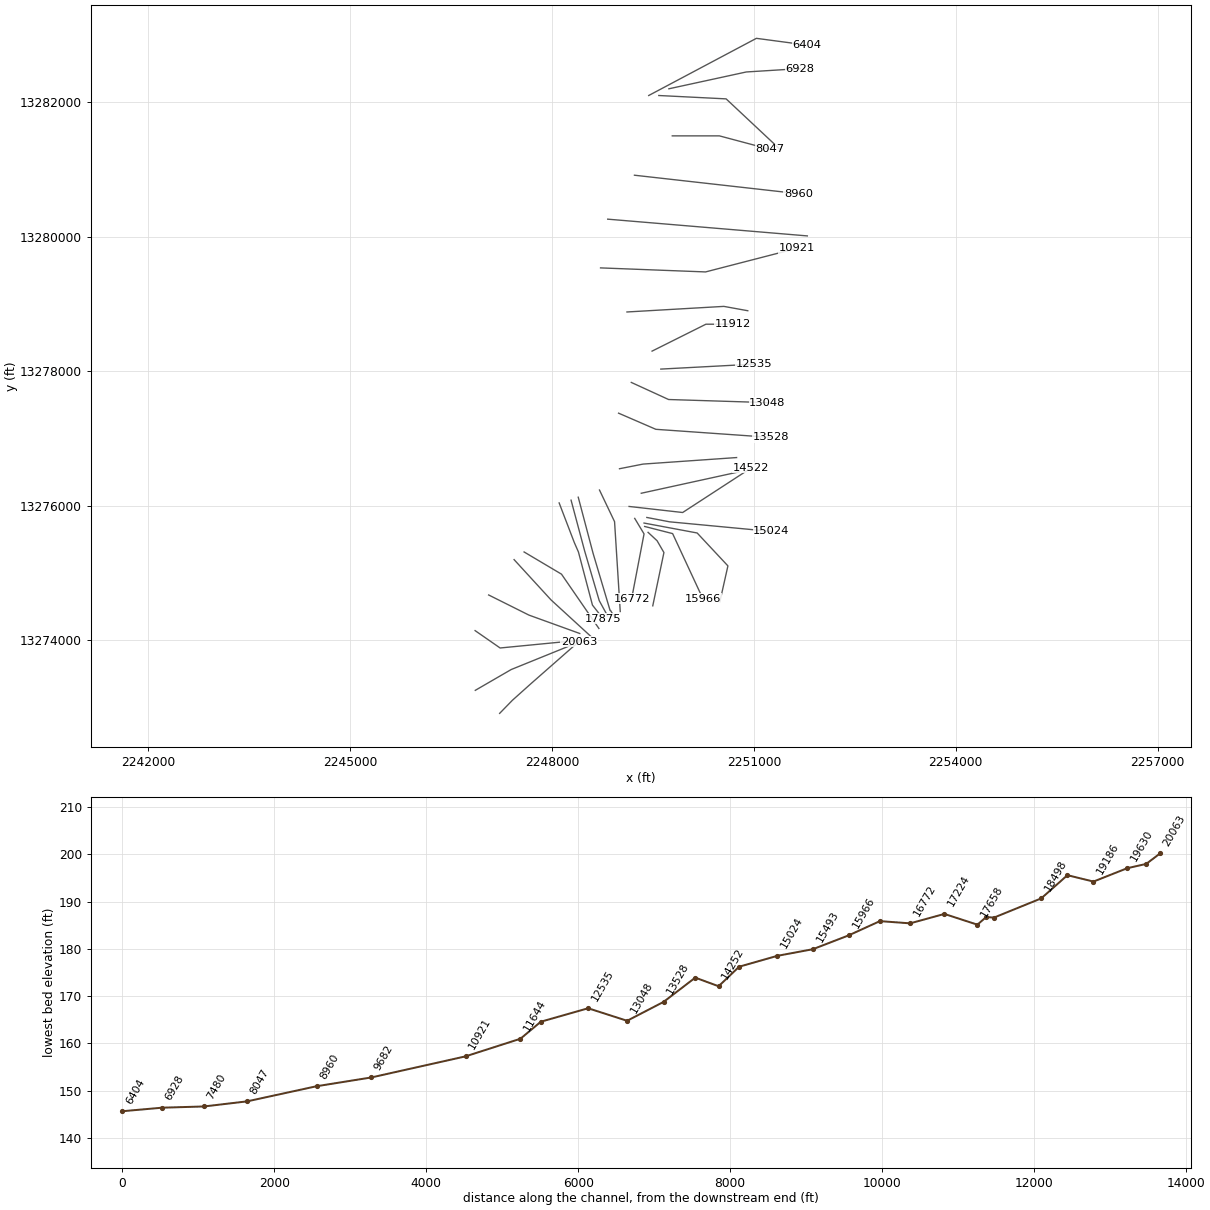
HEC-RAS study UNT023 IN SPCR.prj: UNT023 IN SPCR Base Level Engineering

--- UNT023 IN SPCR.g01 (geometry) --- (continued)

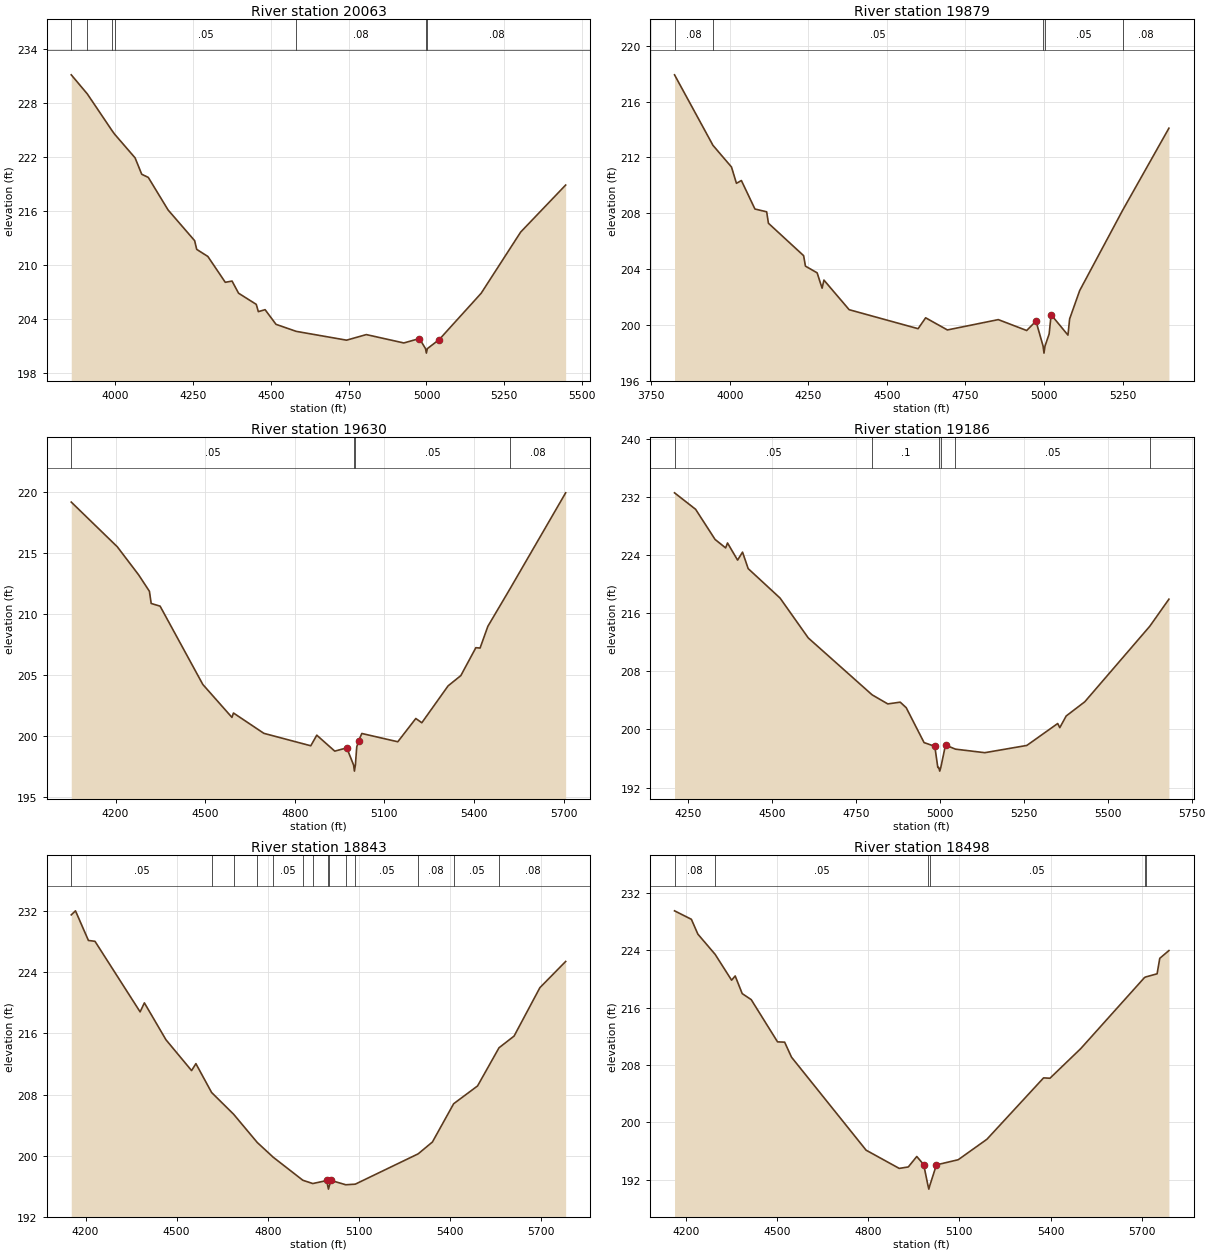
Type RM Length L Ch R = 1 ,20063   ,184,184,184
BEGIN DESCRIPTION:
Mapping XS 7762a345
END DESCRIPTION:
XS GIS Cut Line= 4
      2247223.18     13272911.17      2247412.71     13273105.97
      2247683.82     13273348.98        2248400.     13273978.35
#Sta/Elev= 30
  3858.2  231.15  3909.8  229.03  3988.7  224.98  3997.2  224.57  4063.4  221.92
  4084.7   220.1  4105.8  219.75  4169.5  216.13  4254.8  212.72  4261.5  211.75
  4297.4  210.96  4353.4  208.09  4375.1  208.23    4396  206.88  4452.9  205.64
  4459.6  204.83  4481.3  205.05  4516.4  203.42  4581.3  202.64  4743.2  201.66
  4806.8  202.28  4927.3  201.35  4977.5  201.84    4997  200.72  4999.8  200.22
    5003  200.72  5041.1  201.73  5175.8  206.87    5303  213.68  5447.5   218.9
#Mann= 7 ,-1 , 0
  3858.2     .08       0  3909.8     .05       0  3988.7     .08       0
  3997.2     .05       0  4581.3     .08       0    4997     .07       0
    5003     .08       0
Bank Sta=4977.5,5041.1
XS Rating Curve= 0 ,0
Exp/Cntr=0.3,0.1

Type RM Length L Ch R = 1 ,19879   ,249,249,249
BEGIN DESCRIPTION:
UNT023 IN SPCR 27.0
END DESCRIPTION:
XS GIS Cut Line= 3
      2246861.24     13273253.67       2247394.5     13273562.85
      2248280.81     13273922.47
#Sta/Elev= 30
  3824.4  217.92  3946.7  212.87  4005.6  211.32  4021.4  210.15  4037.1  210.35
  4080.2  208.31  4117.5  208.11  4123.2  207.29  4235.1  204.97  4240.9  204.22
  4278.1  203.74  4293.9  202.64  4299.7  203.22    4380   201.1  4599.3  199.74
  4623.3  200.52  4692.5  199.65  4854.4  200.39  4944.8  199.61  4974.3  200.28
    4997  198.49  4999.8  197.99    5003  198.49  5016.2  199.36  5022.5  200.74
  5076.1  199.28  5081.4  200.44  5113.4  202.47  5250.3  208.23  5397.3   214.1
#Mann= 5 ,-1 , 0
  3824.4     .08       0  3946.7     .05       0    4997     .03       0
    5003     .05       0  5250.3     .08       0
Bank Sta=4974.3,5022.5
XS Rating Curve= 0 ,0
Exp/Cntr=0.3,0.1

Type RM Length L Ch R = 1 ,19630   ,444,444,444
BEGIN DESCRIPTION:
UNT023 IN SPCR 26.0
END DESCRIPTION:
XS GIS Cut Line= 3
      2246858.44     13274141.45        2247230.     13273883.35
      2248426.96     13273999.64
#Sta/Elev= 30
  4051.9  219.17  4206.1   215.5  4277.7  213.19  4313.5  211.85  4319.5  210.85
  4349.3  210.63  4492.4   204.2  4589.8   201.5  4594.9  201.86  4696.8  200.19
  4853.7  199.17  4873.8  200.04    4934  198.73  4974.2     199    4997  197.59
  4999.8  197.09    5003  197.59  5007.6  199.08  5014.4   199.6  5024.5  200.18
    5145   199.5  5205.3  201.41  5225.4  201.06  5313.5  204.09    5356  204.93
  5406.3  207.22  5420.4  207.19  5446.4  208.97    5522  212.11  5706.9  219.93
#Mann= 4 ,-1 , 0
  4051.9     .05       0    4997     .03       0    5003     .05       0
    5522     .08       0
#XS Ineff= 1 ,-1
    4720 4873.28  199.97
Permanent Ineff=
       F
Bank Sta=4974.2,5014.4
XS Rating Curve= 0 ,0
Exp/Cntr=0.3,0.1

Type RM Length L Ch R = 1 ,19186   ,343,343,343
BEGIN DESCRIPTION:
Mapping XS 9c9e8341
END DESCRIPTION:
XS GIS Cut Line= 3
      2247059.74     13274671.51      2247658.66     13274372.05
      2248413.31     13274098.81
#Sta/Elev= 30
  4210.1   232.6  4272.9  230.33  4330.8  226.18  4362.3  225.01  4367.9  225.69
  4397.9  223.33  4412.6  224.43  4429.4  222.16  4524.4   218.1  4608.3  212.61
  4798.5  204.77  4845.1  203.52  4882.2  203.76    4900     203  4953.2  198.19
  4985.1  197.68  4994.1  194.76    4997  194.76  4999.8  194.26    5003  194.76
    5017  197.86  5046.4  197.29    5134   196.8  5259.2   197.8  5351.1  200.82
  5357.3  200.25  5376.4  201.86  5431.7  203.81  5625.5  214.23  5682.3  217.95
#Mann= 6 ,-1 , 0
  4210.1     .05       0  4798.5      .1       0    4997     .07       0
    5003      .1       0  5046.4     .05       0  5625.5     .08       0
Bank Sta=4985.1,5017
XS Rating Curve= 0 ,0
Exp/Cntr=0.3,0.1

Type RM Length L Ch R = 1 ,18843   ,345,345,345
BEGIN DESCRIPTION:
UNT023 IN SPCR 25.0
END DESCRIPTION:
XS GIS Cut Line= 3
      2247437.69     13275196.89      2247987.72     13274596.85
       2248587.7     13274046.88
#Sta/Elev= 30
  4152.9  231.52  4166.8  232.05  4209.4  228.17    4231  228.06  4379.6  218.82
  4393.7     220  4464.7  215.17  4549.1  211.13  4563.3  212.04  4615.1  208.26
  4687.4  205.42  4765.3  201.72  4817.8  199.79  4915.5  196.77  4948.2  196.34
  4994.9  196.74    4997  196.11  4999.8  195.61    5003  196.11  5009.1  196.74
  5056.9  196.18  5088.1  196.26  5295.2  200.23  5342.1  201.78    5412  206.79
  5490.7  209.12  5561.4  214.12    5611  215.65    5696  221.99  5780.8  225.42
#Mann= 14 ,-1 , 0
  4152.9     .05       0  4615.1     .08       0  4687.4     .05       0
  4765.3     .08       0  4817.8     .05       0  4915.5     .08       0
  4948.2     .05       0    4997     .03       0    5003     .05       0
  5056.9     .08       0  5088.1     .05       0  5295.2     .08       0
    5412     .05       0  5561.4     .08       0
Bank Sta=4994.9,5009.1
XS Rating Curve= 0 ,0
Exp/Cntr=0.3,0.1

Type RM Length L Ch R = 1 ,18498   ,623,623,623
BEGIN DESCRIPTION:
UNT023 IN SPCR 24.0
END DESCRIPTION:
XS GIS Cut Line= 3
      2247586.31     13275310.84      2248141.87     13274980.97
      2248697.44     13274173.67
#Sta/Elev= 30
  4163.4   229.5  4218.8  228.32  4240.2  226.25    4297  223.43  4351.1  219.83
  4362.9  220.42    4386  217.96  4415.6  217.12  4502.3  211.23  4525.6  211.19
  4548.1   209.1  4793.5  196.13  4902.4  193.59  4932.2  193.79  4960.2  195.25
  4982.9  194.12    4997   191.2  4999.8   190.7    5003   191.2  5024.8  194.08
  5096.5   194.8  5190.8  197.65  5377.2  206.21  5398.2  206.16  5499.7   210.3
  5709.4  220.21  5713.9  220.29  5750.6  220.72  5759.4  222.88  5789.5  223.96
#Mann= 6 ,-1 , 0
  4163.4     .08       0    4297     .05       0    4997     .03       0
    5003     .05       0  5709.4     .08       0  5713.9     .05       0
Bank Sta=4982.9,5024.8
XS Rating Curve= 0 ,0
Exp/Cntr=0.3,0.1

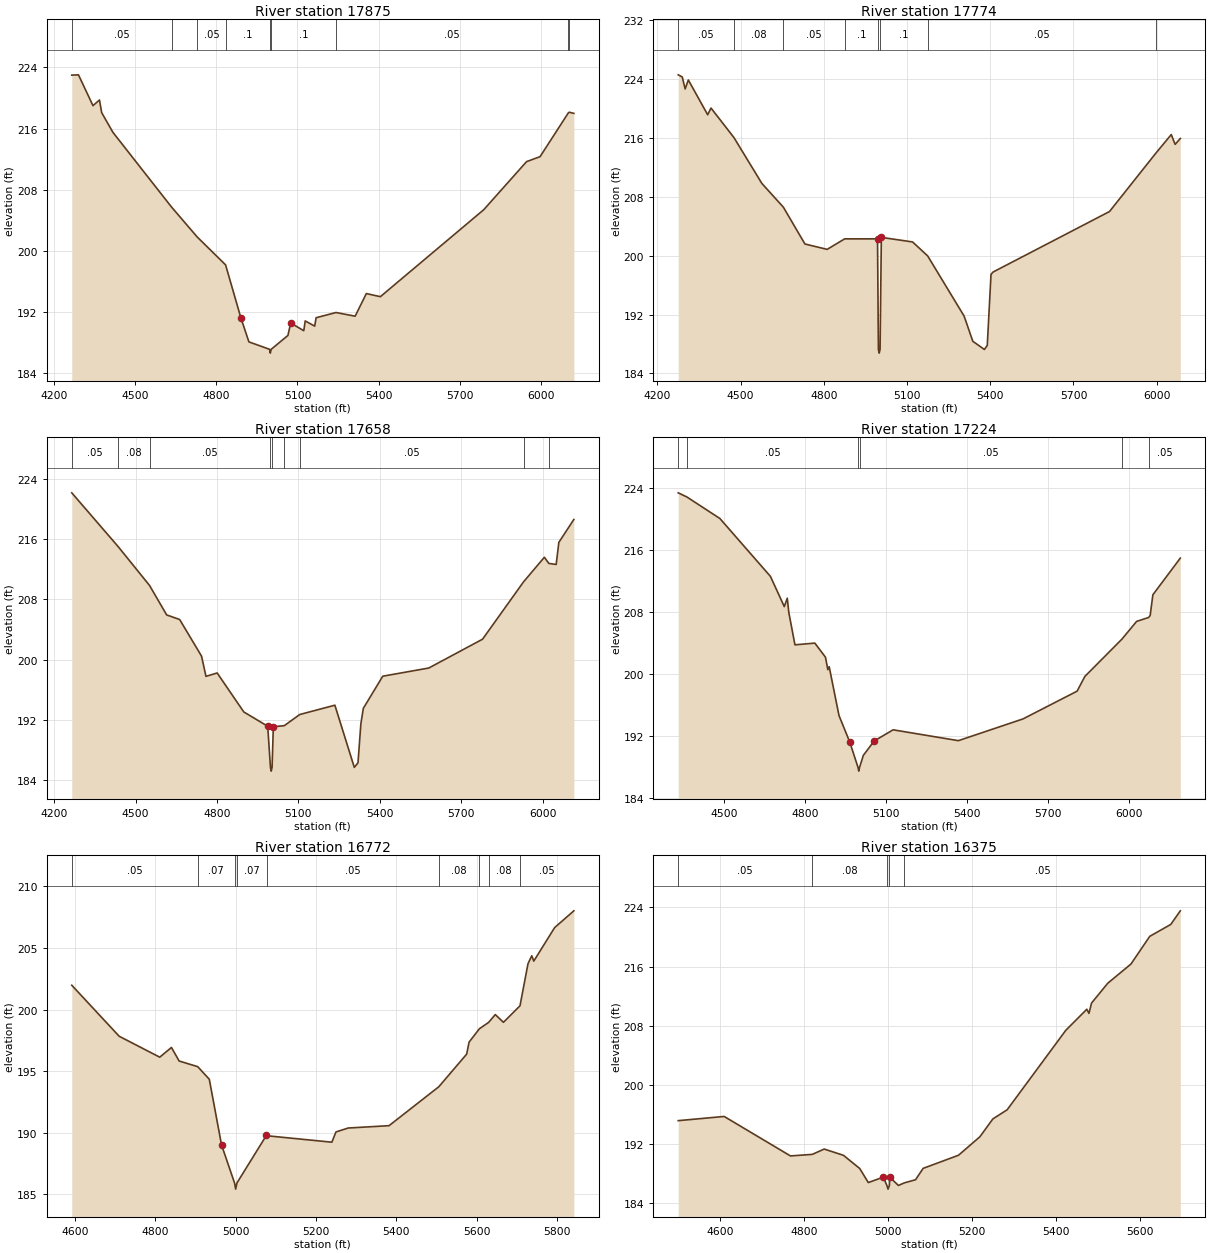
Type RM Length L Ch R = 1 ,17875   ,101,101,101
BEGIN DESCRIPTION:
UNT023 IN SPCR 23.0
END DESCRIPTION:
XS GIS Cut Line= 5
      2248107.17     13276039.96      2248332.85     13275449.72
      2248393.61     13275310.84      2248601.94     13274520.91
      2248757.96     13274321.55
#Sta/Elev= 30
  4266.8  222.98  4291.5  223.02  4345.1  218.99  4369.1  219.73  4377.2  218.08
  4418.5  215.51  4635.4  205.72  4730.1  201.81  4834.7  198.17  4891.1  191.25
  4920.8   188.1    4997  187.13  4999.8  186.63    5003  187.13  5064.8  188.94
  5075.1  190.57  5123.4  189.56  5128.6  190.84  5163.7  190.16  5168.9  191.26
  5242.4  191.94    5313  191.46  5354.3  194.42  5406.1  194.01  5787.7  205.38
  5945.9  211.67  5995.7  212.32  6100.2  218.05  6103.2  218.13  6120.4  217.98
#Mann= 9 ,-1 , 0
  4266.8     .05       0  4635.4     .08       0  4730.1     .05       0
  4834.7      .1       0    4997     .07       0    5003      .1       0
  5242.4     .05       0  6100.2     .08       0  6103.2     .05       0
Bank Sta=4891.1,5075.1
XS Rating Curve= 0 ,0
Exp/Cntr=0.3,0.1

Type RM Length L Ch R = 1 ,17774   ,116,116,116
BEGIN DESCRIPTION:
Mapping XS f96e32c0
END DESCRIPTION:
XS GIS Cut Line= 4
      2248284.34     13276080.87      2248486.22     13275324.75
      2248702.79     13274586.95      2248826.92     13274360.59
#Sta/Elev= 30
  4275.5  224.58    4290  224.29  4300.4  222.66  4311.9  223.88  4381.7  219.15
  4393.5  220.07  4476.2  216.06    4577  209.82  4654.5  206.59  4732.2  201.59
  4812.3  200.86  4875.6  202.29  4993.8  202.29    4997  187.26  4999.8  186.76
    5003  187.26  5007.6  202.49  5120.2  201.87  5174.4  199.98    5306  191.79
  5337.3  188.37    5379  187.26  5389.4  187.81  5402.9  197.46  5410.3  197.78
  5829.9     206  5997.6  213.96  6052.6  216.46  6066.6  215.13  6085.2  215.93
#Mann= 8 ,-1 , 0
  4275.5     .05       0  4476.2     .08       0  4654.5     .05       0
  4875.6      .1       0    4997     .07       0    5003      .1       0
  5174.4     .05       0  5997.6     .08       0
Bank Sta=4993.8,5007.6
XS Rating Curve= 0 ,0
Exp/Cntr=0.3,0.1

Type RM Length L Ch R = 1 ,17658   ,434,434,434
BEGIN DESCRIPTION:
Mapping XS 4915d94d
END DESCRIPTION:
XS GIS Cut Line= 5
      2248390.79     13276124.91      2248611.02     13275291.71
      2248864.29     13274440.13      2248871.64     13274440.13
      2248918.64     13274360.58
#Sta/Elev= 30
  4264.9   222.2  4435.8  215.04  4551.4  209.87  4614.6  205.94  4662.4  205.33
    4743  200.46  4759.4  197.76  4800.7  198.21  4898.8  193.02  4986.9  191.12
    4997  185.64  4999.8  185.14    5003  185.64  5007.6  191.05  5047.9  191.19
  5104.9  192.68  5234.4  193.92    5306  185.64  5319.6  186.25    5330  191.39
  5339.2   193.5  5410.8  197.78  5580.4  198.87  5778.6  202.71  5929.9  210.36
  6006.3  213.62  6022.7   212.8  6049.8  212.66  6059.6   215.6  6114.9  218.65
#Mann= 9 ,-1 , 0
  4264.9     .05       0  4435.8     .08       0  4551.4     .05       0
    4997     .03       0    5003     .05       0  5047.9      .1       0
  5104.9     .05       0  5929.9     .08       0  6022.7     .05       0
Bank Sta=4986.9,5007.6
XS Rating Curve= 0 ,0
Exp/Cntr=0.3,0.1

Type RM Length L Ch R = 1 ,17224   ,452,452,452
BEGIN DESCRIPTION:
Mapping XS 9a878d96
END DESCRIPTION:
XS GIS Cut Line= 3
      2248706.45      13276231.4      2248930.37     13275761.56
      2249014.79     13274425.49
#Sta/Elev= 30
  4331.4  223.39  4363.6  222.85  4485.7  220.07  4672.8  212.59  4724.1  208.68
  4735.2  209.77  4740.9  207.92  4763.6  203.74  4837.3  203.96  4876.6  202.14
  4885.4  200.53  4890.4  200.91  4926.7   194.6  4966.8  191.15    4997  187.91
  4999.8  187.41    5003  187.91  5016.9  189.45    5057  191.31  5127.1  192.75
  5368.8  191.35  5608.1  194.16  5808.5  197.75  5837.1  199.65  5974.3  204.47
  6028.9  206.77    6073  207.27    6079  207.53    6089  210.21  6190.6  214.95
#Mann= 6 ,-1 , 0
  4331.4     .08       0  4363.6     .05       0    4997     .03       0
    5003     .05       0  5974.3     .08       0    6073     .05       0
Bank Sta=4966.8,5057
XS Rating Curve= 0 ,0
Exp/Cntr=0.3,0.1

Type RM Length L Ch R = 1 ,16772   ,397,397,397
BEGIN DESCRIPTION:
Mapping XS c6879a15
END DESCRIPTION:
XS GIS Cut Line= 3
      2249229.97     13275809.86       2249368.4     13275579.14
       2249183.8     13274614.61
#Sta/Elev= 30
  4591.4  201.97  4709.5  197.83  4810.6  196.13  4839.8  196.92  4858.9  195.82
  4905.3  195.36  4934.1  194.34  4964.6  189.01    4997  185.92  4999.8  185.42
    5003  185.92  5076.6  189.79  5078.4  189.75  5239.5  189.23  5249.7  190.06
  5280.2  190.38    5382  190.57    5506  193.73  5575.5  196.38  5581.4  197.35
  5607.2  198.44    5630  198.95  5646.8  199.59  5667.1  198.96  5708.3   200.3
  5728.2  203.71  5737.6  204.36  5742.7  203.93  5794.7  206.65  5842.5  208.01
#Mann= 9 ,-1 , 0
  4591.4     .05       0  4905.3     .07       0    4997     .07       0
    5003     .07       0  5078.4     .05       0    5506     .08       0
  5607.2     .05       0    5630     .08       0  5708.3     .05       0
Bank Sta=4964.6,5076.6
XS Rating Curve= 0 ,0
Exp/Cntr=0.3,0.1

Type RM Length L Ch R = 1 ,16375   ,409,409,409
BEGIN DESCRIPTION:
Mapping XS 61c950f3
END DESCRIPTION:
XS GIS Cut Line= 4
      2249428.36     13275602.24      2249562.22     13275477.61
      2249663.75     13275302.25      2249497.96     13274510.14
#Sta/Elev= 30
  4500.5  195.15  4609.8  195.72  4767.6  190.38  4819.5  190.59  4847.9  191.31
  4893.8  190.46  4932.4  188.68  4952.8  186.78  4988.6  187.51    4997  186.39
  4999.8  185.89    5003  186.39  5003.9   187.5  5024.4  186.39  5038.9  186.74
  5065.2  187.16  5083.4   188.7  5167.4  190.47  5218.5  192.98  5249.1  195.38
  5283.2  196.62  5422.8  207.37  5472.8  210.22  5477.9  209.66  5484.1  211.06
  5522.7  213.74  5577.8  216.33  5622.6  220.08  5672.6  221.69  5695.3  223.53
#Mann= 5 ,-1 , 0
  4500.5     .05       0  4819.5     .08       0    4997     .07       0
    5003     .08       0  5038.9     .05       0
Bank Sta=4988.6,5003.9
XS Rating Curve= 0 ,0
Exp/Cntr=0.3,0.1

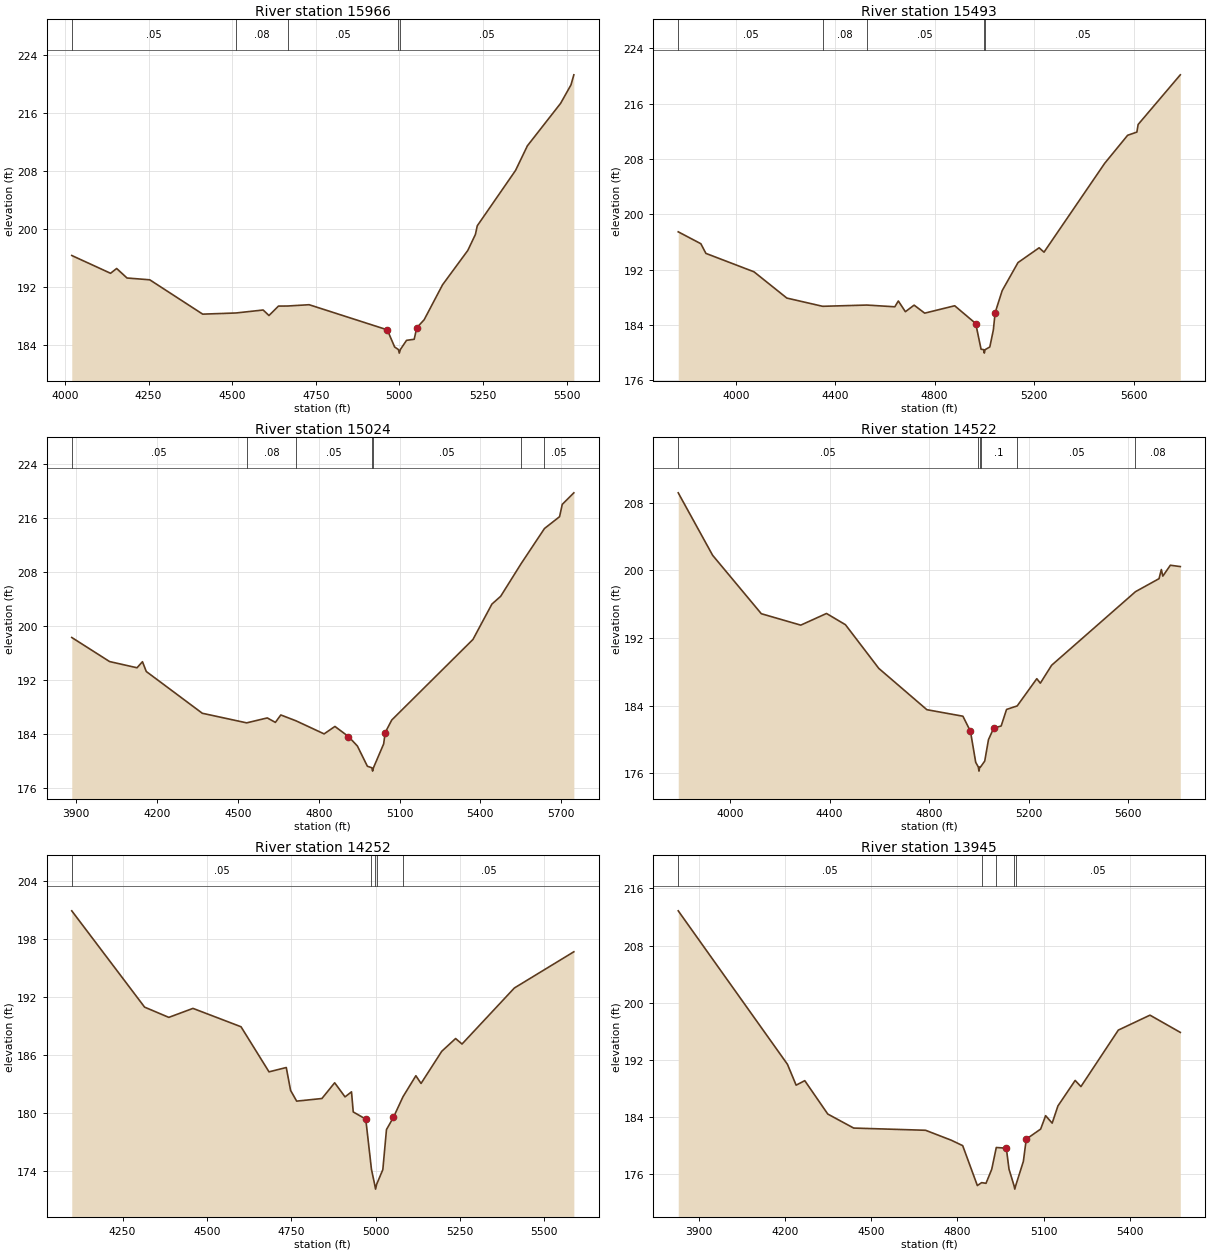
Type RM Length L Ch R = 1 ,15966   ,473,473,473
BEGIN DESCRIPTION:
Mapping XS 5b3d6c92
END DESCRIPTION:
XS GIS Cut Line= 3
      2249377.66     13275689.89      2249792.96     13275583.75
       2250244.8     13274610.91
#Sta/Elev= 30
  4020.4  196.34  4136.4  193.89  4154.6  194.55  4185.6  193.24  4253.7  192.99
  4411.9  188.26  4511.2  188.42  4592.7  188.83  4610.1  188.07  4638.5  189.37
  4665.8  189.38  4730.1  189.56  4963.8   186.1  4985.9  183.73    4997  183.39
  4999.8  182.89    5003  183.39  5021.4  184.65  5044.3   184.8  5052.1  186.39
  5074.1  187.49  5129.2  192.31  5204.5  197.03  5227.4  199.24  5232.9  200.43
  5347.4  208.06  5382.8  211.45  5482.1   217.3  5513.2  219.85  5521.7  221.23
#Mann= 5 ,-1 , 0
  4020.4     .05       0  4511.2     .08       0  4665.8     .05       0
    4997    .035       0    5003     .05       0
Bank Sta=4963.8,5052.1
XS Rating Curve= 0 ,0
Exp/Cntr=0.3,0.1

Type RM Length L Ch R = 1 ,15493   ,469,469,469
BEGIN DESCRIPTION:
Mapping XS c46caf62
END DESCRIPTION:
XS GIS Cut Line= 4
      2249368.35     13275740.67      2250157.53     13275592.98
       2250614.4     13275103.81      2250494.79     13274570.17
#Sta/Elev= 30
  3768.9  197.49  3859.8  195.77  3880.2  194.37  4073.5  191.71  4205.7  187.91
  4349.6  186.72  4527.4   186.9  4639.9  186.65    4654  187.49  4682.4  185.94
  4717.5  186.89    4760  185.73  4880.7   186.8  4965.2  184.23  4986.7  180.52
    4997  180.45  4999.8  179.95    5003  180.45  5021.9  180.84  5036.1  183.29
  5043.4  185.81  5071.7  188.99  5135.2  193.04  5220.2  195.18  5239.9  194.55
    5484   207.4  5576.2  211.45  5613.3  211.91  5618.4  213.01    5788  220.19
#Mann= 5 ,-1 , 0
  3768.9     .05       0  4349.6     .08       0  4527.4     .05       0
    4997    .035       0    5003     .05       0
Bank Sta=4965.2,5043.4
XS Rating Curve= 0 ,0
Exp/Cntr=0.3,0.1

Type RM Length L Ch R = 1 ,15024   ,502,502,502
BEGIN DESCRIPTION:
Mapping XS b27cd2b0
END DESCRIPTION:
XS GIS Cut Line= 3
      2249409.98     13275823.72      2249746.81     13275759.12
      2251260.49     13275616.06
#Sta/Elev= 30
  3883.3  198.31  4023.6  194.75  4125.4  193.83  4145.7  194.73  4159.8  193.28
  4367.8   187.1  4532.4  185.68  4608.9  186.41    4639  185.75  4659.1  186.85
  4715.7  185.98  4819.8  184.05    4860  185.15  4910.2  183.66  4943.3  182.26
  4980.5  179.26    4997  179.04  4999.8  178.54    5003  179.04  5040.8  182.56
  5046.6  184.25  5070.9   186.1  5372.3  198.02  5442.6  203.25  5475.1   204.4
  5550.5   209.2  5637.7  214.43  5693.7  216.18  5703.7     218  5746.7  219.71
#Mann= 7 ,-1 , 0
  3883.3     .05       0  4532.4     .08       0  4715.7     .05       0
    4997    .035       0    5003     .05       0  5550.5     .08       0
  5637.7     .05       0
Bank Sta=4910.2,5046.6
XS Rating Curve= 0 ,0
Exp/Cntr=0.3,0.1

Type RM Length L Ch R = 1 ,14522   ,270,270,270
BEGIN DESCRIPTION:
Mapping XS 1c0d4cb8
END DESCRIPTION:
XS GIS Cut Line= 3
      2249146.04     13275987.43      2249942.02     13275897.41
      2250960.73     13276560.75
#Sta/Elev= 30
  3791.8  209.18  3929.9  201.79  4125.6  194.87    4284  193.52  4387.3   194.9
  4463.5  193.57  4597.4   188.4  4790.6  183.51  4935.3  182.74  4965.6  180.95
  4986.7  177.28    4997  176.74  4999.8  176.24    5003  176.74  5006.3  176.74
  5022.9  177.43    5038  179.97  5059.1  181.34  5088.9  181.58  5110.5  183.54
  5153.4  183.96  5232.1  187.18  5246.2  186.65  5291.6  188.77  5628.5  197.48
  5723.1  199.02  5732.3   200.1  5738.3  199.32  5768.5  200.61  5808.5  200.45
#Mann= 6 ,-1 , 0
  3791.8     .05       0    4997     .03       0    5003     .05       0
  5006.3      .1       0  5153.4     .05       0  5628.5     .08       0
Bank Sta=4965.6,5059.1
XS Rating Curve= 0 ,0
Exp/Cntr=0.3,0.1

Type RM Length L Ch R = 1 ,14252   ,307,307,307
BEGIN DESCRIPTION:
Mapping XS 8feacc1c
END DESCRIPTION:
XS GIS Cut Line= 2
       2249326.9     13276183.69      2250779.95     13276501.97
#Sta/Elev= 30
  4099.7  200.92  4315.5  190.95  4387.2  189.89  4458.8  190.82  4601.1  188.92
  4684.1  184.25  4735.2   184.7    4748  182.33    4766  181.22  4840.8  181.49
  4878.6  183.12  4909.3  181.66  4928.5  182.18  4933.6   180.1  4970.7  179.36
  4987.6  174.16    4997  172.61  4999.8  172.11    5003  172.61  5021.3  174.13
  5032.1  178.28  5052.6  179.53  5080.8  181.66  5119.2  183.85  5134.5  183.05
  5195.9  186.38  5236.9   187.7  5255.9  187.13  5410.9  192.93  5587.2  196.68
#Mann= 5 ,-1 , 0
  4099.7     .05       0  4987.6      .1       0    4997     .07       0
    5003      .1       0  5080.8     .05       0
Bank Sta=4970.7,5052.6
XS Rating Curve= 0 ,0
Exp/Cntr=0.3,0.1

Type RM Length L Ch R = 1 ,13945   ,417,417,417
BEGIN DESCRIPTION:
UNT023 IN SPCR 16.0
END DESCRIPTION:
XS GIS Cut Line= 3
      2249003.83     13276548.25      2249354.55     13276617.47
      2250743.19     13276714.35
#Sta/Elev= 30
    3827  212.85  4207.7  191.38  4237.8  188.47  4267.9   189.1  4348.1  184.43
  4438.3  182.47  4688.9  182.16  4779.1  180.76  4818.2  180.01  4869.3  174.43
  4884.3  174.84  4899.4  174.74  4919.4  176.71  4935.3  179.75  4970.2  179.66
  4979.6  176.72    4997  174.43  4999.8  173.93    5003  174.43  5029.7  177.82
  5039.7  180.92  5089.9  182.33  5107.2   184.2    5130  183.16    5150  185.56
  5210.1  189.13  5230.2  188.27  5360.5  196.17  5470.8  198.26  5576.5  195.85
#Mann= 5 ,-1 , 0
    3827     .05       0  4884.3      .1       0  4935.3     .05       0
    4997     .03       0    5003     .05       0
Bank Sta=4970.2,5039.7
XS Rating Curve= 0 ,0
Exp/Cntr=0.3,0.1

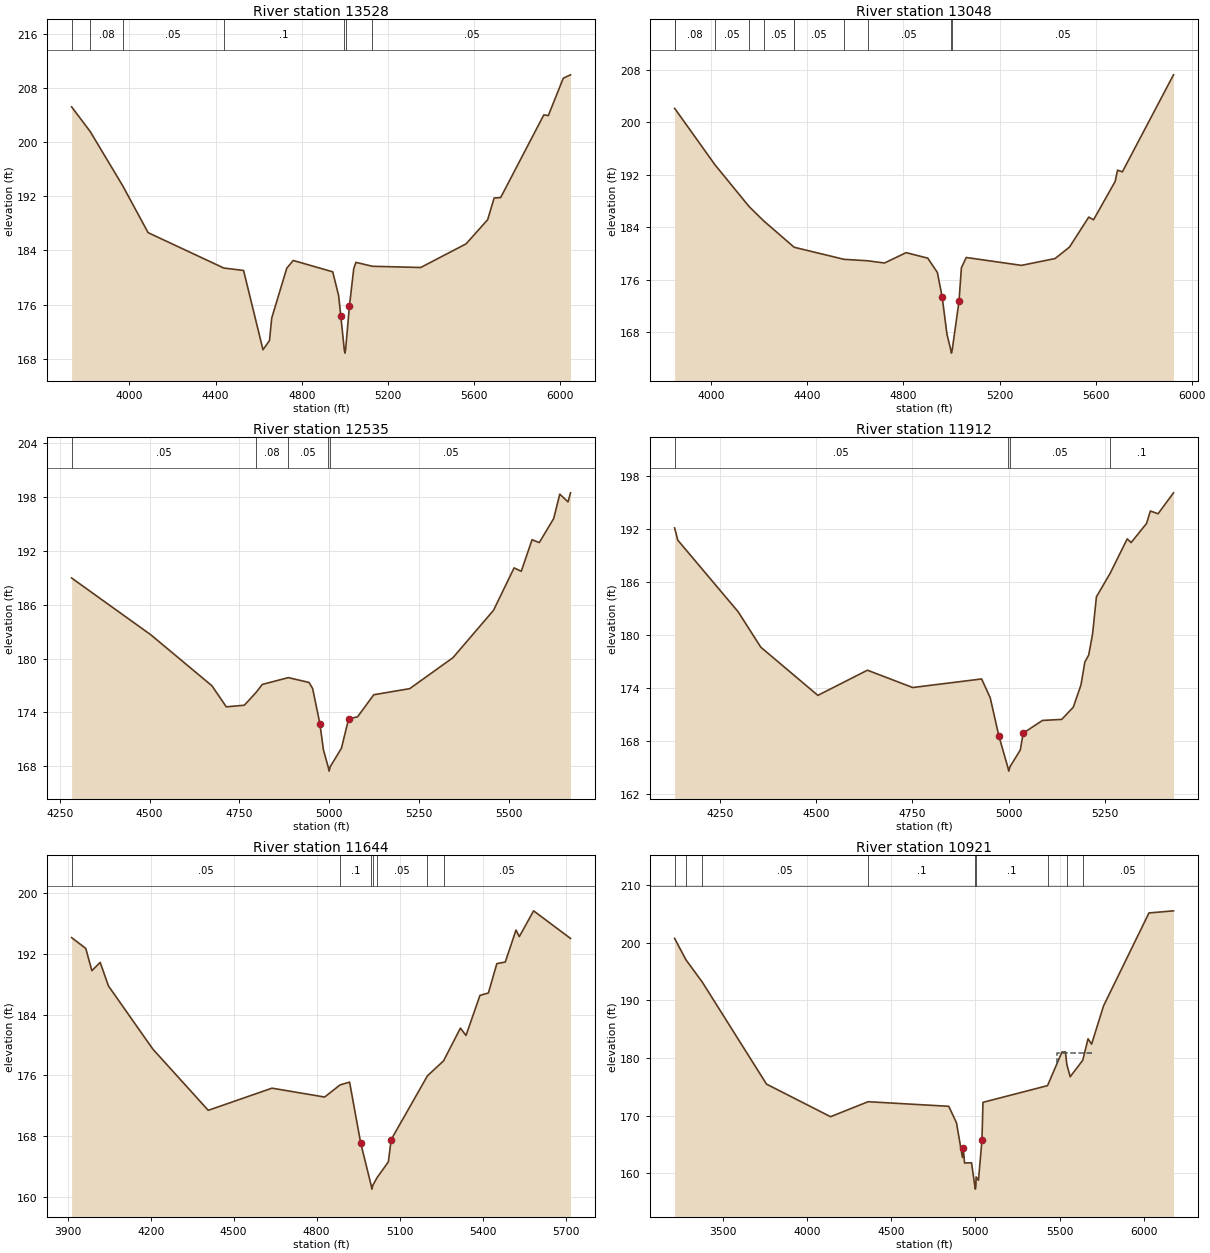
Type RM Length L Ch R = 1 ,13528   ,480,480,480
BEGIN DESCRIPTION:
Mapping XS 79c7992d
END DESCRIPTION:
XS GIS Cut Line= 3
        2248990.     13277374.29      2249543.76     13277134.33
      2251251.24     13277014.35
#Sta/Elev= 30
  3731.6  205.27    3818  201.61  3968.4   193.6  4086.6  186.64  4437.8   181.4
  4529.6  181.04  4619.8   169.3  4649.8  170.66  4660.3     174    4730  181.37
  4760.1  182.52  4943.3  180.84  4970.6  177.34  4980.7  174.32    4997   169.3
  4999.8   168.8    5003   169.3  5020.8  175.77  5040.8   181.3  5050.8  182.24
  5127.5  181.66  5351.6  181.48  5562.1  184.98  5662.3  188.56  5692.4  191.77
  5722.5  191.83    5923  204.08  5943.9  203.98  6013.2  209.51  6046.8  210.01
#Mann= 7 ,-1 , 0
  3731.6     .05       0    3818     .08       0  3968.4     .05       0
  4437.8      .1       0    4997     .07       0    5003      .1       0
  5127.5     .05       0
Bank Sta=4980.7,5020.8
XS Rating Curve= 0 ,0
Exp/Cntr=0.3,0.1

Type RM Length L Ch R = 1 ,13048   ,513,513,513
BEGIN DESCRIPTION:
UNT023 IN SPCR 15.0
END DESCRIPTION:
XS GIS Cut Line= 3
      2249179.19     13277831.17      2249732.97     13277577.35
      2251200.47     13277531.21
#Sta/Elev= 30
    3847   202.1  3849.6     202  4014.6  193.54    4157  187.16  4217.2  184.99
  4344.9  180.94  4346.1  180.93  4552.5   179.1  4650.9  178.88  4721.1  178.54
  4811.1  180.12  4901.1  179.28  4941.2   177.1  4961.2  173.36  4981.2  167.67
    4997   165.3  4999.8   164.8    5003   165.3  5031.2  172.68  5041.2   177.8
  5061.2  179.38  5291.3  178.18  5431.4  179.22  5491.4  180.97  5571.5  185.54
  5591.5  185.13  5681.5  190.98  5691.5  192.69  5711.5  192.44  5924.4  207.23
#Mann= 11 ,-1 , 0
    3847     .05       0  3849.6     .08       0  4014.6     .05       0
    4157      .1       0  4217.2     .05       0  4344.9      .1       0
  4346.1     .05       0  4552.5      .1       0  4650.9     .05       0
    4997     .03       0    5003     .05       0
Bank Sta=4961.2,5031.2
XS Rating Curve= 0 ,0
Exp/Cntr=0.3,0.1

Type RM Length L Ch R = 1 ,12535   ,623,623,623
BEGIN DESCRIPTION:
UNT023 IN SPCR 14.0
END DESCRIPTION:
XS GIS Cut Line= 2
      2249617.61     13278029.61      2251004.65     13278103.34
#Sta/Elev= 30
  4282.9  188.99  4503.3  182.66  4673.6  176.97  4713.6  174.62  4763.7   174.8
  4795.5  176.18  4813.8  177.12  4886.3  177.88  4943.9  177.34    4954  176.66
    4974  172.76    4984  169.83    4997  167.95  4999.8  167.45    5003  167.95
  5034.1     170  5054.1  173.28    5079  173.51  5124.2  175.97  5224.3  176.65
  5344.5   180.1  5457.6  185.39  5514.8  190.12  5534.8  189.74  5564.8  193.26
  5584.9  192.94  5624.9  195.61    5642  198.34    5665  197.48  5671.9  198.49
#Mann= 5 ,-1 , 0
  4282.9     .05       0  4795.5     .08       0  4886.3     .05       0
    4997     .03       0    5003     .05       0
Bank Sta=4974,5054.1
XS Rating Curve= 0 ,0
Exp/Cntr=0.3,0.1

Type RM Length L Ch R = 1 ,11912   ,268,268,268
BEGIN DESCRIPTION:
UNT023 IN SPCR 13.0
END DESCRIPTION:
XS GIS Cut Line= 3
      2249487.76     13278296.87      2250287.72     13278696.85
      2250687.73     13278696.85
#Sta/Elev= 30
  4132.8  192.15  4141.1  190.76  4297.7  182.65  4356.4  178.64  4504.5  173.18
  4633.1  176.03  4750.5  174.07  4929.4  175.04  4951.7  172.91  4974.1  168.59
    4997   165.1  4999.8   164.6    5003   165.1  5029.7  166.99  5037.2   168.9
  5087.2  170.34  5137.2  170.46  5167.2  171.84  5187.2  174.37  5197.2  176.96
  5207.2  177.75  5217.2  180.11  5227.2  184.34    5263  187.02  5307.2  190.91
  5317.2  190.48  5357.2  192.65  5367.2  194.06  5387.2  193.75  5427.2  196.12
#Mann= 4 ,-1 , 0
  4132.8     .05       0    4997     .04       0    5003     .05       0
    5263      .1       0
Bank Sta=4974.1,5037.2
XS Rating Curve= 0 ,0
Exp/Cntr=0.3,0.1

Type RM Length L Ch R = 1 ,11644   ,723,723,723
BEGIN DESCRIPTION:
UNT023 IN SPCR 12.0
END DESCRIPTION:
XS GIS Cut Line= 3
      2249114.62     13278878.73      2250554.41      13278961.8
       2250909.7      13278897.2
#Sta/Elev= 30
  3914.3  194.16  3965.5  192.73  3987.5   189.8  4017.6  190.89  4047.6  187.78
  4207.9  179.46  4408.2  171.39  4638.6  174.31  4828.9  173.14  4884.7  174.74
  4919.1  175.11  4959.1   167.1    4997   161.5  4999.8     161    5003   161.5
  5018.1   162.5  5059.3   164.6  5069.3  167.53  5200.5  175.94  5258.6  177.91
  5319.7  182.23  5339.8  181.26  5390.3  186.54  5420.8  186.86  5451.3  190.73
  5481.8  190.94  5520.6  195.16  5532.6  194.29  5584.2  197.69  5717.6  194.05
#Mann= 7 ,-1 , 0
  3914.3     .05       0  4884.7      .1       0    4997     .07       0
    5003      .1       0  5018.1     .05       0  5200.5      .1       0
  5258.6     .05       0
Bank Sta=4959.1,5069.3
XS Rating Curve= 0 ,0
Exp/Cntr=0.3,0.1

Type RM Length L Ch R = 1 ,10921   ,1239,1239,1239
BEGIN DESCRIPTION:
UNT023 IN SPCR 10.0
END DESCRIPTION:
XS GIS Cut Line= 3
      2248722.28     13279534.04      2250282.13     13279474.04
      2251638.93     13279824.78
#Sta/Elev= 30
    3214  200.76    3281  197.06  3379.4  193.13  3759.8  175.48  4140.1  169.83
  4363.1  172.43  4841.9  171.63  4887.7  168.79  4923.2  162.77  4928.3  164.34
  4935.7   161.8    4977  161.84    4997  157.77  4999.8  157.27    5003  157.77
  5004.4  159.38  5018.3  158.81    5039  165.74  5045.1  172.32  5428.6  175.22
  5514.1  181.05  5534.8  181.06  5543.1  178.88    5563  176.76  5637.6  179.62
    5669  183.34  5690.1  182.41    5761  189.04  6030.6  205.16  6176.4  205.53
#Mann= 9 ,-1 , 0
    3214     .05       0    3281     .08       0  3379.4     .05       0
  4363.1      .1       0    4997     .07       0    5003      .1       0
  5428.6     .05       0  5543.1      .1       0  5637.6     .05       0
#XS Ineff= 1 ,-1
 5482.81 5693.36  180.82
Permanent Ineff=
       F
Bank Sta=4928.3,5039
XS Rating Curve= 0 ,0
Exp/Cntr=0.3,0.1

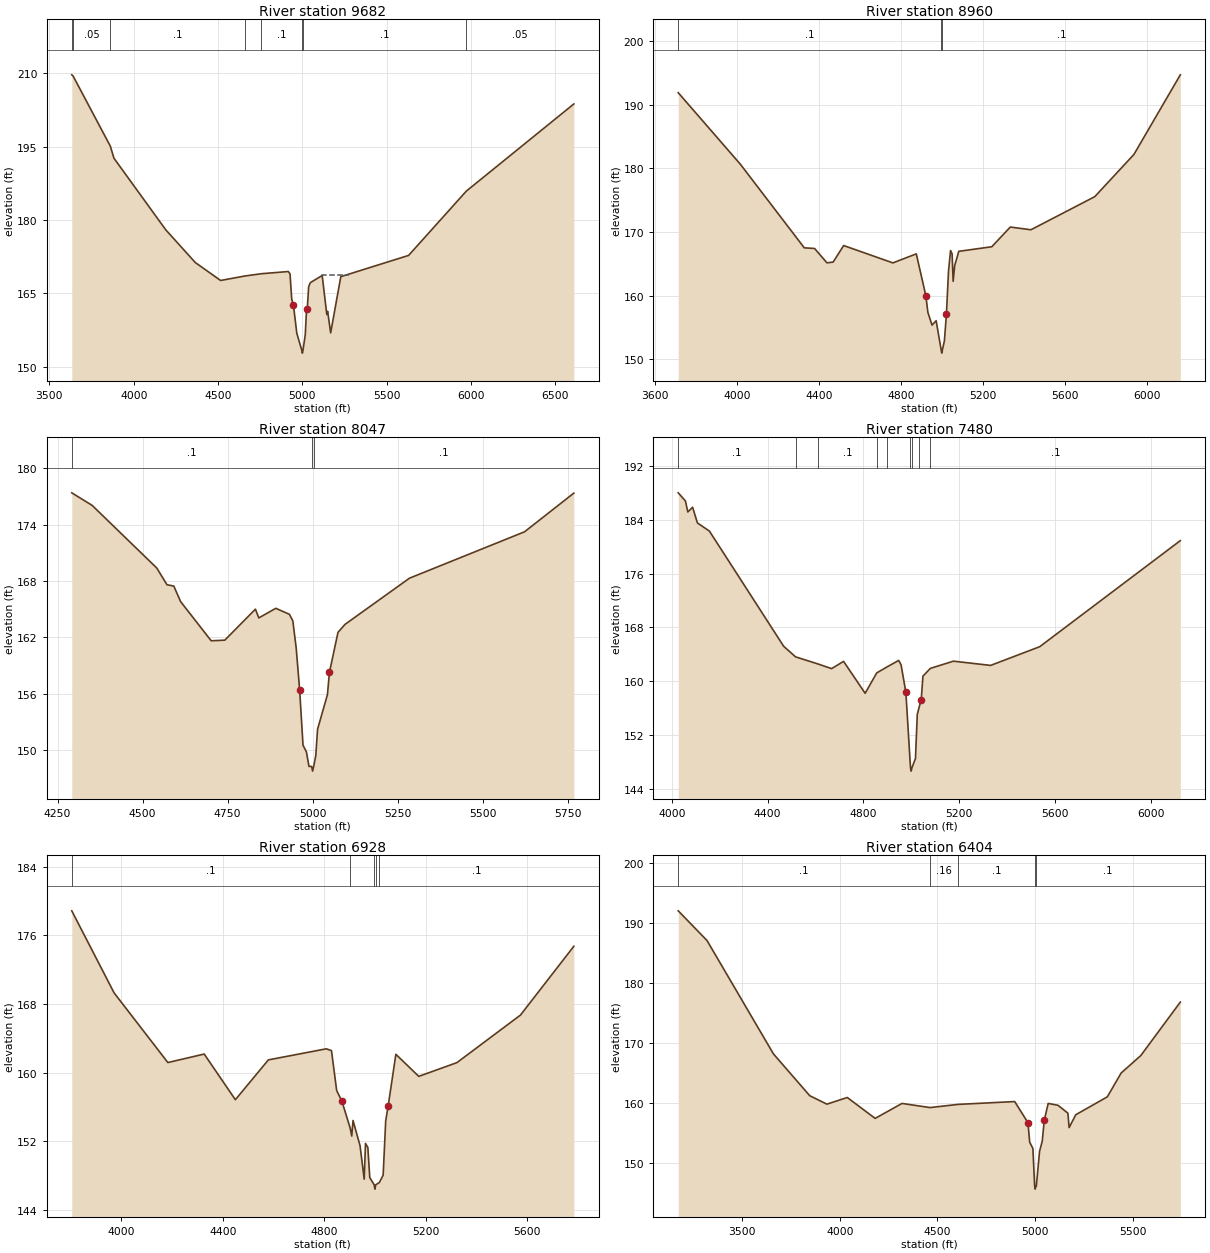
Type RM Length L Ch R = 1 ,9682    ,722,722,722
BEGIN DESCRIPTION:
Mapping XS 0a05f36d
END DESCRIPTION:
XS GIS Cut Line= 2
      2248828.43     13280258.56      2251794.28     13280009.49
#Sta/Elev= 30
  3632.7  209.66  3640.4  209.43  3861.1   195.1  3882.9  192.62  4189.9     178
  4364.6  171.33  4515.1  167.65  4658.1  168.56  4756.9  169.03  4916.5  169.48
  4926.5  168.99  4936.6  163.83  4946.6  162.65  4966.7  156.87    4997  153.31
  4999.8  152.81    5003  153.31  5016.9  156.54  5024.6  161.83  5029.6  162.28
  5036.9  166.37    5047  167.21  5117.2  168.67  5144.5   160.7  5149.6  161.35
  5167.4  156.95  5227.6  168.43  5629.4  172.77  5971.8  185.91    6609  203.71
#Mann= 8 ,-1 , 0
  3632.7      .1       0  3640.4     .05       0  3861.1      .1       0
  4658.1     .16       0  4756.9      .1       0    4997     .07       0
    5003      .1       0  5971.8     .05       0
#XS Ineff= 1 ,-1
 5116.02 5274.61  168.71
Permanent Ineff=
       F
Bank Sta=4946.6,5024.6
XS Rating Curve= 0 ,0
Exp/Cntr=0.3,0.1

Type RM Length L Ch R = 1 ,8960    ,913,913,913
BEGIN DESCRIPTION:
UNT023 IN SPCR 8.0
END DESCRIPTION:
XS GIS Cut Line= 2
      2249225.91     13280911.84      2251662.81     13280637.41
#Sta/Elev= 30
  3712.7  191.91  4016.4  180.65  4328.4  167.51  4378.7  167.41  4439.1  165.15
  4469.3  165.27  4520.7  167.87  4761.1  165.14  4875.5  166.56  4922.1  159.98
  4932.2  157.34  4952.3  155.36  4972.4  156.05    4997  151.45  4999.8  150.95
    5003  151.45  5012.7  152.87  5022.7  157.12  5032.8  163.84  5042.9  167.09
  5050.4  166.56  5055.5  162.24    5063  164.73  5083.1  166.96  5244.1  167.68
  5334.7  170.78  5435.3  170.35  5747.3  175.56  5938.5   182.2    6165  194.72
#Mann= 3 ,-1 , 0
  3712.7      .1       0    4997     .07       0    5003      .1       0
Bank Sta=4922.1,5022.7
XS Rating Curve= 0 ,0
Exp/Cntr=0.3,0.1

Type RM Length L Ch R = 1 ,8047    ,567,567,567
BEGIN DESCRIPTION:
UNT023 IN SPCR 7.0
END DESCRIPTION:
XS GIS Cut Line= 3
      2249787.68     13281496.85      2250487.72     13281496.85
      2251237.77     13281296.84
#Sta/Elev= 30
  4291.7  177.39  4351.7  176.05  4541.7  169.38  4571.7   167.6  4591.7  167.46
  4611.7  165.81  4701.7  161.63  4741.7   161.7  4831.7     165  4841.7  164.07
  4891.7  165.09  4931.7  164.45  4941.7  163.75  4951.7  160.83  4961.7  156.42
  4971.7   150.5  4981.7   149.8  4989.2  148.25    4997  148.25  4999.8  147.75
    5003  148.25  5009.2   149.4  5014.4   152.2  5043.5   155.9  5049.3  158.26
  5074.5  162.53  5095.2  163.38  5284.8   168.3  5623.1  173.24    5768  177.36
#Mann= 3 ,-1 , 0
  4291.7      .1       0    4997     .07       0    5003      .1       0
Bank Sta=4961.7,5049.3
XS Rating Curve= 0 ,0
Exp/Cntr=0.3,0.1

Type RM Length L Ch R = 1 ,7480    ,552,552,552
BEGIN DESCRIPTION:
UNT023 IN SPCR 6.0
END DESCRIPTION:
XS GIS Cut Line= 3
      2249587.69     13282096.86      2250587.72     13282046.85
      2251387.74     13281296.83
#Sta/Elev= 30
  4026.5     188  4056.6  186.79  4066.6  185.16  4086.6  185.86  4106.6  183.53
  4156.7  182.32  4467.1  165.21  4516.8  163.64  4611.7  162.57  4667.3  161.89
  4717.4  162.97  4807.5  158.23  4855.8  161.25  4900.1  162.17  4947.7  163.11
  4957.7  162.45  4977.7  158.37    4997  147.17  4999.8  146.67    5003  147.17
  5017.8  148.54  5025.3  155.08  5034.6  156.36  5041.7  157.22    5049  160.78
  5080.1  161.93  5176.5     163  5331.9  162.37    5537  165.15  6124.4   180.9
#Mann= 9 ,-1 , 0
  4026.5      .1       0  4516.8     .16       0  4611.7      .1       0
  4855.8     .16       0  4900.1      .1       0    4997     .07       0
    5003      .1       0  5034.6     .16       0  5080.1      .1       0
Bank Sta=4977.7,5041.7
XS Rating Curve= 0 ,0
Exp/Cntr=0.3,0.1

Type RM Length L Ch R = 1 ,6928    ,524,524,524
BEGIN DESCRIPTION:
UNT023 IN SPCR 5.0
END DESCRIPTION:
XS GIS Cut Line= 3
      2249737.69     13282196.85      2250887.72     13282446.85
      2251687.67     13282496.85
#Sta/Elev= 30
  3805.3  178.84  3972.1  169.28    4184  161.16  4327.2  162.15    4450  156.83
    4580  161.47  4808.2  162.76  4828.7  162.55  4849.2  157.89  4869.6  156.67
  4902.5  153.51  4908.5   152.6  4913.6  154.41  4941.3  151.47  4957.6  147.57
  4962.7  151.74    4972  151.26  4979.6  147.75    4997  146.91  4999.8  146.41
    5003  146.91  5017.3  147.18  5032.3  148.03  5042.3  154.35  5052.3  156.15
  5082.4  162.12  5172.6  159.55  5322.9  161.15  5573.3  166.69  5783.7  174.71
#Mann= 5 ,-1 , 0
  3805.3      .1       0  4902.5     .16       0    4997     .07       0
    5003     .16       0  5017.3      .1       0
Bank Sta=4869.6,5052.3
XS Rating Curve= 0 ,0
Exp/Cntr=0.3,0.1

Type RM Length L Ch R = 1 ,6404    ,1031,1031,1031
BEGIN DESCRIPTION:
UNT023 IN SPCR 4.0
END DESCRIPTION:
XS GIS Cut Line= 3
      2249437.74     13282096.86      2251037.72     13282946.85
      2251787.73     13282846.85
#Sta/Elev= 30
  3173.8  191.97    3321  187.03  3660.7  168.17  3846.4  161.21  3934.3   159.8
  4038.5  160.91  4181.1  157.43  4318.6  159.92  4462.2  159.23  4605.7  159.76
  4895.1  160.23  4962.9  156.71  4971.7  153.47  4988.1  152.42    4997  146.16
  4999.8  145.66    5003  146.16  5005.7  146.16  5022.1  151.94    5036  153.66
  5046.1  157.09  5066.3  159.92  5116.7  159.61  5167.1   158.3  5173.4   155.9
  5207.5  158.04  5368.9  161.02  5439.5  164.98  5540.4   167.9  5742.2  176.78
#Mann= 5 ,-1 , 0
  3173.8      .1       0  4462.2     .16       0  4605.7      .1       0
    4997     .07       0    5003      .1       0
Bank Sta=4962.9,5046.1
XS Rating Curve= 0 ,0
Exp/Cntr=0.3,0.1