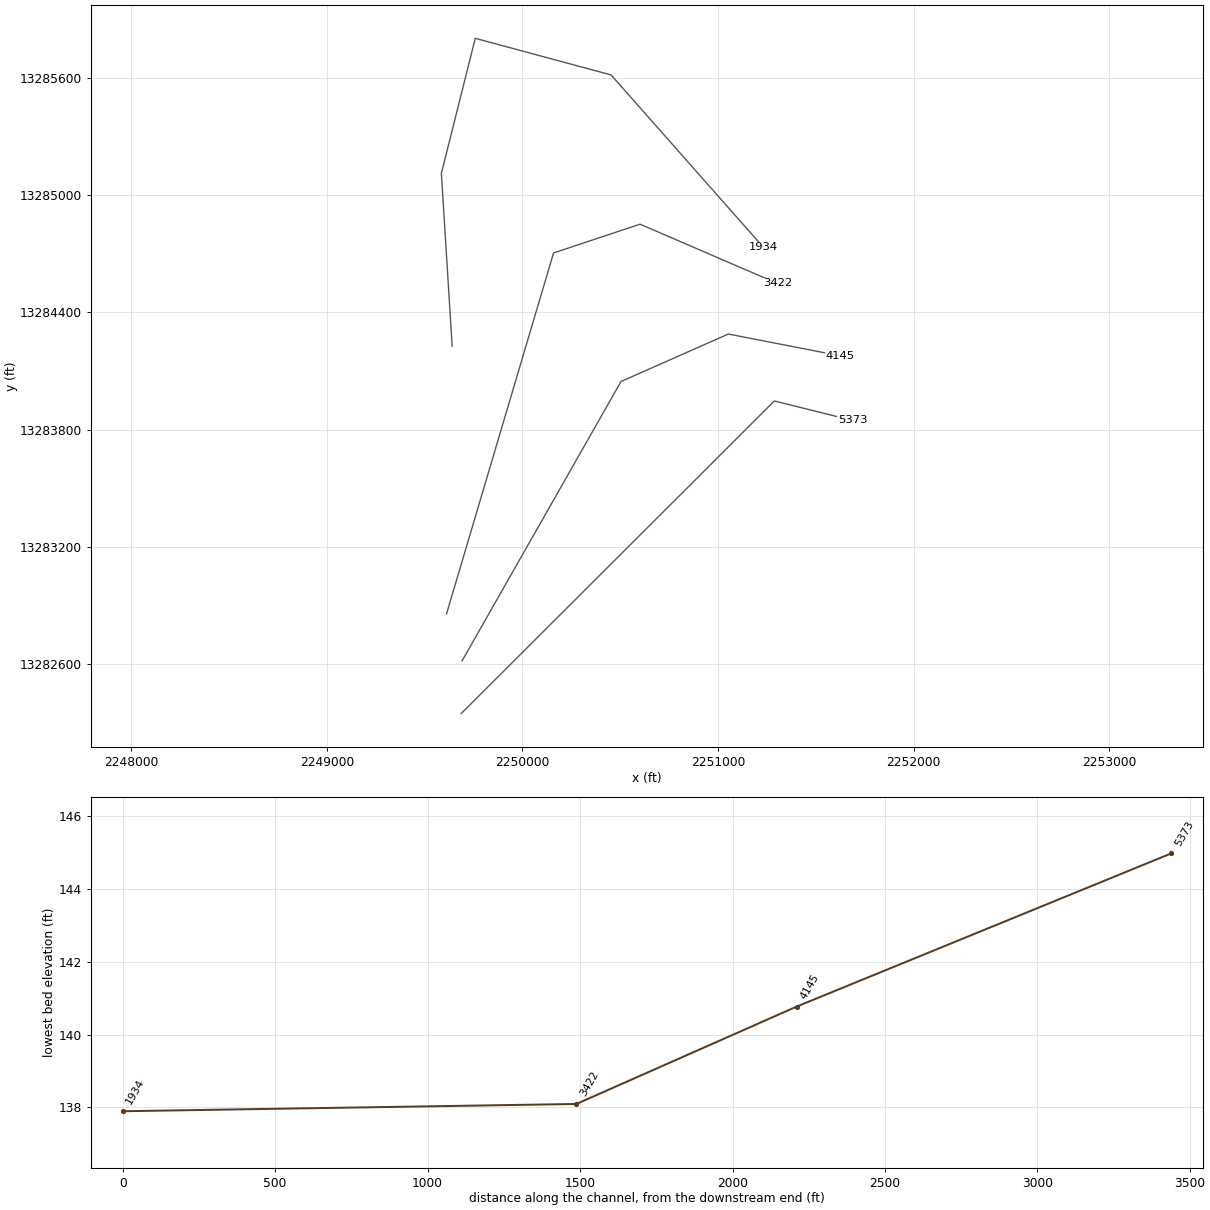
HEC-RAS study UNT023 IN SPCR.prj: UNT023 IN SPCR Base Level Engineering

--- UNT023 IN SPCR.g01 (geometry) --- (continued)

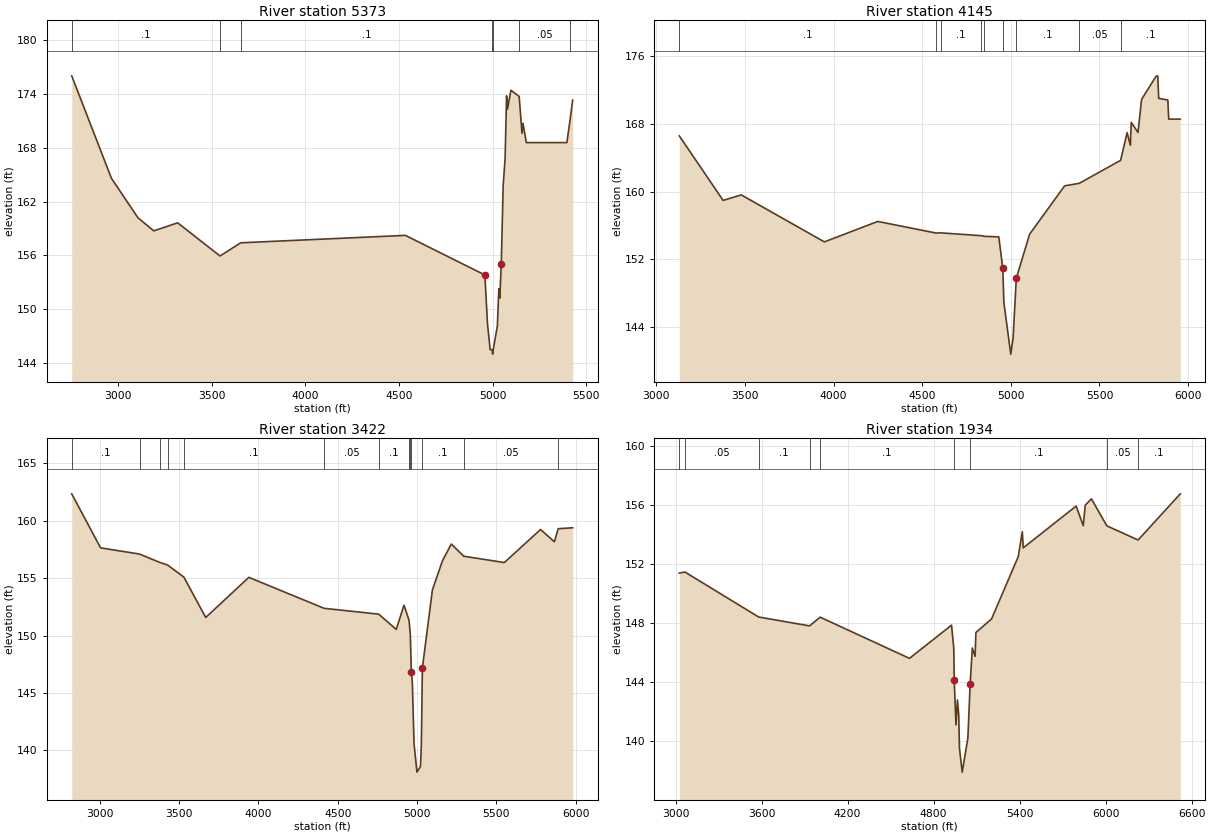
Type RM Length L Ch R = 1 ,5373    ,1228,1228,1228
BEGIN DESCRIPTION:
UNT023 IN SPCR 3.0
END DESCRIPTION:
XS GIS Cut Line= 3
      2249687.72     13282346.86      2251287.72     13283946.85
      2251687.68     13283846.87
#Sta/Elev= 30
  2752.2  176.03  2964.3   164.6  3105.7   160.2  3190.6  158.73  3317.9  159.63
  3544.3  155.93  3654.8   157.4  4534.1  158.23  4958.4  153.81  4972.5  148.35
  4986.7  145.48    4997  145.48  4999.8  144.98    5003  145.48  5025.2  148.13
    5033  152.28  5038.1  151.24  5045.9  154.99  5056.2  163.79  5066.5  166.84
  5074.2   173.8  5079.4  172.32  5097.4  174.42  5141.5  173.73  5156.7  169.62
  5161.8  170.73  5179.9  168.58  5396.3  168.58  5414.1  171.22  5427.2  173.32
#Mann= 7 ,-1 , 0
  2752.2      .1       0  3544.3     .16       0  3654.8      .1       0
    4997     .07       0    5003      .1       0  5141.5     .05       0
  5414.1      .1       0
Bank Sta=4958.4,5045.9
XS Rating Curve= 0 ,0
Exp/Cntr=0.3,0.1

Type RM Length L Ch R = 1 ,4145    ,723,723,723
BEGIN DESCRIPTION:
UNT023 IN SPCR 2.0
END DESCRIPTION:
XS GIS Cut Line= 4
      2249691.38     13282615.96      2250503.88     13284046.52
      2251052.49     13284289.57      2251621.91     13284178.46
#Sta/Elev= 30
  3130.5  166.59  3377.5  158.96  3479.9  159.61  3948.5  154.05  4249.9  156.47
  4577.6   155.1  4603.7  155.12  4830.9  154.79  4849.3  154.71  4932.3  154.64
  4954.9  150.91    4961  146.87  4999.8  140.77  5013.1  142.71  5030.9  149.74
  5106.2  154.96  5303.4  160.68  5386.2  160.98  5619.3   163.7  5656.2  166.98
  5674.3  165.49  5679.4  168.19  5717.3     167  5737.7  170.91  5819.2  173.65
    5829   173.7  5834.1  171.04  5885.7  170.83  5890.8  168.58  5955.9  168.58
#Mann= 9 ,-1 , 0
  3130.5      .1       0  4577.6     .16       0  4603.7      .1       0
  4830.9     .16       0  4849.3      .1       0  4954.9     .07       0
  5030.9      .1       0  5386.2     .05       0  5619.3      .1       0
Bank Sta=4954.9,5030.9
XS Rating Curve= 0 ,0
Exp/Cntr=0.3,0.1

Type RM Length L Ch R = 1 ,3422    ,1488,1488,1488
BEGIN DESCRIPTION:
Mapping XS 6e1cbf27
END DESCRIPTION:
XS GIS Cut Line= 4
      2249611.53     13282855.57      2250158.93     13284704.83
       2250601.1     13284852.07      2251303.51     13284548.56
#Sta/Elev= 30
  2822.1  162.35  3004.2  157.64  3249.8   157.1    3378  156.37  3427.6  156.14
  3529.5  155.09  3667.4  151.57  3939.3  155.07    4414  152.37  4758.9  151.86
  4869.2  150.53    4918  152.64  4949.6  151.35  4957.8  150.12  4964.1  146.83
  4970.7  145.89  4981.3  140.58  4999.8  138.09  5022.1  138.59  5027.4  140.43
    5034  147.17  5097.2  153.97  5160.5  156.51  5216.4  157.97  5295.1  156.91
  5550.7  156.36  5779.5  159.24  5866.7  158.17  5890.7  159.31  5981.9  159.39
#Mann= 13 ,-1 , 0
  2822.1      .1       0  3249.8     .16       0    3378      .1       0
  3427.6     .16       0  3529.5      .1       0    4414     .05       0
  4758.9      .1       0  4949.6     .16       0  4957.8      .1       0
  4964.1     .07       0    5034      .1       0  5295.1     .05       0
  5890.7      .1       0
Bank Sta=4964.1,5034
XS Rating Curve= 0 ,0
Exp/Cntr=0.3,0.1

Type RM Length L Ch R = 1 ,1934    ,0,0,0
BEGIN DESCRIPTION:
UNT023 IN SPCR 1.0
END DESCRIPTION:
XS GIS Cut Line= 5
      2249640.61     13284227.53      2249585.48     13285112.49
      2249758.67     13285803.92      2250453.11     13285616.42
      2251230.89     13284734.47
#Sta/Elev= 30
  3026.4  151.38  3065.4  151.45  3580.4   148.4  3934.6   147.8  4008.8  148.39
  4631.9   145.6  4925.3  147.85  4940.8  146.32 4944.28  144.11  4956.3  141.09
  4966.7  142.78  4975.5  141.77  4980.7  139.51  4999.8  137.89  5039.2  140.19
  5055.3  143.88  5070.3   146.3    5090  145.74  5095.2  147.35  5204.5  148.27
  5390.6  152.49  5419.1  154.18  5425.7  153.09  5794.7  155.92  5844.1  154.59
  5858.3  155.98    5901  156.41  6008.8  154.58  6226.9  153.62  6521.1  156.75
#Mann= 9 ,-1 , 0
  3026.4      .1       0  3065.4     .05       0  3580.4      .1       0
  3934.6     .05       0  4008.8      .1       0 4944.28     .07       0
  5055.3      .1       0  6008.8     .05       0  6226.9      .1       0
Bank Sta=4944.28,5055.3
XS Rating Curve= 0 ,0
Exp/Cntr=0.3,0.1

Chan Stop Cuts=-1
Use User Specified Reach Order=0
Composite Channel Slope=5