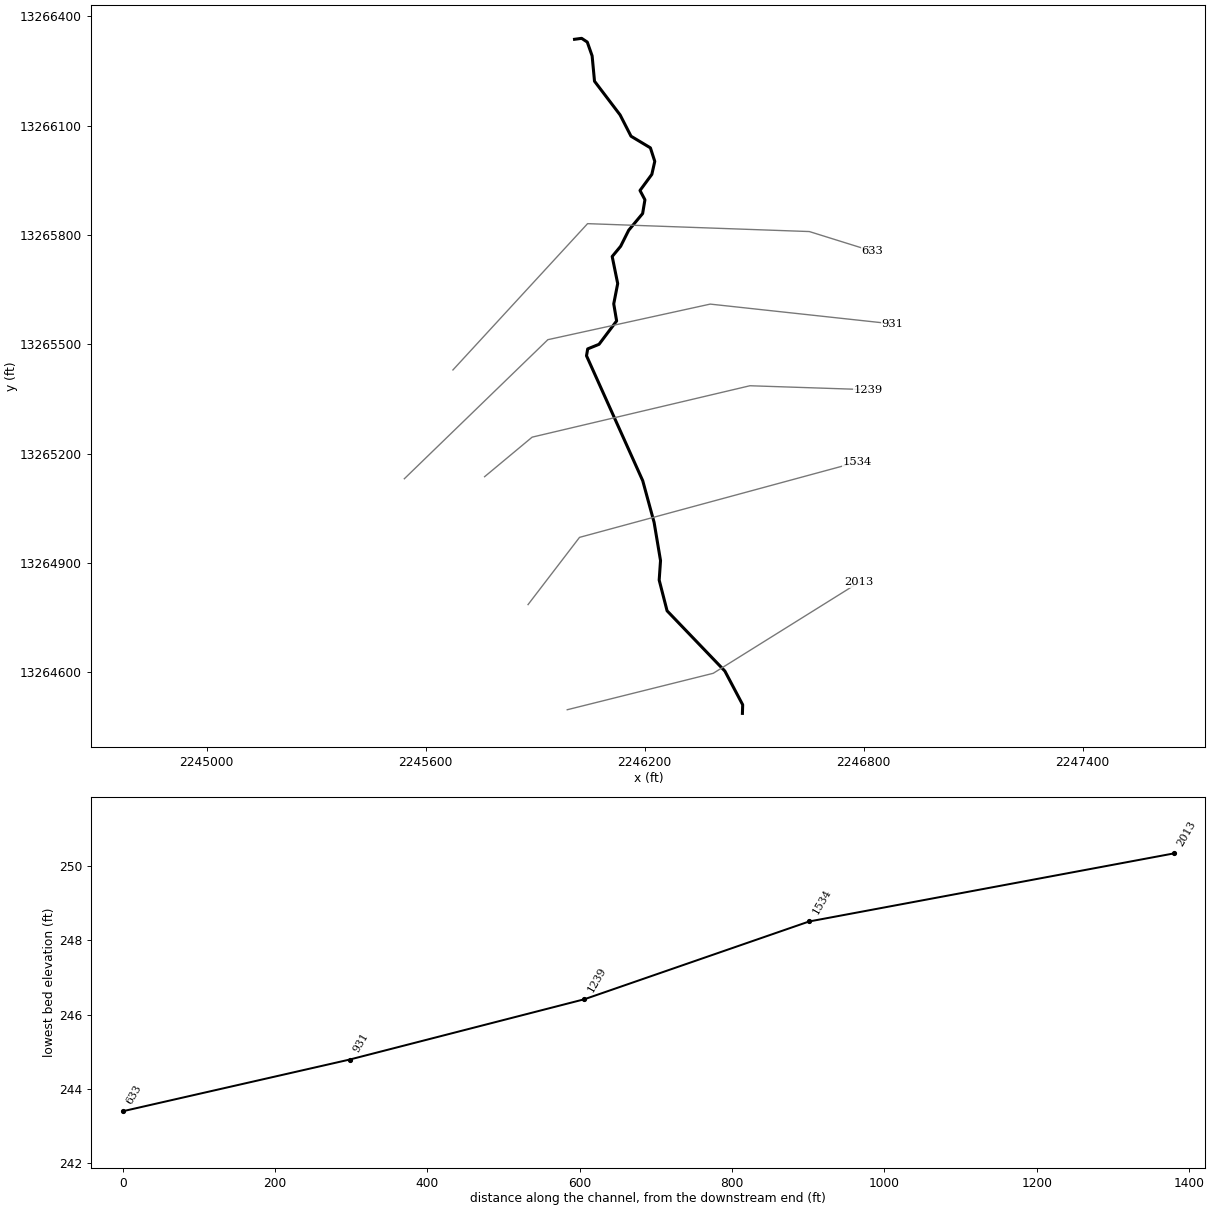
--- UNT024 IN SPCR.prj (project) ---

Proj Title=UNT024 IN SPCR Base Level Engineering
Current Plan=p01
Default Exp/Contr=0.3,0.1
English Units
Geom File=g01
Flow File=f01
Plan File=p01
BEGIN DESCRIPTION:
UNT024 IN SPCR
END DESCRIPTION:

--- UNT024 IN SPCR.p01 (plan) ---

Plan Title=Multiple Run
Short Identifier=Multiple
Geom File=g01
Flow File=f01
Subcritical Flow
K Sum by GR= 0
Std Step Tol= 0.01
Critical Tol= 0.01
Num of Std Step Trials= 20
Max Error Tol= 0.3
Flow Tol Ratio= 0.001
Split Flow NTrial= 30
Split Flow Tol= 0.02
Split Flow Ratio= 0.02
Log Output Level= 0
Friction Slope Method= 1
Unsteady Friction Slope Method= 2
Unsteady Bridges Friction Slope Method= 1
Parabolic Critical Depth
Global Vel Dist=  1 , 1 , 1
Global Log Level= 0
CheckData=True
Encroach Param= -1, 0, 0, 0
BEGIN DESCRIPTION:
Multiple Run
END DESCRIPTION:

--- UNT024 IN SPCR.f01 (steady flow) ---

Flow Title=Multiple
Number of Profiles=7
Profile Names=10-year,25-year,50-year,1pct_min,100-year,1pct_plu,500-year
River Rch & RM= UNT024 IN SPCR,Reach-1,2013
     327     467     587     543     735     994    1168
Boundary for River Rch & Prof#=UNT024 IN SPCR,Reach-1,1
Up Type=0
Dn Type=3
Dn Slope=0.005
Boundary for River Rch & Prof#=UNT024 IN SPCR,Reach-1,2
Up Type=0
Dn Type=3
Dn Slope=0.005
Boundary for River Rch & Prof#=UNT024 IN SPCR,Reach-1,3
Up Type=0
Dn Type=3
Dn Slope=0.005
Boundary for River Rch & Prof#=UNT024 IN SPCR,Reach-1,4
Up Type=0
Dn Type=3
Dn Slope=0.005
Boundary for River Rch & Prof#=UNT024 IN SPCR,Reach-1,5
Up Type=0
Dn Type=3
Dn Slope=0.005
Boundary for River Rch & Prof#=UNT024 IN SPCR,Reach-1,6
Up Type=0
Dn Type=3
Dn Slope=0.005
Boundary for River Rch & Prof#=UNT024 IN SPCR,Reach-1,7
Up Type=0
Dn Type=3
Dn Slope=0.005

--- UNT024 IN SPCR.g01 (geometry) ---

Geom Title=Existing Conditions

River Reach=UNT024 IN SPCR,Reach-1
Reach XY= 30
      2246467.72     13264486.86      2246468.45     13264510.47
      2246419.65     13264602.99      2246261.29     13264768.34
      2246239.64     13264852.69      2246243.34     13264906.13
      2246225.74     13265011.02      2246194.52     13265125.53
      2246040.53     13265468.23      2246043.75     13265487.15
      2246074.86     13265499.79      2246123.02     13265563.90
      2246115.13     13265610.74      2246125.97     13265666.48
      2246110.88     13265740.74      2246134.09     13265768.84
      2246156.09     13265812.78      2246194.28     13265858.62
      2246200.61     13265896.34      2246187.08     13265921.90
      2246219.53     13265966.14      2246227.58     13266001.84
      2246215.59     13266038.97      2246162.45     13266070.90
      2246132.55     13266129.36      2246062.46     13266221.79
      2246055.88     13266291.42      2246042.62     13266329.24
      2246027.16     13266339.50      2246007.72     13266336.85

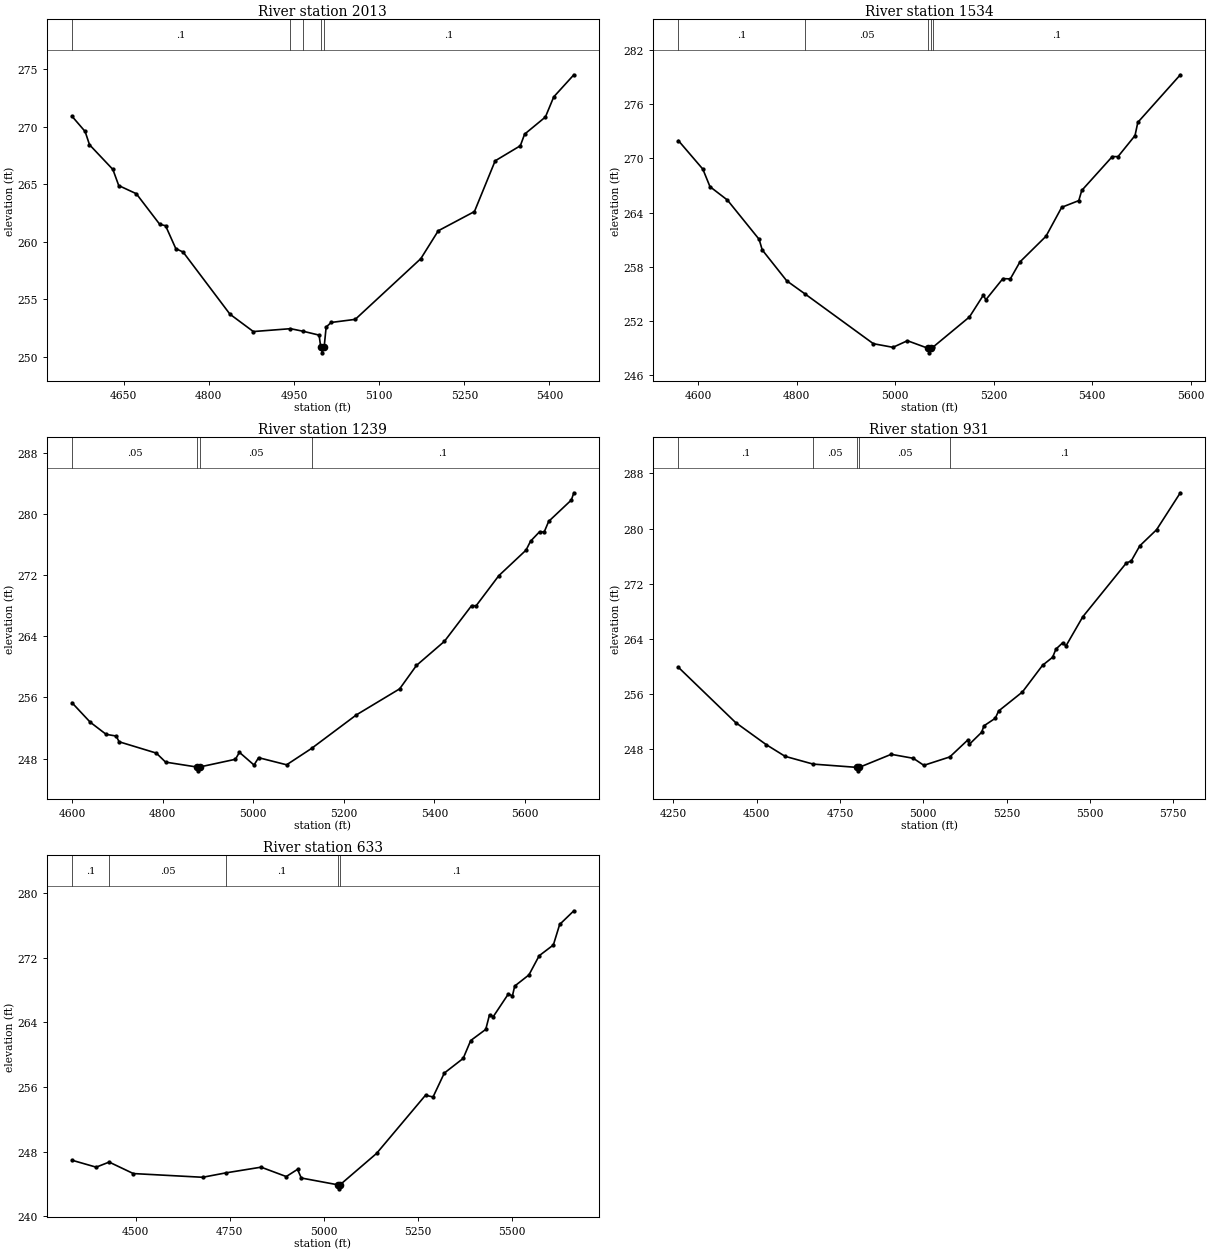
Type RM Length L Ch R = 1,2013,479,479,479
BEGIN DESCRIPTION:
UNT024 IN SPCR 3.0
END DESCRIPTION:
XS GIS Cut Line= 3
      2245987.74     13264496.86      2246387.72     13264596.85
      2246787.73     13264846.86
#Sta/Elev= 30
  4558.9  270.90  4582.1  269.57  4589.8  268.42  4631.0  266.27  4641.3  264.87
  4672.3  264.16  4713.5  261.50  4723.8  261.38  4741.8  259.39  4754.7  259.09
  4837.2  253.69  4878.4  252.18  4943.8  252.43  4966.6  252.20  4994.2  251.87
  4997.1  250.83  4999.8  250.33  5003.1  250.83  5006.6  252.57  5015.4  252.97
  5057.9  253.24  5173.4  258.52  5204.1  260.94  5267.8  262.61  5304.3  267.02
  5348.6  268.33  5356.2  269.34  5392.8  270.83  5407.5  272.58  5442.9  274.50
#Mann=5,-1,0
  4558.9     0.1       0  4943.8    0.05       0  4966.6     0.1       0
  4997.1    0.07       0  5003.1     0.1       0
Bank Sta=4997.1,5003.1
Exp/Cntr=0.3,0.1

Type RM Length L Ch R = 1,1534,295,295,295
BEGIN DESCRIPTION:
Mapping XS 63e3ece1
END DESCRIPTION:
XS GIS Cut Line= 3
      2245880.33     13264785.43      2246021.40     13264969.92
      2246780.97     13265176.09
#Sta/Elev= 30
  4559.8  271.96  4609.4  268.81  4623.9  266.87  4659.3  265.39  4723.7  261.05
  4730.0  259.88  4779.8  256.46  4817.5  254.99  4955.7  249.51  4995.5  249.11
  5024.9  249.84  5066.9  249.00  5069.7  248.50  5072.9  249.00  5076.8  249.13
  5150.9  252.47  5179.0  254.87  5184.2  254.37  5218.8  256.71  5233.8  256.67
  5253.4  258.55  5306.3  261.39  5338.2  264.59  5372.9  265.33  5378.9  266.45
  5441.0  270.20  5452.5  270.19  5487.1  272.52  5492.8  273.98  5579.1  279.24
#Mann=5,-1,0
  4559.8     0.1       0  4817.5    0.05       0  5066.9    0.03       0
  5072.9    0.05       0  5076.8     0.1       0
Bank Sta=5066.9,5072.9
Exp/Cntr=0.3,0.1

Type RM Length L Ch R = 1,1239,308,308,308
BEGIN DESCRIPTION:
UNT024 IN SPCR 2.0
END DESCRIPTION:
XS GIS Cut Line= 4
      2245761.30     13265136.43      2245891.55     13265244.97
      2246488.34     13265386.03      2246813.28     13265375.20
#Sta/Elev= 30
  4599.8  255.32  4640.1  252.77  4675.3  251.18  4697.4  250.96  4703.9  250.21
  4786.0  248.73  4806.5  247.55  4875.4  246.91  4878.2  246.41  4881.4  246.91
  4960.6  247.92  4969.5  248.83  5001.7  247.17  5011.8  248.13  5073.7  247.20
  5128.7  249.34  5227.8  253.73  5323.2  257.13  5360.3  260.19  5422.0  263.34
  5482.0  268.01  5492.0  267.99  5542.0  271.92  5602.1  275.26  5612.1  276.43
  5632.1  277.67  5642.1  277.62  5652.1  279.02  5702.1  281.81  5707.7  282.76
#Mann=4,-1,0
  4599.8    0.05       0  4875.4    0.03       0  4881.4    0.05       0
  5128.7     0.1       0
Bank Sta=4875.4,4881.4
Exp/Cntr=0.3,0.1

Type RM Length L Ch R = 1,931,298,298,298
BEGIN DESCRIPTION:
Mapping XS af2244af
END DESCRIPTION:
XS GIS Cut Line= 4
      2245541.37     13265130.81      2245934.60     13265512.46
      2246379.48     13265610.11      2246878.59     13265555.86
#Sta/Elev= 30
  4265.4  259.83  4436.9  251.81  4528.7  248.60  4585.3  246.90  4669.4  245.77
  4801.5  245.29  4804.2  244.79  4807.5  245.29  4903.7  247.19  4970.1  246.61
  5001.6  245.59  5079.4  246.81  5132.9  249.25  5138.1  248.65  5174.9  250.39
  5181.9  251.33  5215.9  252.43  5225.7  253.48  5297.3  256.25  5357.6  260.12
  5387.8  261.29  5397.8  262.48  5418.0  263.39  5428.0  262.95  5478.3  267.17
  5609.1  275.00  5623.5  275.27  5649.3  277.48  5699.6  279.82  5770.9  285.19
#Mann=5,-1,0
  4265.4     0.1       0  4669.4    0.05       0  4801.5    0.03       0
  4807.5    0.05       0  5079.4     0.1       0
Bank Sta=4801.5,4807.5
Exp/Cntr=0.3,0.1

Type RM Length L Ch R = 1,633,0,0,0
BEGIN DESCRIPTION:
UNT024 IN SPCR 1.0
END DESCRIPTION:
XS GIS Cut Line= 4
      2245674.51     13265429.41      2246043.46     13265830.91
      2246651.10     13265809.21      2246823.67     13265755.28
#Sta/Elev= 30
  4330.6  246.94  4395.0  246.08  4429.5  246.71  4493.7  245.29  4678.0  244.83
  4739.2  245.37  4833.4  246.08  4900.2  244.92  4930.2  245.81  4940.2  244.74
  5037.2  243.90  5040.0  243.40  5043.2  243.90  5140.3  247.78  5270.4  254.98
  5290.4  254.76  5320.4  257.72  5370.5  259.53  5390.5  261.74  5430.5  263.12
  5440.5  264.93  5450.5  264.70  5490.8  267.52  5501.3  267.24  5507.5  268.48
  5545.3  269.86  5572.5  272.23  5610.2  273.56  5627.0  276.10  5664.7  277.79
#Mann=5,-1,0
  4330.6     0.1       0  4429.5    0.05       0  4739.2     0.1       0
  5037.2    0.07       0  5043.2     0.1       0
Bank Sta=5037.2,5043.2
Exp/Cntr=0.3,0.1

Chan Stop Cuts=-1