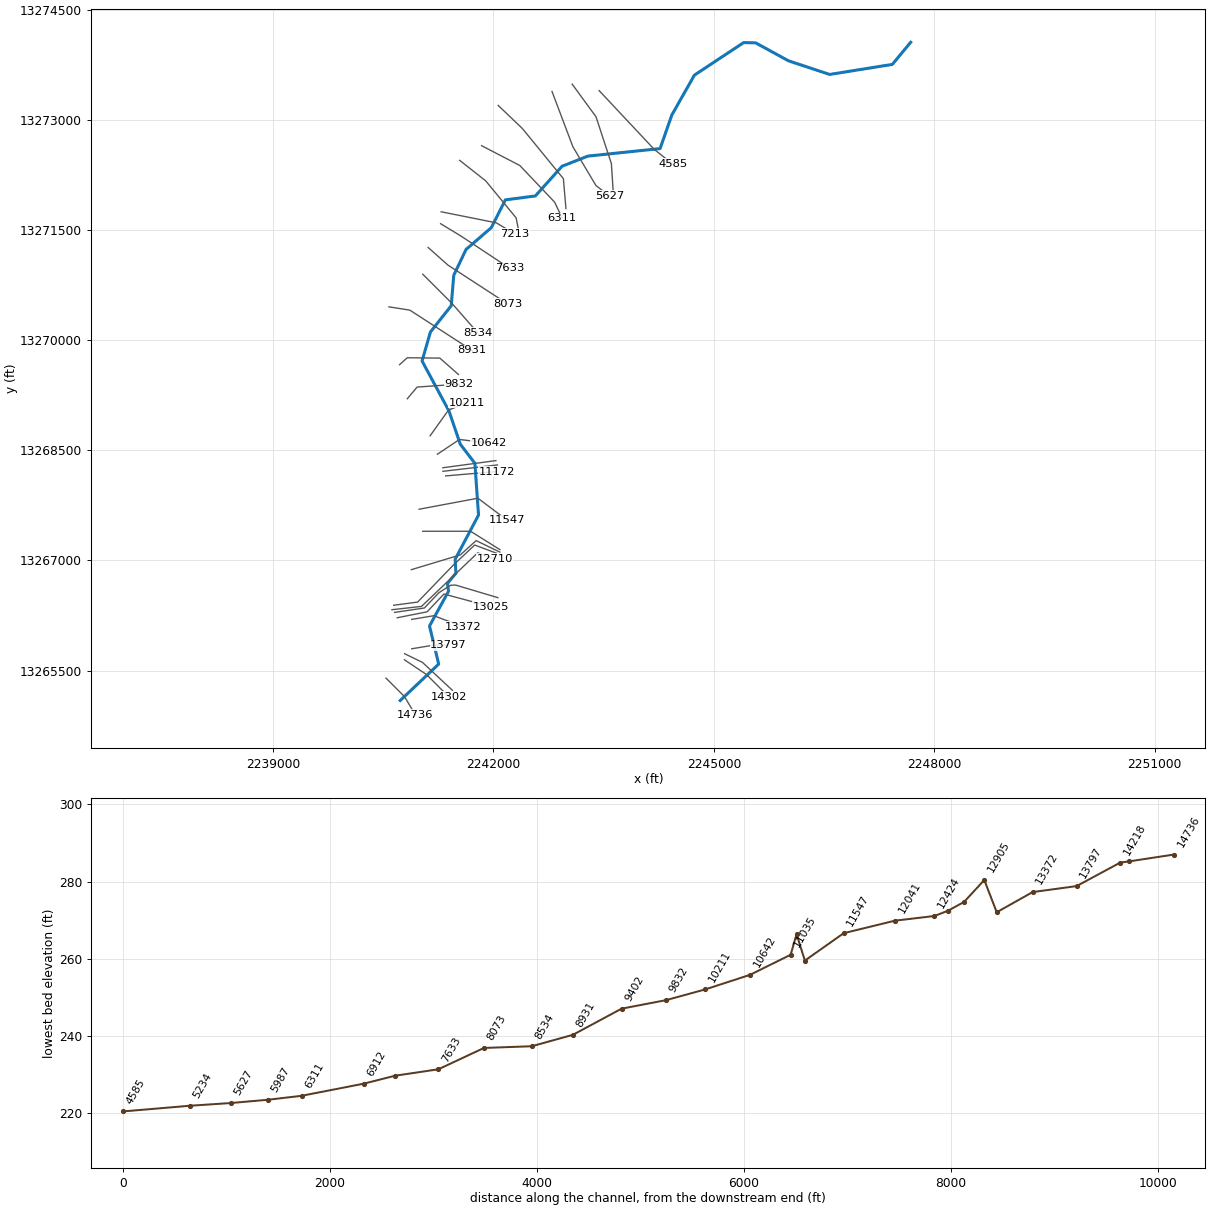
--- UNT025 IN SPCR.prj (project) ---

Proj Title=UNT025 IN SPCR Base Level Engineering
Current Plan=p01
Default Exp/Contr=0.3,0.1
English Units
Geom File=g01
Flow File=f01
Plan File=p01
Y Axis Title=Elevation
X Axis Title(PF)=Main Channel Distance
X Axis Title(XS)=Station
BEGIN DESCRIPTION:
UNT025 IN SPCR
END DESCRIPTION:
DSS File=dss
DSS Export Rating Curves= 0
DSS Export Rating Curve Sorted= 0
DSS Export Volume Flow Curves= 0
DXF OffsetX= 0
DXF OffsetY= 0
DXF ScaleX= 1
DXF ScaleY= 10

--- UNT025 IN SPCR.p01 (plan) ---

Plan Title=Multiple Run
Program Version=4.10
Short Identifier=Multiple Run
Geom File=g01
Flow File=f01
Subcritical Flow
K Sum by GR= 0
Std Step Tol= 0.01
Critical Tol= 0.01
Num of Std Step Trials= 20
Max Error Tol= 0.3
Flow Tol Ratio= 0.001
Split Flow NTrial= 30
Split Flow Tol= 0.02
Split Flow Ratio= 0.02
Log Output Level= 0
Friction Slope Method= 1
Unsteady Friction Slope Method= 2
Unsteady Bridges Friction Slope Method= 1
Parabolic Critical Depth
Global Vel Dist= 1 , 1 , 1
Global Log Level= 0
CheckData=True
Encroach Param=-1 ,0,0, 0
BEGIN DESCRIPTION:
Multiple Run
END DESCRIPTION:
Computation Interval=1HOUR
Output Interval=1HOUR
Run HTab= 1
Run UNet= 0
Run PostProcess= 0
Run WQNet= 0
UNET Theta= 1
UNET Theta Warmup= 1
UNET ZTol= 0.02
UNET ZSATol= 0.05
UNET MxIter= 20
UNET MaxInSteps= 0
UNET DtIC= 0
UNET DtMin= 0
UNET MaxCRTS= 20
UNET WFStab= 2
UNET SFStab= 1
UNET WFX= 1
UNET SFX= 1
UNET DSS MLevel= 4
UNET DZMax Abort= 100
UNET Convert EG Bridges= 0
UNET Use Existing IB Tables=-1
UNET Froude Reduction=False
UNET Froude Limit= 1
UNET Froude Power= 10
UNET Time Slicing=0,0, 5
UNET Junction Losses=0
Instantaneous Interval=1HOUR
DSS File=dss
Write IC File= 0
Write IC File at Sim End=0
Echo Input=False
Echo Parameters=False
Echo Output=False
Write Detailed= 0
WQ AD Non Conservative
WQ ULTIMATE=-1
WQ Max Comp Step=1HOUR
WQ Output Interval=15MIN
WQ Output Selected Increments= 0
WQ Output face flow=0
WQ Output face velocity=0
WQ Output face area=0
WQ Output face dispersion=0
WQ Output cell volume=0
WQ Output cell surface area=0
WQ Output cell continuity=0
WQ Output cumulative cell continuity=0
WQ Output face conc=0
WQ Output face dconc_dx=0
WQ Output face courant=0
WQ Output face peclet=0
WQ Output face adv mass=0
WQ Output face disp mass=0
WQ Output cell mass=0
WQ Output cell source sink temp=0
WQ Output cell source sink nsm=0
WQ Output MaxMinRange=-1
WQ Daily Max Min Mean=-1
WQ Daily Range=0
WQ Daily Time=0
WQ Create Restart=0
WQ Fixed Restart=0
WQ System Summary=0
WQ Use Fixed Temperature=0
Sorting and Armoring Iterations= 10
XS Update Threshold= 0.02
Hydraulics Update Threshold= 0.02
Energy Slope Method= 1
Volume Change Method= 0
XS Weighting Method= 0
Number of US Weighted Cross Sections= 1
Number of DS Weighted Cross Sections= 1
Upstream XS Weight=0.25
Main XS Weight=0.5
Downstream XS Weight=0.25
Number of DS XS's Weighted with US Boundary= 1
Upstream Boundary Weight= 1
Weight of XSs Associated with US Boundary= 0
Number of US XS's Weighted with DS Boundary= 1
Downstream Boundary Weight= 0.5
Weight of XSs Associated with DS Boundary= 0.5
Sediment Output Level= 4
Mass or Volume Output= 0
Output Increment Type= 1
Profile and TS Output Increment= 10
XS Output Flag= 0
XS Output Increment= 10
Disregard all LS=0
Disregard all Conn=0
Disregard all Breaches=0
Disregard all Pumps=0

--- UNT025 IN SPCR.f01 (steady flow) ---

Flow Title=Multiple
Number of Profiles=7
Profile Names=10-year,25-year,50-year,1pct_min,100-year,1pct_plu,500-year
River Rch & RM= UNT025 IN SPCR,Reach-1,14736
     205     282     347     314     424     574     645
River Rch & RM= UNT025 IN SPCR,Reach-1,13372
     340     482     602     553     748    1011    1172
River Rch & RM= UNT025 IN SPCR,Reach-1,6311
     436     624     785     726     982    1327    1558
Boundary for River Rch & Prof#=UNT025 IN SPCR,Reach-1,1
Up Type=0
Dn Type=3
Dn Slope=0.005
Boundary for River Rch & Prof#=UNT025 IN SPCR,Reach-1,2
Up Type=0
Dn Type=3
Dn Slope=0.005
Boundary for River Rch & Prof#=UNT025 IN SPCR,Reach-1,3
Up Type=0
Dn Type=3
Dn Slope=0.005
Boundary for River Rch & Prof#=UNT025 IN SPCR,Reach-1,4
Up Type=0
Dn Type=3
Dn Slope=0.005
Boundary for River Rch & Prof#=UNT025 IN SPCR,Reach-1,5
Up Type=0
Dn Type=3
Dn Slope=0.005
Boundary for River Rch & Prof#=UNT025 IN SPCR,Reach-1,6
Up Type=0
Dn Type=3
Dn Slope=0.005
Boundary for River Rch & Prof#=UNT025 IN SPCR,Reach-1,7
Up Type=0
Dn Type=3
Dn Slope=0.005

--- UNT025 IN SPCR.g01 (geometry) ---

Geom Title=Existing Conditions
Program Version=4.10

River Reach=UNT025 IN SPCR  ,Reach-1
Reach XY= 30
      2240730.38     13265092.04      2241254.23     13265588.22
      2241129.22     13266107.45      2241388.08     13266579.84
      2241373.49      13266686.1       2241488.6      13266826.2
      2241478.18     13267015.26      2241796.55     13267617.33
      2241746.76     13268322.38      2241548.01     13268581.96
      2241393.91     13269035.27      2241028.04     13269715.21
      2241141.58     13270109.97       2241425.1     13270467.94
      2241459.19     13270881.25      2241625.82     13271232.99
      2241970.07     13271530.57      2242161.76     13271909.09
      2242570.06     13271962.36      2242932.81     13272366.64
      2243283.33     13272504.74      2244267.53     13272607.47
      2244426.62     13273063.35      2244734.28     13273607.41
      2245404.98     13274050.68      2245567.72     13274046.85
      2246015.26     13273802.33      2246574.83     13273616.73
      2247428.32     13273753.62      2247677.62     13274054.31

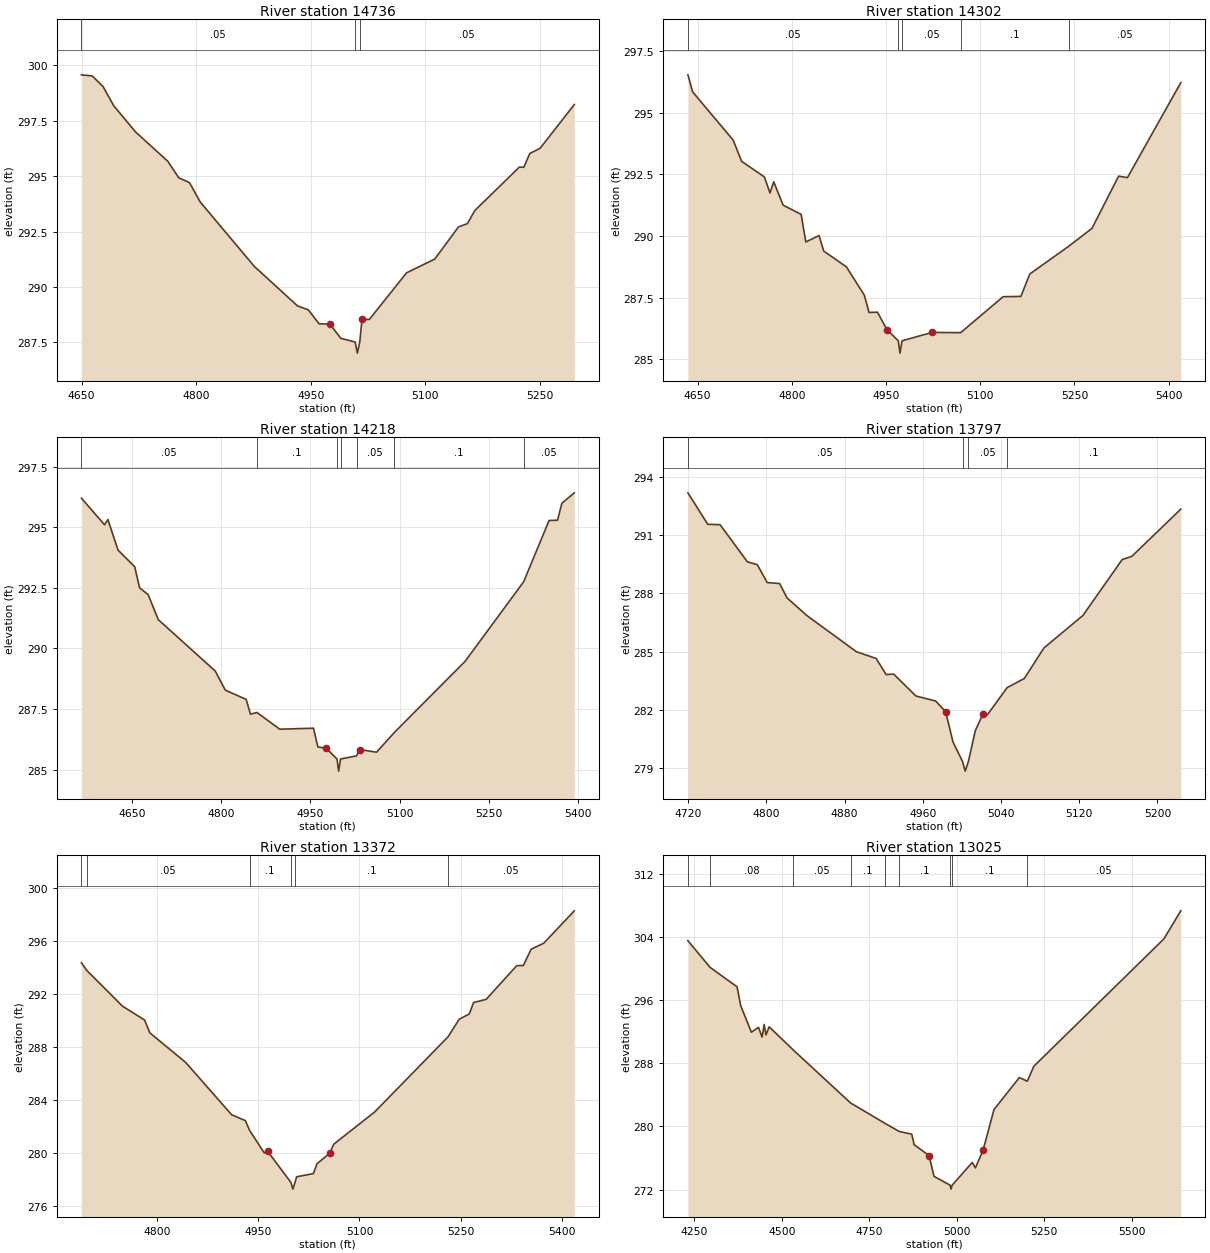
Type RM Length L Ch R = 1 ,14736   ,434,434,434
BEGIN DESCRIPTION:
UNT025 IN SPCR 33.0
END DESCRIPTION:
XS GIS Cut Line= 3
      2240537.72     13265396.86      2240787.72     13265146.85
      2240937.72     13264896.86
#Sta/Elev= 30
  4649.9  299.57    4664  299.52  4678.2  299.04  4692.3  298.17  4720.6     297
    4763  295.67  4777.2  294.93  4791.3  294.71  4805.5  293.83  4876.2  290.93
  4932.7  289.15  4946.9  288.97    4961  288.34  4975.2  288.33  4989.3  287.69
  5008.2  287.52    5011  287.02  5014.2  287.52  5017.1  288.54  5026.8  288.54
  5075.4  290.64  5112.3  291.26  5143.4  292.71  5155.1  292.86  5164.8  293.45
  5223.1  295.41  5228.9   295.4  5236.7  296.02  5250.3  296.26    5295  298.23
#Mann= 3 ,-1 , 0
  4649.9     .05       0  5008.2     .03       0  5014.2     .05       0
Bank Sta=4975.2,5017.1
XS Rating Curve= 0 ,0
Exp/Cntr=0.3,0.1

Type RM Length L Ch R = 1 ,14302   ,84,84,84
BEGIN DESCRIPTION:
UNT025 IN SPCR 32.0
END DESCRIPTION:
XS GIS Cut Line= 3
      2240787.74     13265646.84      2241087.72     13265446.85
      2241387.72     13265146.85
#Sta/Elev= 30
  4634.5  296.54    4642  295.85  4706.6  293.89  4720.1  293.03  4756.2   292.4
  4765.2  291.75  4771.2   292.2  4786.2  291.25  4814.8  290.88  4822.3  289.76
  4843.3  290.02  4850.8  289.39  4886.9  288.75  4915.4   287.6  4922.9   286.9
  4936.4  286.91  4951.5   286.2  4969.5  285.75  4972.2  285.25  4975.5  285.75
  5023.3  286.09  5068.8  286.08  5136.5  287.54  5164.7  287.55  5178.9  288.46
  5240.6  289.58  5277.9  290.31  5320.3  292.43  5334.4  292.37  5419.3  296.22
#Mann= 5 ,-1 , 0
  4634.5     .05       0  4969.5     .03       0  4975.5     .05       0
  5068.8      .1       0  5240.6     .05       0
Bank Sta=4951.5,5023.3
XS Rating Curve= 0 ,0
Exp/Cntr=0.3,0.1

Type RM Length L Ch R = 1 ,14218   ,421,421,421
BEGIN DESCRIPTION:
Mapping XS 8dc74917
END DESCRIPTION:
XS GIS Cut Line= 3
      2240789.74     13265729.86      2241032.78     13265611.81
      2241441.46     13265230.84
#Sta/Elev= 30
  4564.9   296.2  4603.8   295.1  4609.4  295.32  4626.4  294.06  4654.5  293.37
  4662.7   292.5  4677.1  292.22  4694.1  291.19  4789.9  289.07  4806.9  288.28
  4841.9   287.9  4849.2  287.29    4860  287.36  4898.5  286.67  4955.2  286.71
  4962.5  285.94  4976.7  285.88  4994.7  285.44  4997.5  284.94  5000.7  285.44
  5027.5  285.57  5033.2  285.83  5061.2  285.72  5090.6  286.52  5210.2  289.47
  5308.6  292.75  5351.4  295.28  5365.6  295.29  5372.9  295.99  5393.8  296.42
#Mann= 7 ,-1 , 0
  4564.9     .05       0    4860      .1       0  4994.7     .07       0
  5000.7      .1       0  5027.5     .05       0  5090.6      .1       0
  5308.6     .05       0
Bank Sta=4976.7,5033.2
XS Rating Curve= 0 ,0
Exp/Cntr=0.3,0.1

Type RM Length L Ch R = 1 ,13797   ,425,425,425
BEGIN DESCRIPTION:
UNT025 IN SPCR 31.0
END DESCRIPTION:
XS GIS Cut Line= 3
      2240887.72     13265796.86      2241187.72     13265846.85
      2241387.68     13265846.85
#Sta/Elev= 30
  4719.8  293.18  4740.1  291.56  4752.7  291.54  4780.6  289.63  4790.8  289.48
  4800.9  288.56  4813.6  288.51  4821.2  287.77  4841.5  286.86  4892.1     285
  4912.4  284.65  4922.6  283.82  4930.2  283.85    4953  282.72  4973.2  282.46
  4983.4  281.91    4991  280.34  5000.7  279.35  5003.4  278.85  5006.7  279.35
  5013.8  280.94  5021.4  281.77  5026.4  281.77  5046.3  283.15  5063.9  283.62
  5083.9  285.19  5123.9  286.87  5163.9  289.74  5173.9  289.91  5223.9  292.34
#Mann= 4 ,-1 , 0
  4719.8     .05       0  5000.7     .03       0  5006.7     .05       0
  5046.3      .1       0
Bank Sta=4983.4,5021.4
XS Rating Curve= 0 ,0
Exp/Cntr=0.3,0.1

Type RM Length L Ch R = 1 ,13372   ,347,347,347
BEGIN DESCRIPTION:
UNT025 IN SPCR 30.0
END DESCRIPTION:
XS GIS Cut Line= 3
      2240887.71     13266196.85      2241187.72     13266246.85
      2241587.68     13266096.87
#Sta/Elev= 30
  4687.5  294.36  4695.6  293.77  4748.3  291.09  4781.3  290.04  4788.9  289.08
  4842.1  286.85  4910.5   282.9  4930.8  282.46  4936.9  281.74  4958.7  280.03
  4963.8  280.15  4998.4   277.8  5001.2   277.3  5004.4   277.8  5006.8  278.23
  5031.7  278.47    5037  279.21  5055.7     280    5062  280.69  5122.5  283.11
  5231.5  288.78    5248   290.1  5263.1   290.5  5269.3  291.36    5288   291.6
  5333.4  294.14  5343.2  294.15  5354.8  295.38  5373.5  295.83  5418.8  298.27
#Mann= 6 ,-1 , 0
  4687.5     .08       0  4695.6     .05       0  4936.9      .1       0
  4998.4     .07       0  5004.4      .1       0  5231.5     .05       0
Bank Sta=4963.8,5055.7
XS Rating Curve= 0 ,0
Exp/Cntr=0.3,0.1

Type RM Length L Ch R = 1 ,13025   ,120,120,120
BEGIN DESCRIPTION:
Mapping XS 5399971f
END DESCRIPTION:
XS GIS Cut Line= 4
      2240689.92     13266219.21      2241096.15     13266299.94
      2241325.31     13266542.13      2241962.99     13266370.34
#Sta/Elev= 30
  4231.7  303.51  4295.2  300.13  4372.2  297.67  4382.4   295.3    4413  291.93
  4433.4  292.54  4443.6  291.31  4449.6   292.9  4454.7  291.59  4463.9  292.61
  4533.2  289.66  4696.3  282.98  4793.4  280.43  4834.8  279.38  4871.2  279.02
  4878.1  277.69  4920.6  276.32  4934.7  273.69  4980.6  272.57  4983.4  272.07
  4986.6  272.57  5043.9  275.44  5053.2  274.76    5075  277.01  5106.1  282.14
  5178.6  286.19  5201.3  285.73    5220  287.62  5591.5  303.74  5639.7  307.29
#Mann= 9 ,-1 , 0
  4231.7     .05       0  4295.2     .08       0  4533.2     .05       0
  4696.3      .1       0  4793.4     .05       0  4834.8      .1       0
  4980.6     .07       0  4986.6      .1       0  5201.3     .05       0
Bank Sta=4920.6,5075
XS Rating Curve= 0 ,0
Exp/Cntr=0.3,0.1

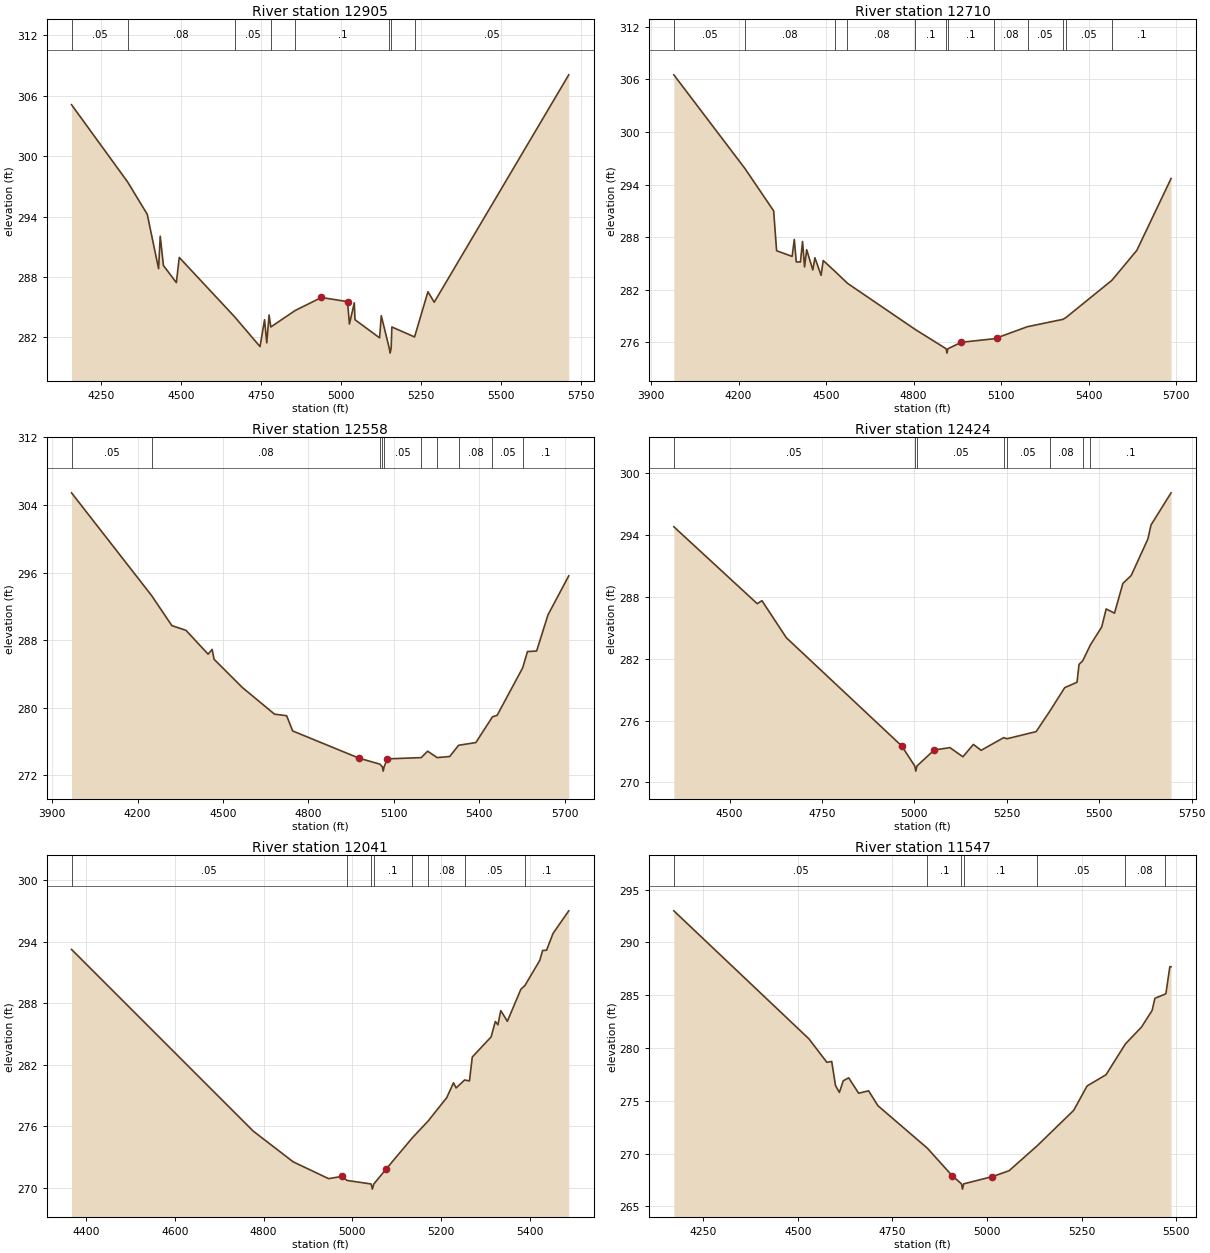
Type RM Length L Ch R = 1 ,12905   ,195,195,195
BEGIN DESCRIPTION:
Mapping XS 257bd034
END DESCRIPTION:
XS GIS Cut Line= 6
      2240653.42     13266292.12      2241059.69     13266352.02
       2241257.6     13266560.35      2241416.46     13266661.92
      2241484.17     13266664.52      2242059.73     13266492.63
#Sta/Elev= 30
  4156.7  305.12    4332  297.45  4393.5  294.23    4429  288.82  4434.1  292.05
  4444.1  289.14  4484.5  287.44  4493.6  289.94  4666.8  284.04  4746.2  281.08
  4760.4  283.75  4767.3  281.45  4774.5  284.22  4779.9  283.03  4856.4  284.67
  4937.9  285.96  5019.8  285.55  5025.8  283.32    5041  285.43  5043.2  283.75
  5120.1  281.95  5125.4  284.15  5150.3  280.93    5153  280.43  5156.3  280.93
  5158.5  283.03  5229.5  282.04  5271.3  286.53    5291  285.49  5711.7  308.09
#Mann= 8 ,-1 , 0
  4156.7     .05       0    4332     .08       0  4666.8     .05       0
  4779.9     .08       0  4856.4      .1       0  5150.3     .07       0
  5156.3      .1       0  5229.5     .05       0
Bank Sta=4937.9,5019.8
XS Rating Curve= 0 ,0
Exp/Cntr=0.3,0.1

Type RM Length L Ch R = 1 ,12710   ,152,152,152
BEGIN DESCRIPTION:
Mapping XS 0c000496
END DESCRIPTION:
XS GIS Cut Line= 4
       2240617.8     13266328.58      2241020.62     13266373.72
      2241784.51     13267102.89      2242013.25     13267023.18
#Sta/Elev= 30
  3978.3  306.52  4221.8  295.83  4320.3  290.99  4330.4  286.44  4383.6  285.79
    4391  287.73  4397.9  285.16    4412  285.15  4419.3  287.49  4426.2  284.59
  4433.4  286.56  4454.5  284.25  4461.7  285.64  4482.8  283.63  4490.1  285.32
  4530.3  284.09  4573.3  282.72  4805.5  277.45  4911.3  275.25  4914.1  274.75
  4917.3  275.25  4963.7  275.99  5075.5  276.39  5084.2  276.48  5190.1  277.77
  5311.8  278.61  5322.1  278.82  5479.1  283.06  5564.6  286.48  5681.9  294.68
#Mann= 12 ,-1 , 0
  3978.3     .05       0  4221.8     .08       0  4530.3     .05       0
  4573.3     .08       0  4805.5      .1       0  4911.3     .07       0
  4917.3      .1       0  5075.5     .08       0  5190.1     .05       0
  5311.8     .08       0  5322.1     .05       0  5479.1      .1       0
Bank Sta=4963.7,5084.2
XS Rating Curve= 0 ,0
Exp/Cntr=0.3,0.1

Type RM Length L Ch R = 1 ,12558   ,134,134,134
BEGIN DESCRIPTION:
Mapping XS ef72bec7
END DESCRIPTION:
XS GIS Cut Line= 5
      2240642.16     13266389.35      2240967.67     13266432.75
      2241449.44     13266931.88      2241744.58     13267209.66
      2242043.37     13267097.07
#Sta/Elev= 30
    3968  305.44  4249.6  293.27  4320.5  289.73  4370.1  289.17  4447.8  286.35
    4462  286.91  4468.9  285.74    4568  282.41  4681.2  279.25  4723.6  279.07
    4745  277.26  4978.3  274.04  5051.7  273.33  5060.1  273.01  5062.9  272.51
  5066.1  273.01  5077.3  273.96  5196.5  274.11  5218.9  274.87  5252.6  274.11
  5296.6  274.24  5327.7  275.57  5388.4  275.89  5446.7  278.94  5462.9   279.1
  5552.8  284.73  5569.7  286.66  5601.8  286.72  5641.8     291  5714.7  295.62
#Mann= 10 ,-1 , 0
    3968     .05       0  4249.6     .08       0  5051.7     .05       0
  5060.1     .07       0  5066.1     .05       0  5196.5     .08       0
  5252.6     .05       0  5327.7     .08       0  5446.7     .05       0
  5552.8      .1       0
Bank Sta=4978.3,5077.3
XS Rating Curve= 0 ,0
Exp/Cntr=0.3,0.1

Type RM Length L Ch R = 1 ,12424   ,383,383,383
BEGIN DESCRIPTION:
Mapping XS 19b7a099
END DESCRIPTION:
XS GIS Cut Line= 4
      2240881.76     13266873.73       2241548.4     13267075.11
      2241763.68     13267269.56      2242086.58     13267113.31
#Sta/Elev= 30
  4349.1   294.8  4574.7  287.34  4587.5  287.63  4653.4  284.04  4965.7  273.54
  5000.9   271.6  5003.7   271.1  5006.9   271.6  5053.4  273.15    5096  273.38
  5131.2  272.49  5159.5  273.69  5180.5  273.12  5241.6  274.35  5250.2  274.24
  5329.2  274.93  5365.6  276.88  5406.7   279.2  5439.8  279.72  5445.4  281.46
  5455.1  281.79  5476.2  283.35  5506.7  285.08  5518.7  286.83  5541.3  286.42
  5563.9   289.3  5586.4  290.07  5631.6  293.61    5640  294.97  5694.3  298.09
#Mann= 8 ,-1 , 0
  4349.1     .05       0  5000.9     .03       0  5006.9     .05       0
  5241.6     .08       0  5250.2     .05       0  5365.6     .08       0
  5455.1     .05       0  5476.2      .1       0
Bank Sta=4965.7,5053.4
XS Rating Curve= 0 ,0
Exp/Cntr=0.3,0.1

Type RM Length L Ch R = 1 ,12041   ,494,494,494
BEGIN DESCRIPTION:
UNT025 IN SPCR 27.0
END DESCRIPTION:
XS GIS Cut Line= 3
       2241037.7     13267396.85      2241687.72     13267396.85
      2242087.71     13267146.86
#Sta/Elev= 30
  4366.7  293.23  4776.7  275.53  4866.7  272.54  4946.7   270.9  4976.7  271.12
    4988  270.73  5042.6  270.38  5045.4  269.88  5048.6  270.38  5075.7   271.8
  5135.4  274.87  5171.7  276.54  5213.1  278.79  5228.4  280.24  5234.3  279.74
  5253.4  280.51  5264.4  280.42  5270.8  282.75  5313.3  284.71  5322.7  286.21
  5328.6  285.89  5335.1  287.27  5349.9  286.23  5380.5  289.36  5389.6  289.72
    5423  292.16  5429.5  293.13  5438.3  293.15    5453  294.79  5488.4  296.99
#Mann= 8 ,-1 , 0
  4366.7     .05       0    4988      .1       0  5042.6     .07       0
  5048.6      .1       0  5135.4     .05       0  5171.7     .08       0
  5253.4     .05       0  5389.6      .1       0
Bank Sta=4976.7,5075.7
XS Rating Curve= 0 ,0
Exp/Cntr=0.3,0.1

Type RM Length L Ch R = 1 ,11547   ,375,375,375
BEGIN DESCRIPTION:
UNT025 IN SPCR 26.0
END DESCRIPTION:
XS GIS Cut Line= 3
       2240987.7     13267696.85      2241787.72     13267846.85
      2242187.75     13267546.83
#Sta/Elev= 30
  4172.2  292.99  4529.2  280.87  4576.6  278.65  4589.4  278.73  4599.5  276.44
  4609.7   275.8  4619.9   276.9  4634.3  277.18  4660.6  275.72  4686.9  275.95
  4711.5  274.54  4842.1  270.52  4907.3  267.93  4932.3  267.14    4935  266.64
  4938.3  267.14  5014.3  267.83    5058  268.38  5132.9  270.76  5228.9   274.1
  5264.3  276.41  5314.3  277.47  5365.6  280.39    5408  281.98  5436.2  283.56
  5443.5  284.71  5469.6  285.09  5472.6  285.16    5483   287.7  5486.2   287.7
#Mann= 7 ,-1 , 0
  4172.2     .05       0  4842.1      .1       0  4932.3     .07       0
  4938.3      .1       0  5132.9     .05       0  5365.6     .08       0
  5469.6     .05       0
Bank Sta=4907.3,5014.3
XS Rating Curve= 0 ,0
Exp/Cntr=0.3,0.1

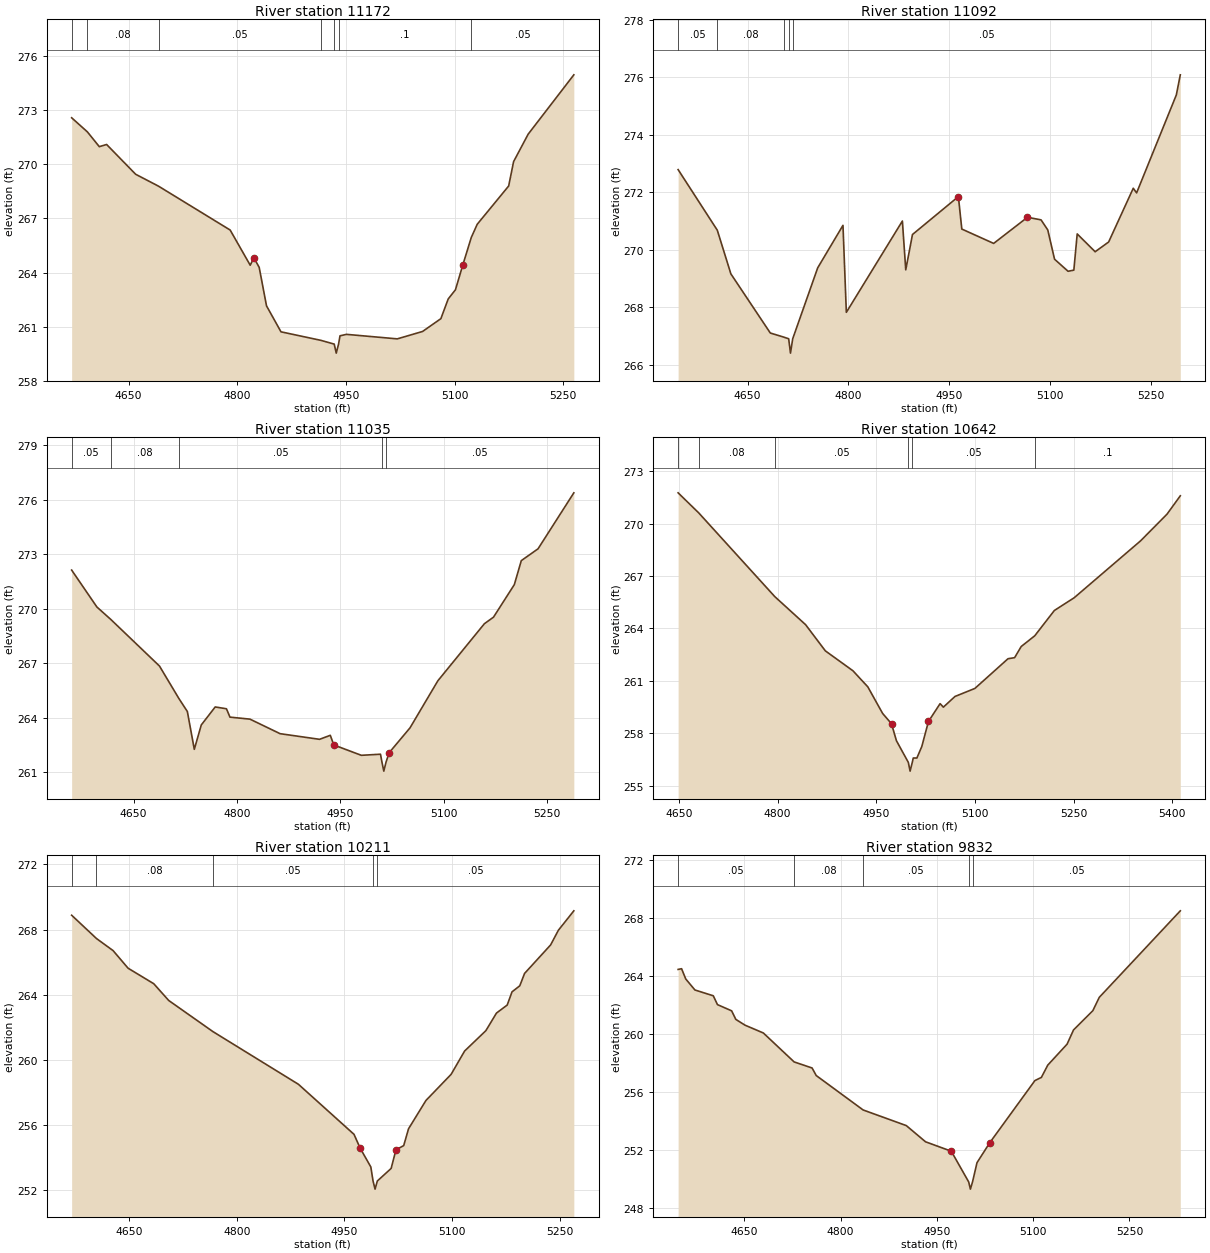
Type RM Length L Ch R = 1 ,11172   ,80,80,80
BEGIN DESCRIPTION:
Mapping XS 2e50aa5e
END DESCRIPTION:
XS GIS Cut Line= 2
      2241349.64     13268150.63      2242040.62     13268209.66
#Sta/Elev= 30
  4571.3  272.58    4593   271.8  4609.5  270.98  4619.6   271.1  4659.7  269.45
  4691.3  268.79  4790.2  266.36  4817.9  264.41    4823  264.82  4830.3  264.29
  4840.4  262.16  4860.4  260.72  4915.3  260.25  4933.9  260.04  4936.7  259.54
  4939.9  260.04  4941.9   260.5  4950.8  260.58    5021  260.33  5055.9  260.74
  5081.2  261.45  5091.3  262.54  5101.3  263.05  5111.3   264.4  5123.2  265.95
  5131.4  266.68  5174.8   268.8  5181.6  270.15  5201.7  271.67  5264.8  274.96
#Mann= 7 ,-1 , 0
  4571.3     .05       0    4593     .08       0  4691.3     .05       0
  4915.3      .1       0  4933.9     .07       0  4939.9      .1       0
  5123.2     .05       0
Bank Sta=4823,5111.3
XS Rating Curve= 0 ,0
Exp/Cntr=0.3,0.1

Type RM Length L Ch R = 1 ,11092   ,57,57,57
BEGIN DESCRIPTION:
Mapping XS d03f1392
END DESCRIPTION:
XS GIS Cut Line= 2
       2241311.4     13268213.13      2242053.55     13268299.83
#Sta/Elev= 30
  4546.5  272.79  4604.8  270.68    4625  269.16  4683.7   267.1  4703.3  266.96
    4711   266.9  4713.7   266.4    4717   266.9  4754.2  269.37  4791.8  270.85
  4796.8  267.82  4880.2     271  4885.2   269.3  4895.2  270.53  4963.5  271.85
  4968.6  270.72    5016  270.22  5066.3  271.13  5086.5  271.04  5096.5  270.69
  5106.6  269.67  5126.7  269.25  5135.3  269.29  5140.3  270.55    5167  269.93
  5187.1  270.27  5223.7  272.14  5228.7  271.98  5287.8  275.39  5293.7  276.09
#Mann= 5 ,-1 , 0
  4546.5     .05       0  4604.8     .08       0  4703.3     .05       0
    4711     .03       0    4717     .05       0
Bank Sta=4963.5,5066.3
XS Rating Curve= 0 ,0
Exp/Cntr=0.3,0.1

Type RM Length L Ch R = 1 ,11035   ,393,393,393
BEGIN DESCRIPTION:
UNT025 IN SPCR 25.0
END DESCRIPTION:
XS GIS Cut Line= 2
      2241311.41     13268261.74       2242033.2     13268358.91
#Sta/Elev= 30
  4560.2  272.12  4596.8  270.09  4617.1   269.4  4687.6  266.84  4715.8  265.05
    4728  264.34  4738.1  262.26  4748.2   263.6  4768.4  264.59  4784.7  264.49
  4789.8  264.03  4818.8  263.92  4862.5  263.12  4919.7  262.81  4935.3  263.03
  4940.4   262.5  4980.3  261.93  5008.1  261.99  5010.2  261.56  5012.9  261.06
  5016.2  261.56  5020.6  262.07  5050.9  263.44  5091.3  266.03  5158.8  269.17
    5172  269.53  5202.2  271.32  5212.3  272.64  5236.6  273.29  5288.5  276.37
#Mann= 5 ,-1 , 0
  4560.2     .05       0  4617.1     .08       0  4715.8     .05       0
  5010.2     .03       0  5016.2     .05       0
Bank Sta=4940.4,5020.6
XS Rating Curve= 0 ,0
Exp/Cntr=0.3,0.1

Type RM Length L Ch R = 1 ,10642   ,431,431,431
BEGIN DESCRIPTION:
UNT025 IN SPCR 24.0
END DESCRIPTION:
XS GIS Cut Line= 3
      2241237.71     13268446.85      2241537.72     13268646.85
      2241937.74     13268596.85
#Sta/Elev= 30
  4648.6  271.76    4680  270.61  4795.7  265.82  4842.4  264.22  4872.5  262.72
  4914.5  261.58  4937.1  260.66  4959.6  259.14  4973.1  258.55  4980.6  257.58
  4998.7  256.34  5001.4  255.84  5004.7  256.34  5006.2  256.59  5011.7  256.59
  5019.2  257.25  5029.3  258.68    5047   259.7    5052   259.5  5069.6  260.11
  5099.9  260.57  5150.3  262.27  5160.3  262.33  5170.4  262.97  5190.9  263.58
  5220.8  265.03    5251  265.76  5351.8  269.01  5392.1  270.54  5412.3  271.59
#Mann= 6 ,-1 , 0
  4648.6     .05       0    4680     .08       0  4795.7     .05       0
  4998.7     .03       0  5004.7     .05       0  5190.9      .1       0
Bank Sta=4973.1,5029.3
XS Rating Curve= 0 ,0
Exp/Cntr=0.3,0.1

Type RM Length L Ch R = 1 ,10211   ,379,379,379
BEGIN DESCRIPTION:
UNT025 IN SPCR 23.0
END DESCRIPTION:
XS GIS Cut Line= 3
      2241137.74     13268696.88      2241387.72     13269046.85
      2241637.68     13269146.84
#Sta/Elev= 30
  4570.1  268.88  4604.7  267.45  4627.8  266.71  4648.7  265.63  4684.4  264.68
  4705.3  263.65  4766.9  261.74  4885.9  258.51  4963.3  255.44  4971.9  254.59
  4986.7  253.44  4989.8  252.58  4992.6  252.08  4995.8  252.58    5015  253.35
  5021.7  254.49  5032.5  254.75  5039.2  255.78  5063.5  257.52  5098.5  259.12
  5117.3  260.55  5146.9   261.8  5161.7  262.88  5176.6  263.37  5183.3  264.18
  5194.1  264.55  5200.8  265.31  5237.1  267.06  5247.9  267.96  5269.4  269.15
#Mann= 5 ,-1 , 0
  4570.1     .05       0  4604.7     .08       0  4766.9     .05       0
  4989.8     .03       0  4995.8     .05       0
Bank Sta=4971.9,5021.7
XS Rating Curve= 0 ,0
Exp/Cntr=0.3,0.1

Type RM Length L Ch R = 1 ,9832    ,430,430,430
BEGIN DESCRIPTION:
UNT025 IN SPCR 22.0
END DESCRIPTION:
XS GIS Cut Line= 3
      2240826.66     13269200.81       2240961.3     13269360.38
      2241533.74      13269400.2
#Sta/Elev= 30
  4546.7  264.47  4552.1  264.52  4558.6  263.81  4572.9  263.05  4601.5  262.65
    4608  262.04  4630.1  261.61  4636.6  261.02  4650.9  260.62  4679.5  260.08
  4727.5  258.08  4755.5  257.66  4761.9  257.14    4835  254.76  4902.3  253.68
  4932.3  252.56  4972.4  251.91  4999.5  249.79  5002.2  249.29  5005.5  249.79
  5012.5  251.12  5032.6  252.51  5102.7  256.79  5112.8  257.01  5122.8  257.86
  5152.9  259.31  5162.9  260.29    5193  261.62    5203  262.54  5329.3  268.52
#Mann= 5 ,-1 , 0
  4546.7     .05       0  4727.5     .08       0    4835     .05       0
  4999.5     .03       0  5005.5     .05       0
Bank Sta=4972.4,5032.6
XS Rating Curve= 0 ,0
Exp/Cntr=0.3,0.1

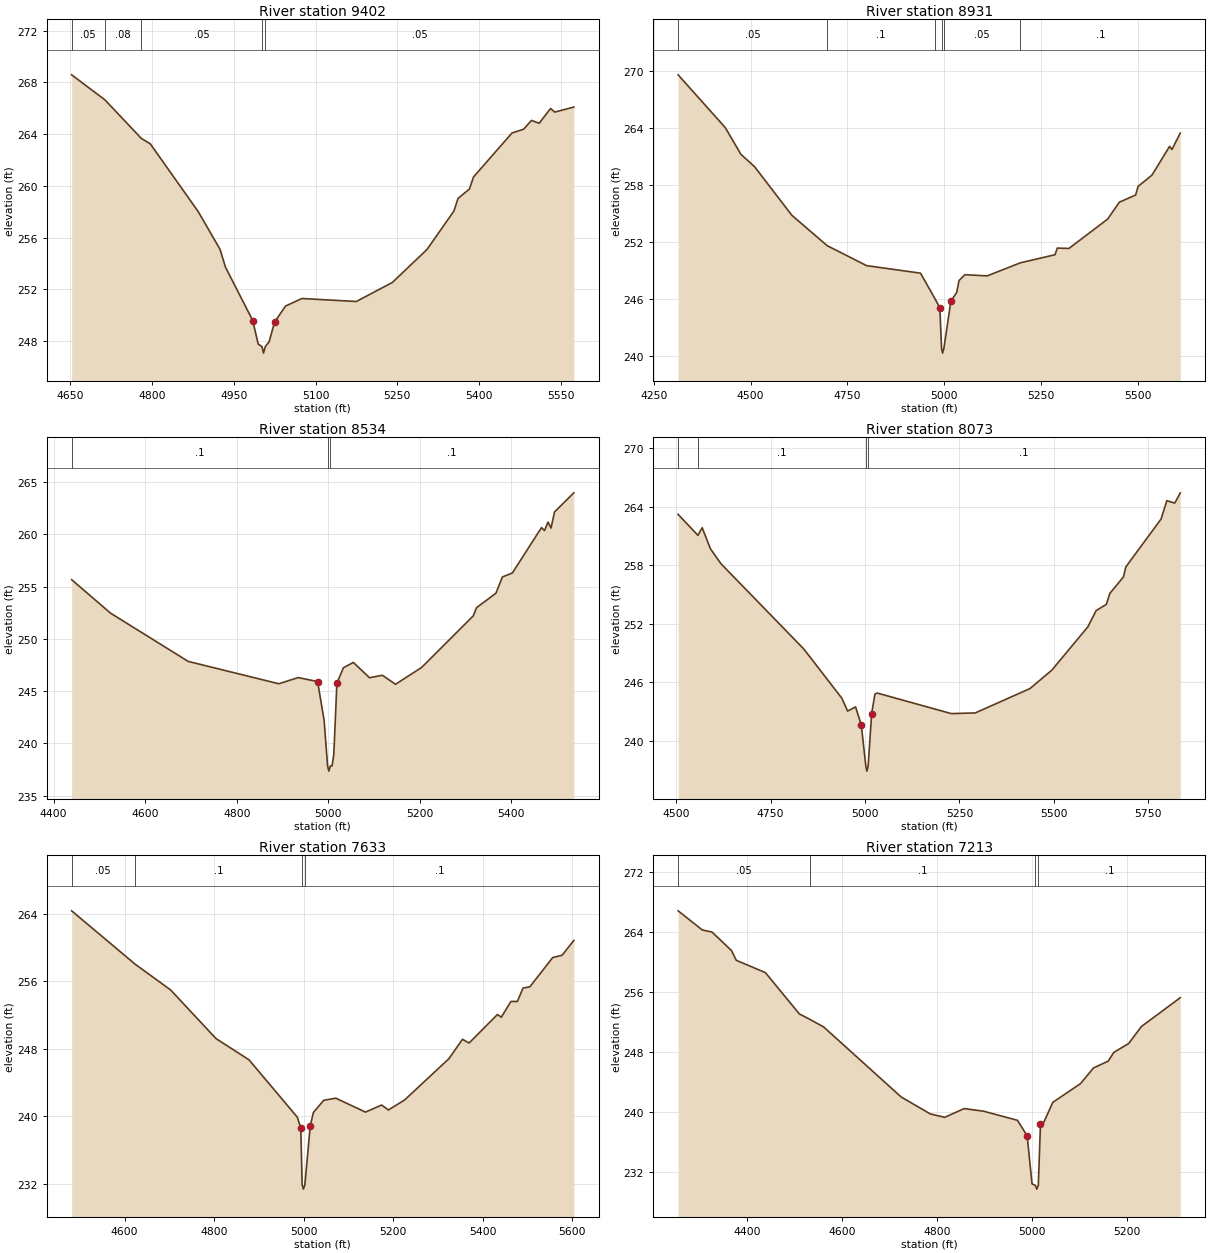
Type RM Length L Ch R = 1 ,9402    ,471,471,471
BEGIN DESCRIPTION:
UNT025 IN SPCR 21.0
END DESCRIPTION:
XS GIS Cut Line= 4
       2240721.9     13269664.58      2240826.65     13269759.35
       2241270.5     13269754.36      2241522.72     13269531.82
#Sta/Elev= 30
  4652.4  268.58  4713.4  266.65  4780.2  263.67  4796.7  263.25  4884.7  258.01
  4924.7   255.1  4934.7  253.72  4984.7   249.6  4994.7  247.78  5001.7  247.58
  5004.5  247.08  5007.7  247.58  5014.7  247.95  5024.7  249.47  5044.7  250.71
  5074.8   251.3  5174.8  251.07  5240.9  252.54  5304.5  255.09  5353.9  258.06
  5361.4  259.03  5382.3  259.76  5389.8  260.69  5460.5  264.09  5481.9  264.38
  5496.1  265.06  5510.3  264.84  5531.2  265.98  5538.8   265.7  5573.9  266.09
#Mann= 5 ,-1 , 0
  4652.4     .05       0  4713.4     .08       0  4780.2     .05       0
  5001.7     .03       0  5007.7     .05       0
Bank Sta=4984.7,5024.7
XS Rating Curve= 0 ,0
Exp/Cntr=0.3,0.1

Type RM Length L Ch R = 1 ,8931    ,397,397,397
BEGIN DESCRIPTION:
UNT025 IN SPCR 20.0
END DESCRIPTION:
XS GIS Cut Line= 3
      2240577.27     13270452.56      2240861.56     13270407.68
      2241709.34     13269859.11
#Sta/Elev= 30
  4312.7  269.59  4434.6  264.03  4475.1  261.21  4510.1  259.93  4606.6   254.8
    4698   251.6  4799.8   249.5    4939  248.71  4975.7  246.07    4989  245.06
  4993.4  240.79  4996.1  240.29  4999.4  240.79  5017.5  245.77  5032.6  246.68
  5038.6  247.94  5053.8  248.55  5111.2  248.42  5197.2   249.8  5286.6  250.65
  5292.5  251.35  5322.5  251.31  5422.5   254.4  5452.8  256.18    5495  256.94
  5501.2  257.84  5537.2  259.04  5582.7  262.06  5588.7  261.73  5610.3  263.46
#Mann= 6 ,-1 , 0
  4312.7     .05       0    4698      .1       0  4975.7     .05       0
  4993.4     .03       0  4999.4     .05       0  5197.2      .1       0
Bank Sta=4989,5017.5
XS Rating Curve= 0 ,0
Exp/Cntr=0.3,0.1

Type RM Length L Ch R = 1 ,8534    ,461,461,461
BEGIN DESCRIPTION:
UNT025 IN SPCR 19.0
END DESCRIPTION:
XS GIS Cut Line= 3
       2241037.7     13270896.87      2241437.72     13270496.85
      2241787.71     13270096.87
#Sta/Elev= 30
  4439.4  255.66  4524.3  252.46    4694  247.84    4892   245.7  4934.4  246.29
  4976.8  245.91    4991   242.2  4998.6  237.84  5001.3  237.34  5004.6  237.84
  5008.4  237.84  5012.2  238.96  5018.9  245.75  5033.1  247.23  5054.9  247.74
  5090.1  246.28  5118.5  246.51    5147  245.65    5204  247.26  5316.9   252.2
    5324  252.98  5366.3  254.36  5380.5  255.92  5402.3   256.3  5465.9  260.64
  5472.6  260.36  5480.1  261.17  5486.8   260.6  5494.4  262.14  5536.6  263.97
#Mann= 3 ,-1 , 0
  4439.4      .1       0  4998.6     .07       0  5004.6      .1       0
Bank Sta=4976.8,5018.9
XS Rating Curve= 0 ,0
Exp/Cntr=0.3,0.1

Type RM Length L Ch R = 1 ,8073    ,440,440,440
BEGIN DESCRIPTION:
UNT025 IN SPCR 18.0
END DESCRIPTION:
XS GIS Cut Line= 3
      2241110.88     13271260.51      2241380.22      13271021.1
      2242192.93     13270492.59
#Sta/Elev= 30
  4505.1  263.24  4557.6  261.09  4568.9  261.87  4590.6  259.71    4619  258.16
  4838.1  249.42  4938.7  244.38  4953.9  243.06    4975  243.49  4990.1  241.65
  5002.2   237.4    5005   236.9  5008.2   237.4  5017.6  242.81  5026.3  244.81
  5032.3  244.91  5228.6   242.8  5291.9  242.87  5436.9  245.37  5494.7  247.26
  5590.1   251.7  5612.1  253.37  5639.1  254.01  5648.3  255.13  5684.5  256.83
  5690.5  257.84  5784.1  262.77  5799.2  264.64  5820.3   264.4  5834.9  265.45
#Mann= 4 ,-1 , 0
  4505.1     .05       0  4557.6      .1       0  5002.2     .07       0
  5008.2      .1       0
Bank Sta=4990.1,5017.6
XS Rating Curve= 0 ,0
Exp/Cntr=0.3,0.1

Type RM Length L Ch R = 1 ,7633    ,420,420,420
BEGIN DESCRIPTION:
UNT025 IN SPCR 17.0
END DESCRIPTION:
XS GIS Cut Line= 3
       2241280.5     13271584.63      2241559.76     13271415.08
      2242222.86     13270976.34
#Sta/Elev= 30
  4481.6  264.36  4622.9  258.06  4702.7  254.98  4804.2  249.21  4877.8   246.7
  4985.7   239.9  4993.5  238.61  4996.5  231.87  4999.3  231.37  5002.5  231.87
  5014.6  238.87  5021.7  240.46  5044.7   241.9  5071.7  242.15    5138   240.5
  5174.1  241.34  5189.1  240.75  5225.2  241.93  5324.5  246.84  5354.6  249.13
  5369.4  248.69  5432.8  252.07  5441.4  251.75  5462.9  253.62  5477.3  253.62
    5490  255.21  5505.1  255.35  5556.2  258.82  5577.3   259.1  5603.4  260.85
#Mann= 4 ,-1 , 0
  4481.6     .05       0  4622.9      .1       0  4996.5     .07       0
  5002.5      .1       0
Bank Sta=4993.5,5014.6
XS Rating Curve= 0 ,0
Exp/Cntr=0.3,0.1

Type RM Length L Ch R = 1 ,7213    ,301,301,301
BEGIN DESCRIPTION:
UNT025 IN SPCR 16.0
END DESCRIPTION:
XS GIS Cut Line= 3
      2241287.68     13271746.86      2242037.72     13271596.85
      2242287.69     13271446.88
#Sta/Elev= 30
    4255  266.86    4306   264.3  4326.4  264.02  4367.2  261.56  4377.4  260.25
  4438.6  258.61    4510  253.09  4533.1  252.33    4561  251.36  4724.2     242
  4785.3  239.74  4815.9  239.28  4856.7  240.45  4897.5   240.1  4968.9  238.88
  4989.3   236.8  4999.5  230.39  5006.7  230.19  5009.4  229.69  5012.7  230.19
  5017.3  238.41  5022.8  238.41  5043.2  241.28  5101.5  243.78  5128.7  245.87
  5159.8  246.79  5171.5  247.95  5202.6  249.13  5229.8  251.42  5311.4  255.26
#Mann= 4 ,-1 , 0
    4255     .05       0  4533.1      .1       0  5006.7     .07       0
  5012.7      .1       0
Bank Sta=4989.3,5017.3
XS Rating Curve= 0 ,0
Exp/Cntr=0.3,0.1

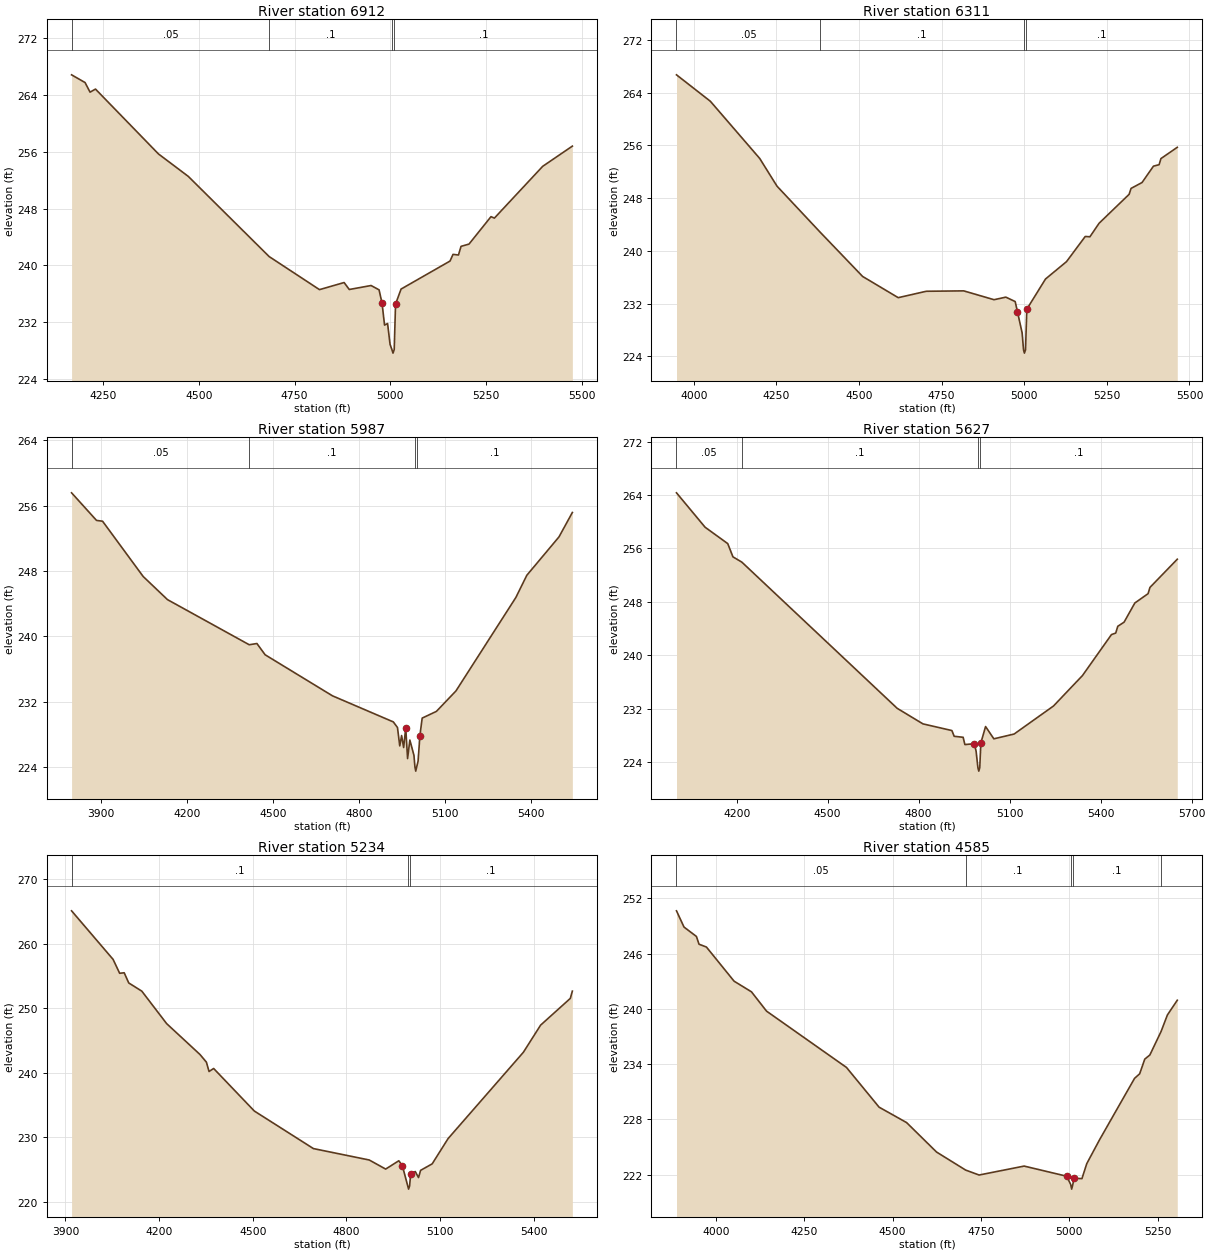
Type RM Length L Ch R = 1 ,6912    ,601,601,601
BEGIN DESCRIPTION:
UNT025 IN SPCR 15.0
END DESCRIPTION:
XS GIS Cut Line= 4
      2241539.84     13272447.39      2241893.89     13272168.14
      2242307.83     13271664.44      2242347.72     13271464.98
#Sta/Elev= 30
  4168.4  266.87  4203.6  265.78  4216.6  264.43  4230.8  264.86    4395  255.72
  4472.9  252.55  4683.8  241.25  4815.1  236.59  4879.3  237.59  4892.8  236.61
  4949.6  237.17  4970.5  236.56  4978.3  234.67  4984.8  231.59  4992.7  231.81
  4999.2  228.87    5004  228.14  5006.8  227.64    5010  228.14  5013.5  234.55
  5027.9  236.67  5155.6  240.62  5163.4  241.56  5177.6  241.47  5184.3  242.69
  5205.1  243.01  5262.5  246.88  5271.3  246.67  5397.3  253.97  5474.7  256.82
#Mann= 4 ,-1 , 0
  4168.4     .05       0  4683.8      .1       0    5004     .07       0
    5010      .1       0
Bank Sta=4978.3,5013.5
XS Rating Curve= 0 ,0
Exp/Cntr=0.3,0.1

Type RM Length L Ch R = 1 ,6311    ,324,324,324
BEGIN DESCRIPTION:
UNT025 IN SPCR 14.0
END DESCRIPTION:
XS GIS Cut Line= 4
      2241837.68     13272646.87       2242357.7      13272377.6
      2242831.48     13271878.88      2242935.64     13271660.65
#Sta/Elev= 30
  3947.8  266.69  4050.3  262.68  4199.6  254.01  4251.9  249.81  4382.5  242.83
  4510.9  236.12  4618.7   232.9  4703.6  233.87  4816.9  233.93  4908.7  232.59
  4944.3  232.98  4972.6  232.31  4979.5  230.77  4993.6  227.57  4997.9  224.99
  5000.6  224.49  5003.9  224.99  5007.8  231.15  5064.4  235.73  5127.9  238.36
  5184.6  242.18  5198.7  242.13  5226.6  244.19  5317.4  248.57  5323.3  249.47
  5356.5  250.36    5391  252.84  5408.1  253.06  5413.7  253.99  5463.1   255.7
#Mann= 4 ,-1 , 0
  3947.8     .05       0  4382.5      .1       0  4997.9     .07       0
  5003.9      .1       0
Bank Sta=4979.5,5007.8
XS Rating Curve= 0 ,0
Exp/Cntr=0.3,0.1

Type RM Length L Ch R = 1 ,5987    ,360,360,360
BEGIN DESCRIPTION:
UNT025 IN SPCR 13.0
END DESCRIPTION:
XS GIS Cut Line= 4
      2242063.49     13273195.46      2242392.61      13272881.3
      2242951.17     13272198.06      2242985.97     13271790.44
#Sta/Elev= 30
  3798.3  257.58  3885.3   254.2  3906.4   254.1  4047.9  247.33  4132.8  244.49
  4417.9  238.96  4444.7  239.11  4473.4  237.73  4708.2   232.7  4920.6   229.5
    4935  228.81  4942.9  226.56  4949.4  227.83  4956.5  226.36  4963.7  228.78
  4970.2  225.01  4978.1  227.28  4992.4  225.41  4995.9  223.97  4998.6  223.47
  5001.9  223.97  5006.8  224.69  5013.2  227.83  5021.1  229.97  5070.7  230.79
  5138.9   233.3  5347.8  244.75    5386  247.47  5498.3  252.18  5544.9  255.17
#Mann= 4 ,-1 , 0
  3798.3     .05       0  4417.9      .1       0  4995.9     .07       0
  5001.9      .1       0
Bank Sta=4963.7,5013.2
XS Rating Curve= 0 ,0
Exp/Cntr=0.3,0.1

Type RM Length L Ch R = 1 ,5627    ,393,393,393
BEGIN DESCRIPTION:
UNT025 IN SPCR 12.0
END DESCRIPTION:
XS GIS Cut Line= 4
      2242796.58     13273384.96      2243080.84     13272631.94
      2243395.03     13272103.31      2243579.52     13271963.69
#Sta/Elev= 30
  4001.5  264.32  4095.7  259.17  4170.5  256.71  4187.6  254.73  4217.1  253.93
  4729.2  232.03  4814.1   229.7  4909.6   228.7    4917  227.84  4946.6  227.69
  4952.4   226.6  4983.6  226.73  4989.4   225.6  4995.4  223.12  4998.2  222.62
  5001.4  223.12    5005  226.83  5020.6   229.3  5047.9  227.46  5114.8  228.18
  5244.6  232.38  5340.1  236.94  5435.7  243.08  5449.8  243.31  5456.5  244.32
  5477.3  244.94  5512.7  247.81  5556.4  249.21  5562.7  250.15  5652.7  254.37
#Mann= 4 ,-1 , 0
  4001.5     .05       0  4217.1      .1       0  4995.4     .07       0
  5001.4      .1       0
Bank Sta=4983.6,5005
XS Rating Curve= 0 ,0
Exp/Cntr=0.3,0.1

Type RM Length L Ch R = 1 ,5234    ,649,649,649
BEGIN DESCRIPTION:
UNT025 IN SPCR 11.0
END DESCRIPTION:
XS GIS Cut Line= 4
      2243070.85     13273484.76      2243395.03     13273040.89
      2243604.49     13272402.54      2243629.31     13272020.23
#Sta/Elev= 30
  3919.6   265.1  4052.7  257.56  4073.6  255.41  4088.2  255.49  4102.8  253.91
  4144.6  252.64  4224.2   247.6  4330.8  242.82  4351.6  241.62  4360.1  240.17
  4374.8  240.64  4505.1  234.04  4694.5  228.21  4873.4  226.44    4926  225.03
  4968.1  226.32  4979.5  225.55  4996.7  222.42  4999.5  221.92  5002.7  222.42
  5006.1  224.26  5020.8  224.65  5031.3  223.71  5037.9  224.83    5075  225.84
    5126  229.76  5367.2  243.15  5422.4  247.36  5517.6  251.51  5524.2  252.64
#Mann= 3 ,-1 , 0
  3919.6      .1       0  4996.7     .07       0  5002.7      .1       0
Bank Sta=4979.5,5006.1
XS Rating Curve= 0 ,0
Exp/Cntr=0.3,0.1

Type RM Length L Ch R = 1 ,4585    ,516,516,516
BEGIN DESCRIPTION:
UNT025 IN SPCR 10.0
END DESCRIPTION:
XS GIS Cut Line= 3
      2243437.73     13273396.84      2244187.72     13272596.85
       2244437.7     13272396.87
#Sta/Elev= 30
  3888.6  250.63  3909.8  248.87    3945  247.85  3952.3  247.01  3973.3   246.7
  4051.5     243  4100.8  241.84  4143.3  239.75  4369.5  233.64  4461.8  229.33
  4539.5  227.66  4624.4  224.46  4706.5  222.51  4744.6  221.97  4872.1  222.94
  4992.4  221.84  5003.8  220.94  5006.5  220.44  5009.8  220.94  5013.2  221.62
  5035.6  221.58  5049.2   223.2  5085.2  225.78  5184.5  232.46  5198.9  232.95
  5213.3  234.54  5227.7  234.99  5259.7  237.56  5277.3  239.33  5305.3  240.93
#Mann= 5 ,-1 , 0
  3888.6     .05       0  4706.5      .1       0  5003.8     .07       0
  5009.8      .1       0  5259.7     .05       0
Bank Sta=4992.4,5013.2
XS Rating Curve= 0 ,0
Exp/Cntr=0.3,0.1