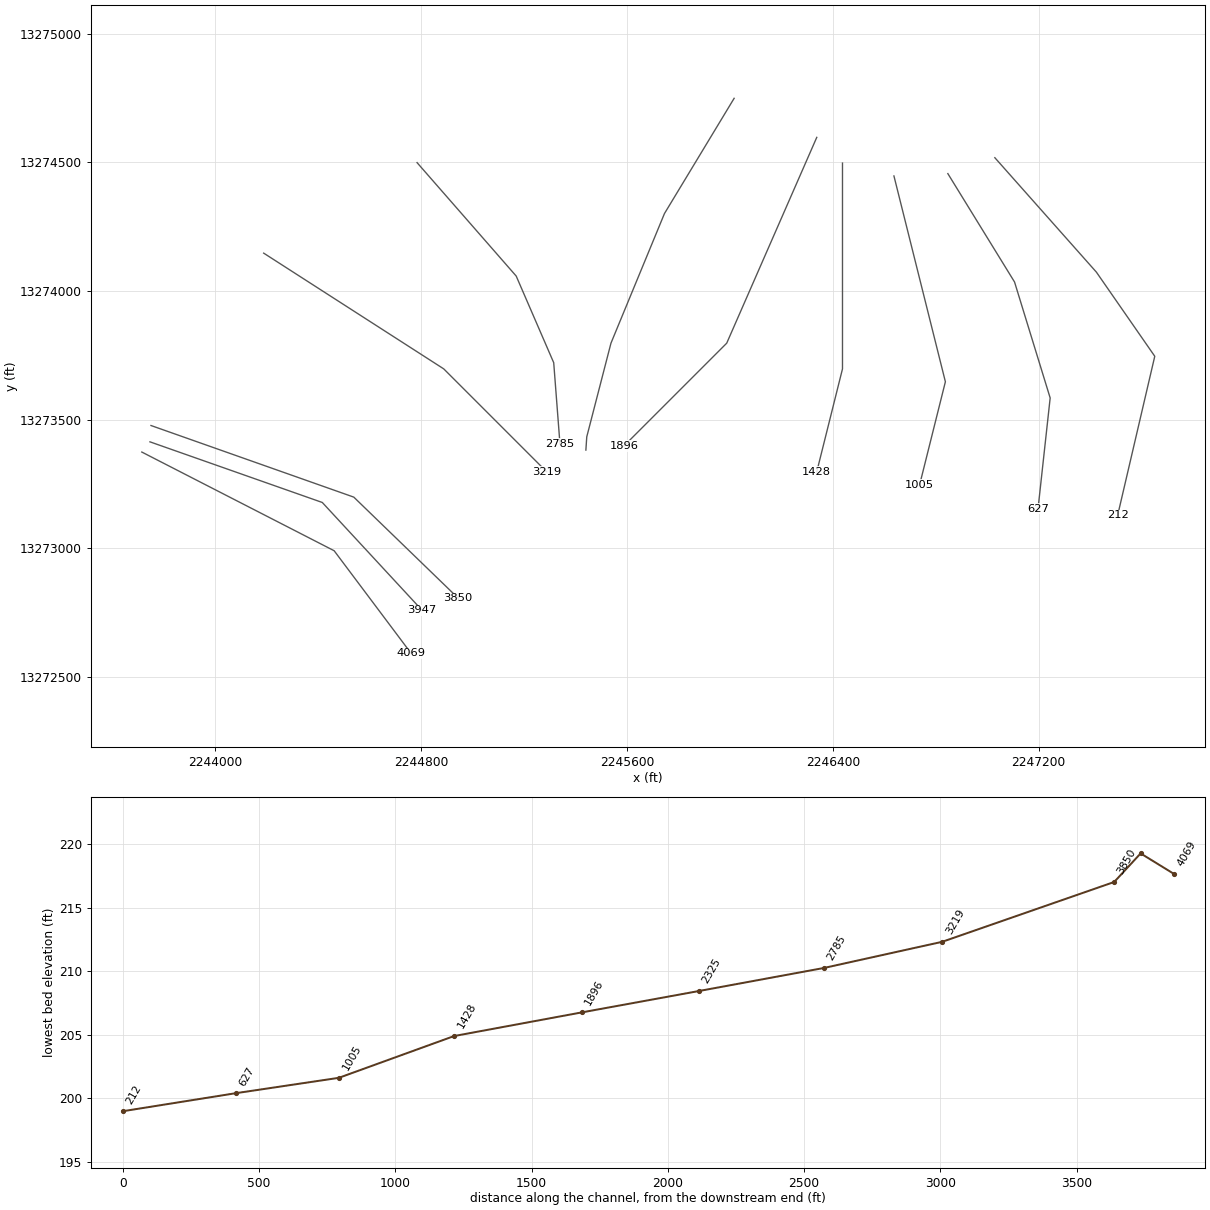
HEC-RAS study UNT025 IN SPCR.prj: UNT025 IN SPCR Base Level Engineering

--- UNT025 IN SPCR.g01 (geometry) --- (continued)

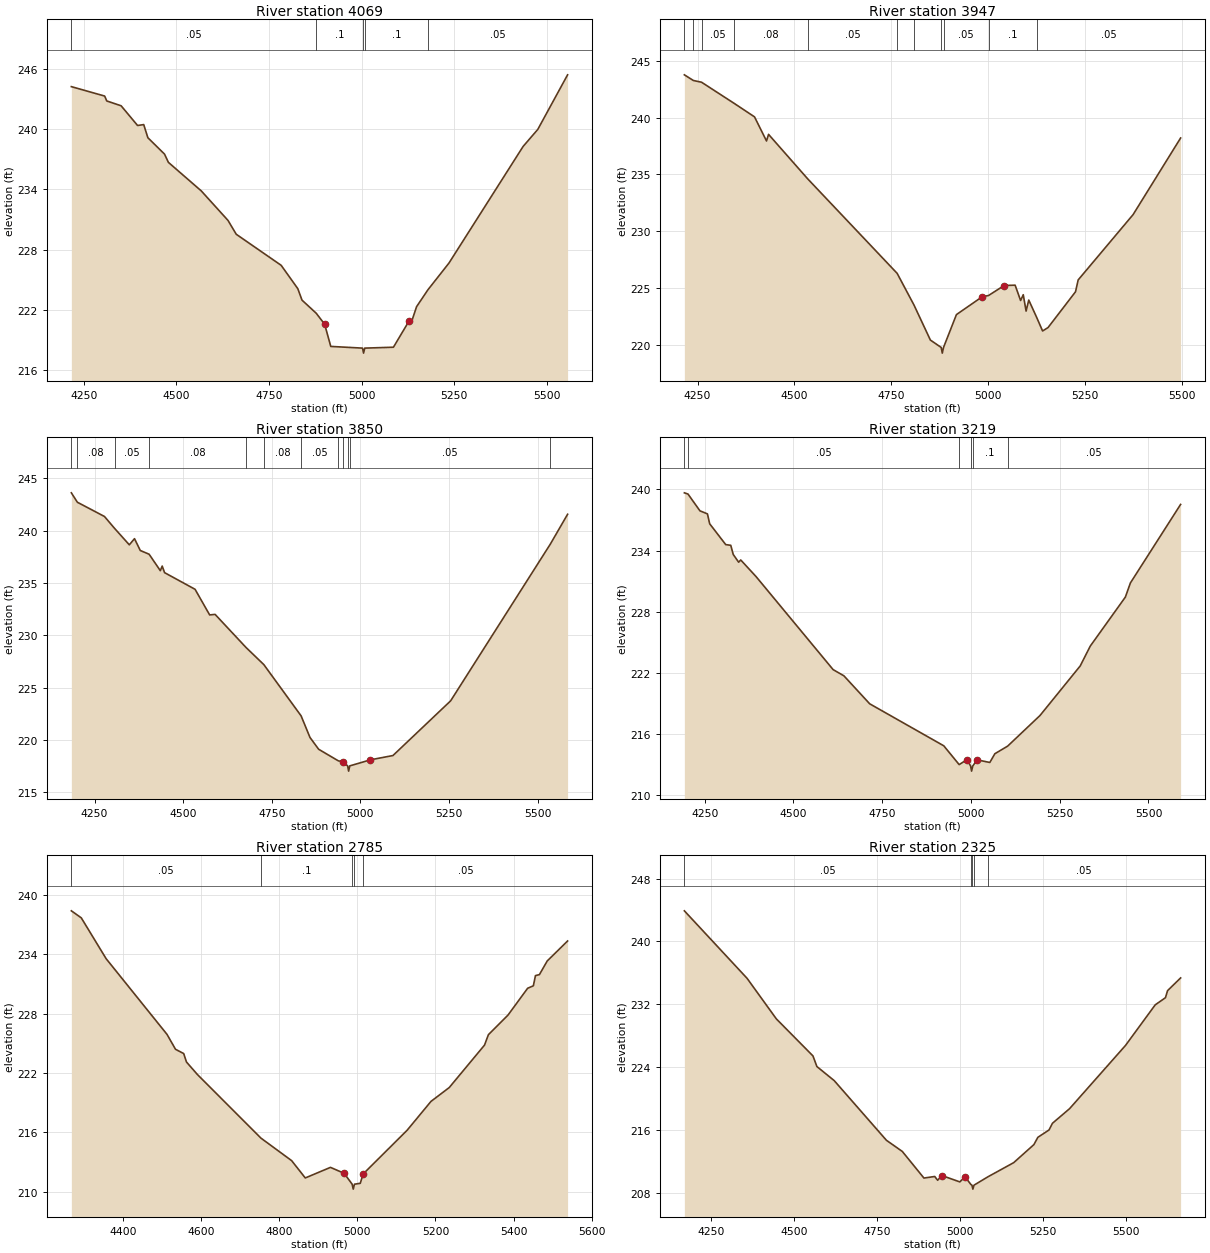
Type RM Length L Ch R = 1 ,4069    ,122,122,122
BEGIN DESCRIPTION:
UNT025 IN SPCR 9.0
END DESCRIPTION:
XS GIS Cut Line= 3
      2243713.99     13273373.58      2244461.66     13272989.94
      2244760.97     13272590.86
#Sta/Elev= 30
  4216.4  244.27  4306.3  243.33    4312  242.84  4350.7  242.36  4395.1  240.39
  4411.7  240.48  4422.9  239.17  4467.9  237.53  4478.3  236.71    4567  233.86
  4639.2  230.91  4661.4  229.53  4782.6  226.43  4827.5   224.1  4838.9  222.95
  4877.3  221.64  4899.9  220.55  4916.5  218.33  5002.2  218.16    5005  217.66
  5008.2  218.16  5085.6  218.25  5127.3  220.84  5135.6  220.91  5148.1   222.3
  5178.6  223.98  5235.6  226.66  5435.6   238.3  5475.2     240  5555.6  245.45
#Mann= 5 ,-1 , 0
  4216.4     .05       0  4877.3      .1       0  5002.2     .07       0
  5008.2      .1       0  5178.6     .05       0
Bank Sta=4899.9,5127.3
XS Rating Curve= 0 ,0
Exp/Cntr=0.3,0.1

Type RM Length L Ch R = 1 ,3947    ,97,97,97
BEGIN DESCRIPTION:
Mapping XS d7946cd1
END DESCRIPTION:
XS GIS Cut Line= 3
      2243745.65     13273413.27      2244415.59     13273177.54
      2244803.16     13272758.76
#Sta/Elev= 30
  4216.1  243.76  4239.4  243.26  4260.4  243.11  4344.6  241.25  4397.2  240.06
  4428.1  237.94  4433.4  238.52  4534.6   234.6  4765.3  226.29  4808.8   223.5
  4851.1  220.42    4879  219.77  4881.8  219.27    4885  219.77  4918.3  222.66
  4984.8  224.23  5001.1  224.34  5041.5  225.22  5069.8  225.25    5084   223.9
  5090.8  224.41  5098.1  222.97    5105  223.94  5125.2  222.43  5140.7  221.22
  5154.8  221.52  5225.7  224.67  5232.5  225.71  5374.3  231.46  5496.9   238.2
#Mann= 11 ,-1 , 0
  4216.1     .05       0  4239.4     .08       0  4260.4     .05       0
  4344.6     .08       0  4534.6     .05       0  4765.3     .08       0
  4808.8     .05       0    4879     .04       0    4885     .05       0
  5001.1      .1       0  5125.2     .05       0
Bank Sta=4984.8,5041.5
XS Rating Curve= 0 ,0
Exp/Cntr=0.3,0.1

Type RM Length L Ch R = 1 ,3850    ,631,631,631
BEGIN DESCRIPTION:
Mapping XS 55341cc1
END DESCRIPTION:
XS GIS Cut Line= 3
      2243749.64     13273476.73      2244537.99     13273198.38
      2244943.49     13272805.87
#Sta/Elev= 30
  4184.5  243.62  4201.5  242.72  4277.9  241.36  4306.8  240.21  4348.1  238.65
  4362.7  239.24    4379  238.11    4404  237.75  4435.6  236.18  4440.9  236.62
  4447.6  235.99  4533.6   234.4  4574.8  231.95  4590.2     232  4677.4  228.84
  4727.7   227.2  4832.9   222.3  4857.9  220.24  4882.4  219.11  4938.1     218
  4950.7  217.93  4950.8  217.93  4964.2  217.52    4967  217.02  4970.2  217.52
  5028.5   218.1  5092.1  218.51  5254.9  223.74  5536.4  238.73  5584.9  241.57
#Mann= 12 ,-1 , 0
  4184.5     .05       0  4201.5     .08       0  4306.8     .05       0
    4404     .08       0  4677.4     .05       0  4727.7     .08       0
  4832.9     .05       0  4938.1      .1       0  4950.8     .05       0
  4964.2     .04       0  4970.2     .05       0  5536.4      .1       0
Bank Sta=4950.7,5028.5
XS Rating Curve= 0 ,0
Exp/Cntr=0.3,0.1

Type RM Length L Ch R = 1 ,3219    ,434,434,434
BEGIN DESCRIPTION:
UNT025 IN SPCR 7.0
END DESCRIPTION:
XS GIS Cut Line= 3
      2244187.76     13274146.83      2244887.72     13273696.85
      2245287.71     13273296.86
#Sta/Elev= 30
  4192.8  239.67    4203  239.55  4236.7   237.9  4257.8   237.6  4264.1  236.63
  4309.3  234.58  4323.5  234.51  4330.5  233.61  4345.7  232.85  4351.6  233.07
  4394.9  231.43  4611.8  222.29  4642.2  221.68  4714.8  218.93  4923.5   214.8
  4966.9  212.95  4989.3  213.45  4999.1  212.81  5001.9  212.31  5005.1  212.81
  5017.3  213.42  5053.2  213.16  5067.4  214.02  5103.5  214.77  5194.6  217.78
  5307.8  222.65  5336.1   224.6    5435  229.42  5449.2  230.81  5590.6  238.53
#Mann= 6 ,-1 , 0
  4192.8      .1       0    4203     .05       0  4966.9      .1       0
  4999.1     .07       0  5005.1      .1       0  5103.5     .05       0
Bank Sta=4989.3,5017.3
XS Rating Curve= 0 ,0
Exp/Cntr=0.3,0.1

Type RM Length L Ch R = 1 ,2785    ,460,460,460
BEGIN DESCRIPTION:
UNT025 IN SPCR 6.0
END DESCRIPTION:
XS GIS Cut Line= 4
      2244783.94     13274498.69      2245169.33     13274057.75
      2245315.17     13273720.94      2245339.48     13273404.92
#Sta/Elev= 30
  4268.6  238.39    4294  237.68  4357.6  233.55  4513.3   225.9  4535.1  224.39
    4556  223.96  4563.2   223.1  4591.1  221.84  4753.6  215.41  4832.2  213.13
  4867.1  211.38  4931.5  212.45  4966.5  211.85    4987  210.75  4989.8  210.25
    4993  210.75  5007.8  210.84  5015.1  211.78  5127.6   216.2  5188.7  219.12
  5235.4  220.52  5325.6  224.81  5335.7  225.87  5385.8  227.85    5436  230.56
  5450.6  230.81    5456  231.84  5466.1  231.94  5486.1  233.32  5538.2  235.34
#Mann= 5 ,-1 , 0
  4268.6     .05       0  4753.6      .1       0    4987     .07       0
    4993      .1       0  5015.1     .05       0
Bank Sta=4966.5,5015.1
XS Rating Curve= 0 ,0
Exp/Cntr=0.3,0.1

Type RM Length L Ch R = 1 ,2325    ,429,429,429
BEGIN DESCRIPTION:
UNT025 IN SPCR 5.0
END DESCRIPTION:
XS GIS Cut Line= 5
      2246016.54      13274748.7      2245745.72      13274300.8
      2245537.72     13273796.85      2245443.64     13273432.75
       2245440.2     13273381.22
#Sta/Elev= 30
  4168.6  243.89  4357.7  235.29    4446  230.12  4556.4   225.4  4568.2  224.05
  4620.6  222.25    4778  214.65  4825.8  213.23    4891  209.84  4923.5  210.04
  4932.3  209.56  4945.1  210.16  4999.2  209.35  5014.9     210  5032.4  209.03
  5035.8  208.93  5038.6  208.43  5041.8  208.93  5083.9     210  5161.5   211.8
  5222.5   214.1  5234.5  215.03  5268.2  215.97  5278.5  216.82  5330.1  218.68
  5498.8  226.74  5588.4  231.91  5619.2  232.82  5625.6  233.72  5664.9  235.34
#Mann= 5 ,-1 , 0
  4168.6     .05       0  5032.4      .1       0  5035.8     .03       0
  5041.8      .1       0  5083.9     .05       0
Bank Sta=4945.1,5014.9
XS Rating Curve= 0 ,0
Exp/Cntr=0.3,0.1

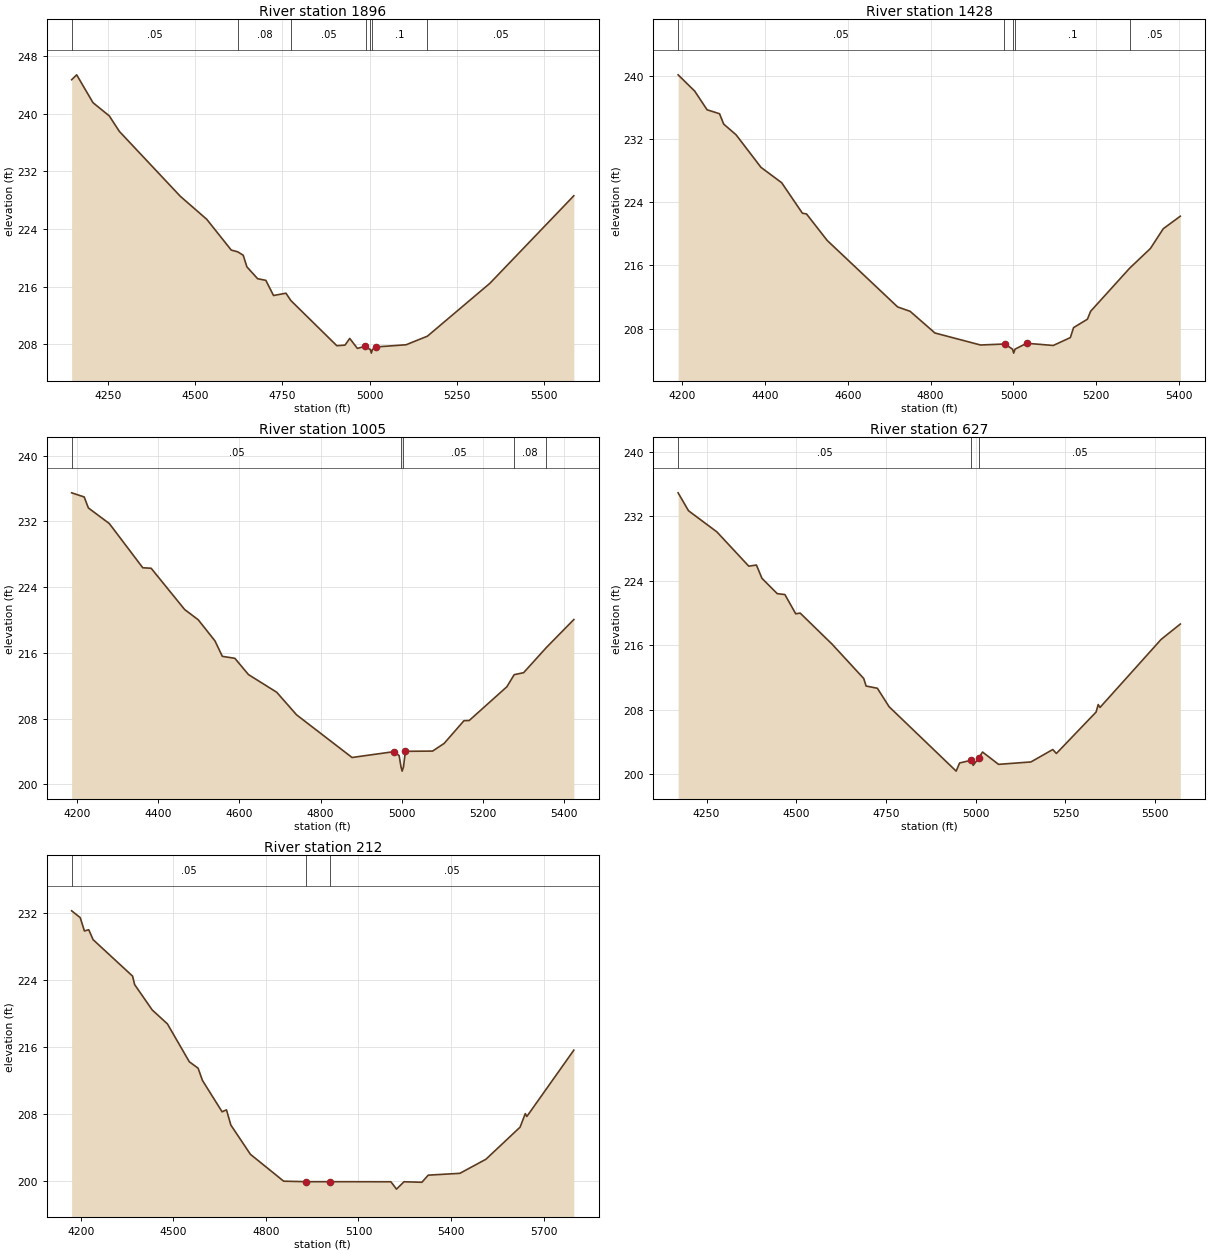
Type RM Length L Ch R = 1 ,1896    ,468,468,468
BEGIN DESCRIPTION:
UNT025 IN SPCR 4.0
END DESCRIPTION:
XS GIS Cut Line= 3
      2246337.73     13274596.87      2245987.72     13273796.85
      2245587.73     13273396.86
#Sta/Elev= 30
  4146.5  244.71  4160.9  245.39  4207.7  241.52  4254.5  239.68  4283.3  237.53
    4458  228.52  4533.6  225.33  4603.8  221.06  4622.6  220.81  4638.1  220.34
  4648.6  218.73  4679.4  217.08  4702.8  216.86    4725  214.75  4760.5  215.07
  4774.6  214.05  4906.3  207.78  4929.7  207.86  4943.3  208.79  4965.1  207.41
  4987.4  207.69  4989.5   207.6  5002.3  207.25  5005.1  206.75  5008.3  207.25
  5019.7  207.61  5104.6  207.91  5165.8   209.1    5345  216.45  5585.4   228.6
#Mann= 7 ,-1 , 0
  4146.5     .05       0  4622.6     .08       0  4774.6     .05       0
  4989.5      .1       0  5002.3     .07       0  5008.3      .1       0
  5165.8     .05       0
Bank Sta=4987.4,5019.7
XS Rating Curve= 0 ,0
Exp/Cntr=0.3,0.1

Type RM Length L Ch R = 1 ,1428    ,423,423,423
BEGIN DESCRIPTION:
UNT025 IN SPCR 3.0
END DESCRIPTION:
XS GIS Cut Line= 3
      2246437.72     13274496.85      2246437.72     13273696.85
      2246337.72     13273296.86
#Sta/Elev= 30
  4190.4  240.15  4230.4  238.09  4260.4  235.72  4290.4  235.22  4300.4  233.91
  4330.4  232.55  4390.4  228.43  4440.4  226.48  4490.4  222.62  4500.4  222.52
  4550.4  219.16  4720.4  210.74  4750.4  210.19  4810.4  207.44  4920.4  205.92
  4976.4  206.04  4980.4     206  4997.7  205.39  5000.5  204.89  5003.7  205.39
  5031.6  206.14    5096  205.86  5137.3  206.86    5145  208.12  5178.5  209.19
  5186.2  210.19  5280.4  215.65  5330.6  218.15  5361.5  220.65  5402.7  222.24
#Mann= 5 ,-1 , 0
  4190.4     .05       0  4976.4      .1       0  4997.7     .07       0
  5003.7      .1       0  5280.4     .05       0
Bank Sta=4980.4,5031.6
XS Rating Curve= 0 ,0
Exp/Cntr=0.3,0.1

Type RM Length L Ch R = 1 ,1005    ,378,378,378
BEGIN DESCRIPTION:
UNT025 IN SPCR 2.0
END DESCRIPTION:
XS GIS Cut Line= 3
      2246637.72     13274446.84      2246837.72     13273646.85
      2246737.72     13273246.87
#Sta/Elev= 30
  4186.7  235.47  4217.6  234.97  4227.9  233.63  4279.5  231.73  4361.9  226.35
  4382.5  226.29    4465  221.27  4498.5  220.02  4539.7  217.45  4557.8  215.57
  4588.7  215.33  4622.2  213.35  4691.8   211.2  4740.7  208.45  4877.3  203.26
  4980.4  203.97  4993.3  203.49    4998   202.1  5000.7   201.6    5004   202.1
  5008.7  204.01  5075.7  204.04  5104.1  204.97    5153  207.74  5165.9  207.76
  5258.7  211.87  5276.7  213.34  5299.9  213.58  5355.7  216.63  5423.6  220.05
#Mann= 5 ,-1 , 0
  4186.7     .05       0    4998     .03       0    5004     .05       0
  5276.7     .08       0  5355.7     .05       0
Bank Sta=4980.4,5008.7
XS Rating Curve= 0 ,0
Exp/Cntr=0.3,0.1

Type RM Length L Ch R = 1 ,627     ,415,415,415
BEGIN DESCRIPTION:
Mapping XS 181e66e4
END DESCRIPTION:
XS GIS Cut Line= 4
      2246847.29     13274455.92      2247106.56     13274034.61
      2247245.04     13273583.81       2247197.9     13273153.67
#Sta/Elev= 30
  4170.9  234.92  4199.8   232.7    4279  230.07  4367.8  225.82  4389.1  225.96
  4404.5  224.31  4447.1  222.41  4468.3   222.3  4498.6  219.91  4510.9     220
  4599.7  216.15    4688  211.88  4694.6  210.95    4726  210.67  4758.7  208.38
  4945.5  200.39    4955   201.4  4987.5  201.74  4992.9  201.11  5008.5     202
  5018.9  202.76  5063.6  201.23  5153.8  201.53  5214.6  203.07  5224.7  202.58
  5335.3  207.72  5341.2  208.65  5346.2  208.29  5516.4  216.73  5569.9  218.64
#Mann= 3 , 0 , 0
  4170.9     .05       0  4987.5     .03       0  5008.5     .05       0
Bank Sta=4987.5,5008.5
XS Rating Curve= 0 ,0
Exp/Cntr=0.3,0.1

Type RM Length L Ch R = 1 ,212     ,0,0,0
BEGIN DESCRIPTION:
UNT025 IN SPCR 1.0
END DESCRIPTION:
XS GIS Cut Line= 4
      2247029.97      13274517.8      2247424.77     13274072.91
      2247651.65     13273745.86      2247507.27     13273127.12
#Sta/Elev= 30
  4170.1  232.25  4197.9  231.44  4211.5  229.84  4225.5  229.99  4239.7   228.8
  4367.7  224.44  4374.3  223.43  4431.2   220.4  4480.6  218.73  4551.6   214.2
  4580.1  213.43  4594.3  211.96  4657.9  208.22  4672.1  208.45  4686.3  206.63
  4749.8  203.13  4857.5  199.92  4930.5  199.86  5008.3  199.86  5205.2  199.85
  5223.3  198.97  5247.7  199.85  5305.7  199.79  5326.2  200.64  5428.9  200.86
  5513.2  202.54    5624  206.38  5640.9     208    5646  207.66  5798.3  215.59
#Mann= 3 , 0 , 0
  4170.1     .05       0  4930.5     .03       0  5008.3     .05       0
Bank Sta=4930.5,5008.3
XS Rating Curve= 0 ,0
Exp/Cntr=0.3,0.1

Chan Stop Cuts=-1
Use User Specified Reach Order=0
Composite Channel Slope=5