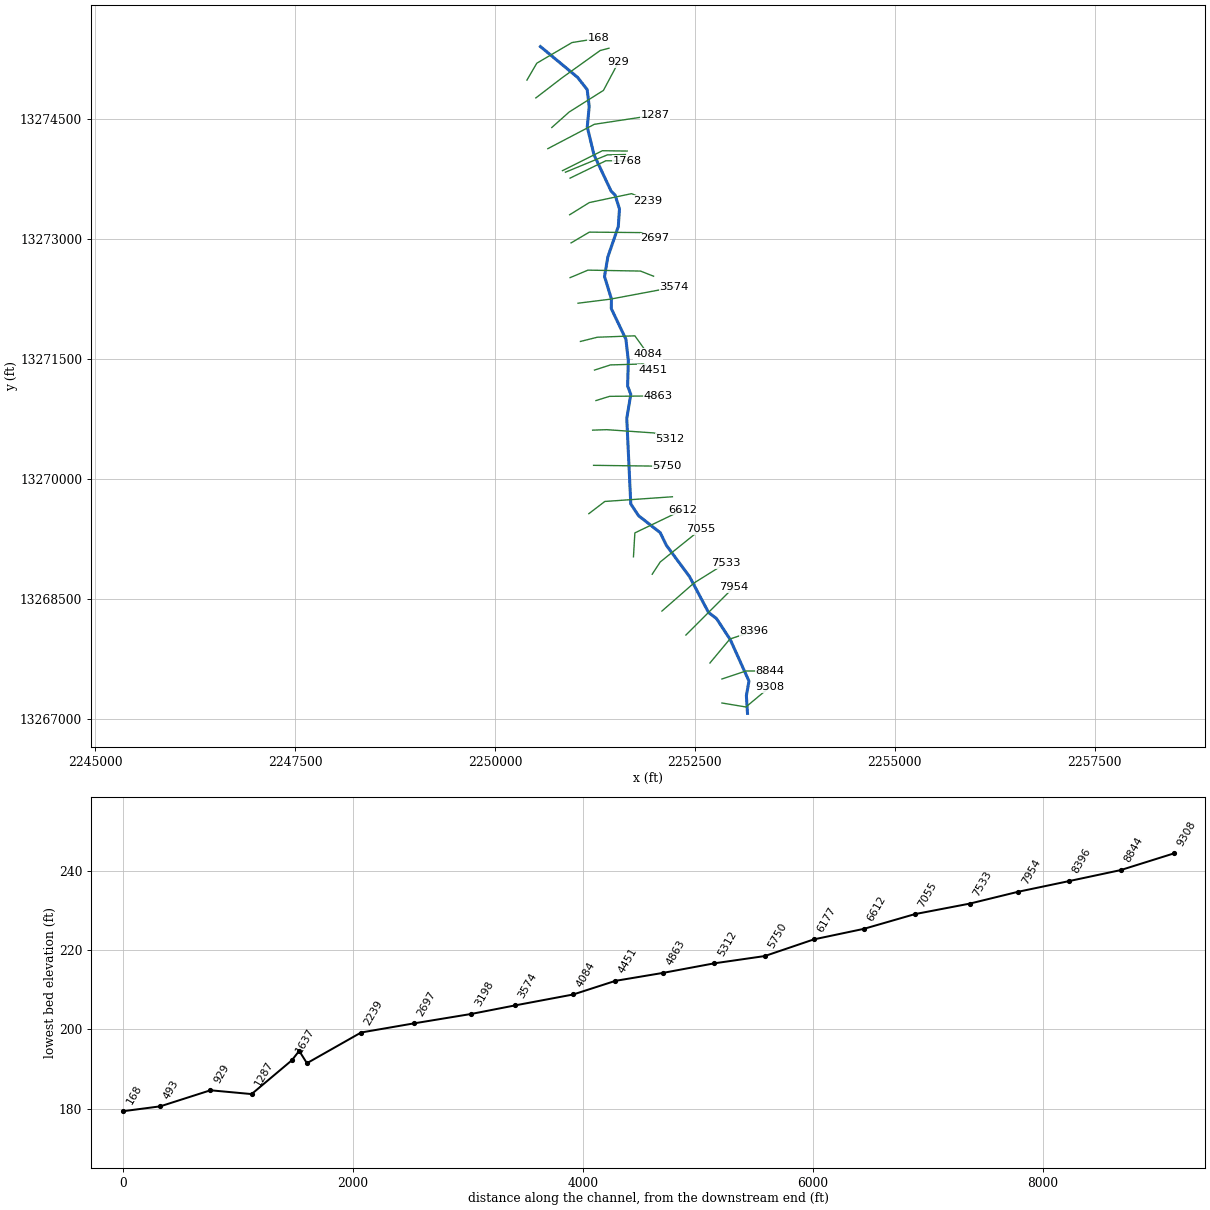
--- UNT026 IN SPCR.prj (project) ---

Proj Title=UNT026 IN SPCR Base Level Engineering
Current Plan=p01
Default Exp/Contr=0.3,0.1
English Units
Geom File=g01
Flow File=f01
Plan File=p01
BEGIN DESCRIPTION:
UNT026 IN SPCR
END DESCRIPTION:

--- UNT026 IN SPCR.p01 (plan) ---

Plan Title=Multiple Run
Short Identifier=Multiple
Geom File=g01
Flow File=f01
Subcritical Flow
K Sum by GR= 0
Std Step Tol= 0.01
Critical Tol= 0.01
Num of Std Step Trials= 20
Max Error Tol= 0.3
Flow Tol Ratio= 0.001
Split Flow NTrial= 30
Split Flow Tol= 0.02
Split Flow Ratio= 0.02
Log Output Level= 0
Friction Slope Method= 1
Unsteady Friction Slope Method= 2
Unsteady Bridges Friction Slope Method= 1
Parabolic Critical Depth
Global Vel Dist=  1 , 1 , 1
Global Log Level= 0
CheckData=True
Encroach Param= -1, 0, 0, 0
BEGIN DESCRIPTION:
Multiple Run
END DESCRIPTION:

--- UNT026 IN SPCR.f01 (steady flow) ---

Flow Title=Multiple
Number of Profiles=7
Profile Names=10-year,25-year,50-year,1pct_min,100-year,1pct_plu,500-year
River Rch & RM= UNT026 IN SPCR,Reach-1,9308
     226     315     390     356     481     650     741
River Rch & RM= UNT026 IN SPCR,Reach-1,7533
     389     558     703     651     881    1191    1404
River Rch & RM= UNT026 IN SPCR,Reach-1,3574
     476     689     874     814    1100    1488    1774
Boundary for River Rch & Prof#=UNT026 IN SPCR,Reach-1,1
Up Type=0
Dn Type=3
Dn Slope=0.005
Boundary for River Rch & Prof#=UNT026 IN SPCR,Reach-1,2
Up Type=0
Dn Type=3
Dn Slope=0.005
Boundary for River Rch & Prof#=UNT026 IN SPCR,Reach-1,3
Up Type=0
Dn Type=3
Dn Slope=0.005
Boundary for River Rch & Prof#=UNT026 IN SPCR,Reach-1,4
Up Type=0
Dn Type=3
Dn Slope=0.005
Boundary for River Rch & Prof#=UNT026 IN SPCR,Reach-1,5
Up Type=0
Dn Type=3
Dn Slope=0.005
Boundary for River Rch & Prof#=UNT026 IN SPCR,Reach-1,6
Up Type=0
Dn Type=3
Dn Slope=0.005
Boundary for River Rch & Prof#=UNT026 IN SPCR,Reach-1,7
Up Type=0
Dn Type=3
Dn Slope=0.005

--- UNT026 IN SPCR.g01 (geometry) ---

Geom Title=Existing Conditions

River Reach=UNT026 IN SPCR,Reach-1
Reach XY= 30
      2253157.72     13267066.85      2253143.66     13267287.06
      2253176.01     13267471.02      2252942.24     13267989.36
      2252769.53     13268253.13      2252670.74     13268328.51
      2252432.14     13268777.86      2252143.08     13269168.49
      2252066.11     13269326.88      2251794.14     13269540.00
      2251697.72     13269686.85      2251647.54     13270756.80
      2251698.15     13271056.88      2251658.07     13271161.06
      2251667.34     13271476.66      2251636.87     13271746.37
      2251454.34     13272129.09      2251455.51     13272250.82
      2251369.19     13272531.98      2251411.05     13272775.50
      2251541.75     13273156.79      2251556.35     13273376.65
      2251501.65     13273549.31      2251451.83     13273599.14
      2251237.70     13274053.03      2251153.49     13274401.99
      2251177.75     13274658.42      2251152.33     13274869.22
      2251031.30     13275022.74      2250567.72     13275406.85

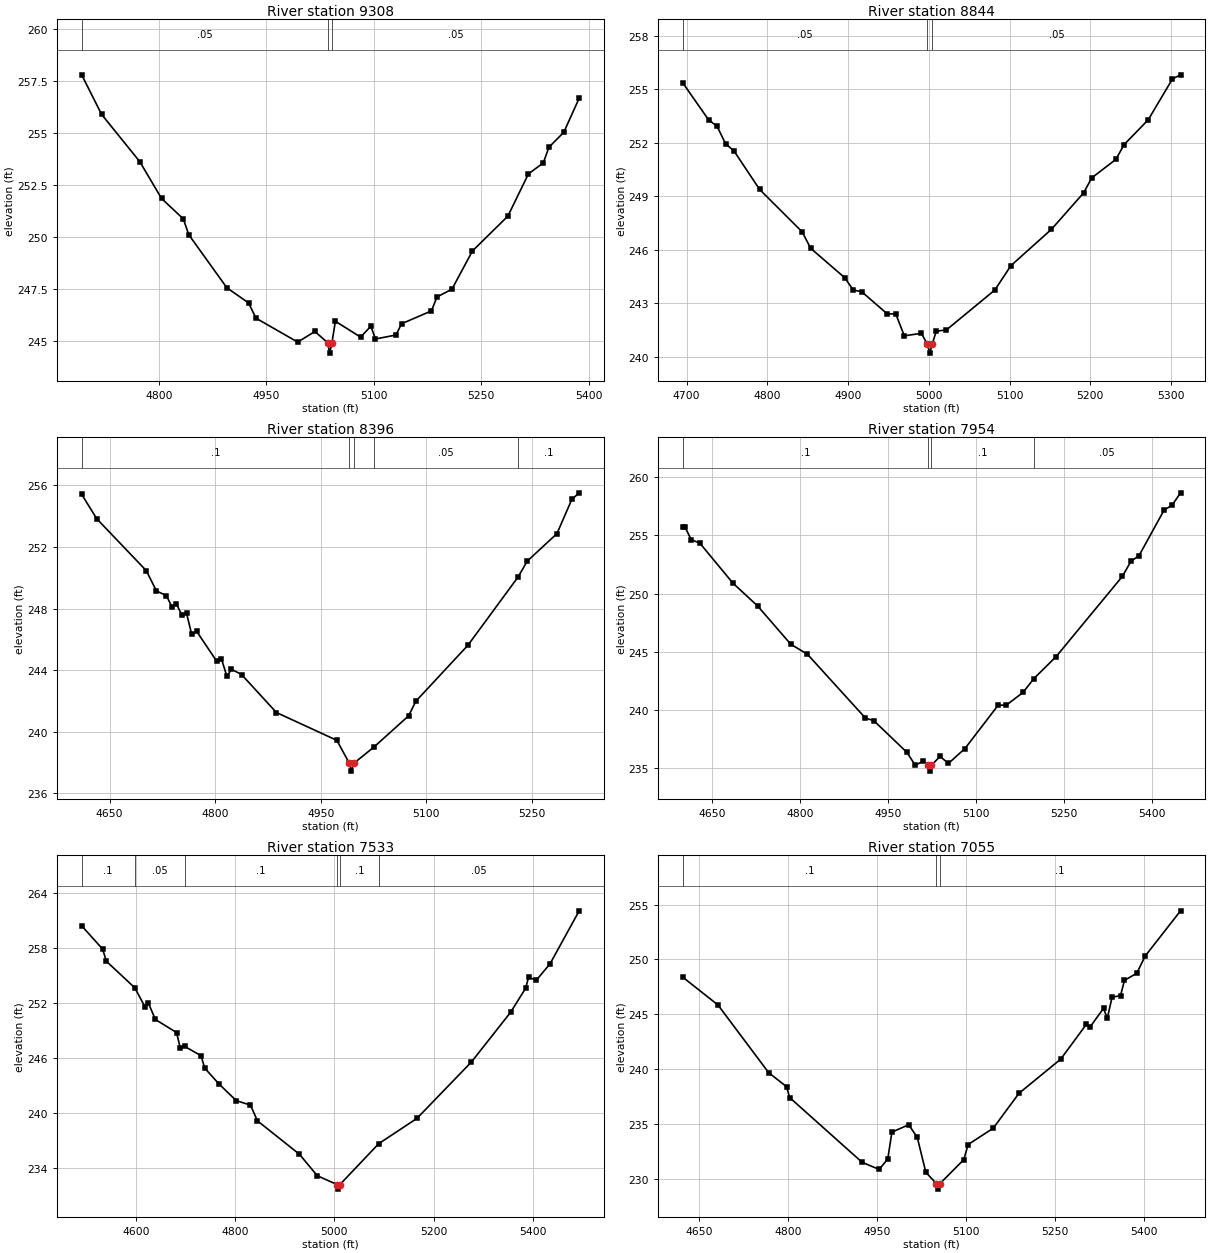
Type RM Length L Ch R = 1,9308,464,464,464
BEGIN DESCRIPTION:
UNT026 IN SPCR 21.0
END DESCRIPTION:
XS GIS Cut Line= 3
      2252837.76     13267196.85      2253137.72     13267146.85
      2253437.71     13267396.85
#Sta/Elev= 30
  4692.3  257.79  4720.1  255.89  4773.4  253.62  4803.8  251.85  4834.2  250.87
  4841.8  250.11  4895.0  247.56  4925.4  246.83  4935.6  246.10  4993.9  244.95
  5017.9  245.46  5035.7  244.92  5038.5  244.42  5041.7  244.92  5046.5  245.95
  5081.7  245.19  5096.0  245.71  5102.5  245.10  5131.1  245.29  5138.9  245.83
  5180.6  246.45  5188.4  247.12  5209.2  247.49  5237.9  249.33  5287.3  251.00
  5316.0  253.03  5336.8  253.56  5344.6  254.31  5365.4  255.03  5386.9  256.67
#Mann=3,-1,0
  4692.3    0.05       0  5035.7   0.035       0  5041.7    0.05       0
Bank Sta=5035.7,5041.7
Exp/Cntr=0.3,0.1

Type RM Length L Ch R = 1,8844,448,448,448
BEGIN DESCRIPTION:
UNT026 IN SPCR 20.0
END DESCRIPTION:
XS GIS Cut Line= 3
      2252837.70     13267496.85      2253137.72     13267596.85
      2253437.68     13267596.85
#Sta/Elev= 30
  4695.6  255.34  4727.2  253.29  4737.8  252.92  4748.3  251.95  4758.9  251.53
  4790.5  249.38  4843.2  247.00  4853.7  246.08  4895.9  244.43  4906.4  243.74
  4917.0  243.64  4948.6  242.40  4959.1  242.40  4969.7  241.17  4990.8  241.31
  4998.3  240.70  5001.1  240.20  5004.3  240.70  5009.2  241.43  5021.8  241.50
  5081.8  243.74  5101.8  245.11  5151.8  247.14  5191.8  249.19  5201.8  250.03
  5231.8  251.07  5241.8  251.89  5271.8  253.29  5301.8  255.58  5311.8  255.81
#Mann=3,-1,0
  4695.6    0.05       0  4998.3   0.035       0  5004.3    0.05       0
Bank Sta=4998.3,5004.3
Exp/Cntr=0.3,0.1

Type RM Length L Ch R = 1,8396,442,442,442
BEGIN DESCRIPTION:
UNT026 IN SPCR 19.0
END DESCRIPTION:
XS GIS Cut Line= 3
      2252687.72     13267696.86      2252937.72     13267996.85
      2253237.69     13268096.84
#Sta/Elev= 30
  4610.4  255.42  4631.9  253.83  4702.2  250.46  4716.5  249.15  4730.8  248.83
  4738.6  248.11  4745.1  248.29  4752.9  247.56  4759.4  247.69  4766.6  246.33
  4773.8  246.51  4802.4  244.56  4808.9  244.73  4816.7  243.59  4823.2  244.05
  4837.5  243.71  4887.0  241.24  4972.9  239.43  4990.7  237.93  4993.5  237.43
  4996.7  237.93  5025.4  238.99  5074.7  241.02  5085.2  241.98  5159.0  245.61
  5230.3  250.05  5243.3  251.08  5285.5  252.87  5306.6  255.09  5317.1  255.52
#Mann=5,-1,0
  4610.4     0.1       0  4990.7    0.07       0  4996.7     0.1       0
  5025.4    0.05       0  5230.3     0.1       0
Bank Sta=4990.7,4996.7
Exp/Cntr=0.3,0.1

Type RM Length L Ch R = 1,7954,421,421,421
BEGIN DESCRIPTION:
UNT026 IN SPCR 18.0
END DESCRIPTION:
XS GIS Cut Line= 3
      2252387.71     13268046.84      2252687.72     13268346.85
      2252987.69     13268646.82
#Sta/Elev= 30
  4600.4  255.70  4604.0  255.70  4614.6  254.61  4628.7  254.36  4685.3  250.91
  4727.7  248.93  4784.3  245.64  4812.5  244.79  4911.5  239.30  4925.7  239.08
  4982.3  236.35  4996.4  235.25  5010.5  235.61  5018.1  235.24  5020.9  234.74
  5024.1  235.24  5038.8  236.01  5053.0  235.40  5081.2  236.68  5137.8  240.40
  5152.0  240.42  5180.2  241.50  5198.9  242.70  5236.8  244.59  5349.9  251.49
  5364.1  252.76  5378.2  253.27  5420.7  257.16  5434.8  257.62  5448.9  258.66
#Mann=4,-1,0
  4600.4     0.1       0  5018.1    0.07       0  5024.1     0.1       0
  5198.9    0.05       0
Bank Sta=5018.1,5024.1
Exp/Cntr=0.3,0.1

Type RM Length L Ch R = 1,7533,478,478,478
BEGIN DESCRIPTION:
UNT026 IN SPCR 17.0
END DESCRIPTION:
XS GIS Cut Line= 3
      2252087.71     13268346.84      2252487.72     13268696.85
      2252887.70     13268946.84
#Sta/Elev= 30
  4490.4  260.42  4532.7  257.88  4540.2  256.56  4597.5  253.67  4618.1  251.59
  4624.7  252.03  4639.0  250.22  4681.7  248.80  4689.3  247.10  4698.4  247.28
  4731.0  246.28  4738.6  244.92  4767.1  243.21  4802.2  241.38  4830.7  240.90
  4844.9  239.18  4929.4  235.55  4965.5  233.21  5005.2  232.25  5007.9  231.75
  5011.2  232.25  5089.4  236.70  5166.4  239.45  5276.1  245.58  5355.1  250.99
  5385.7  253.63  5391.6  254.84  5407.0  254.49  5434.7  256.27  5493.6  262.05
#Mann=6,-1,0
  4490.4     0.1       0  4597.5    0.05       0  4698.4     0.1       0
  5005.2    0.07       0  5011.2     0.1       0  5089.4    0.05       0
Bank Sta=5005.2,5011.2
Exp/Cntr=0.3,0.1

Type RM Length L Ch R = 1,7055,443,443,443
BEGIN DESCRIPTION:
UNT026 IN SPCR 16.0
END DESCRIPTION:
XS GIS Cut Line= 3
      2251966.01     13268807.66      2252065.79     13268960.26
      2252576.40     13269371.10
#Sta/Elev= 30
  4623.3  248.37  4682.1  245.86  4767.6  239.69  4797.8  238.41  4802.8  237.43
  4924.9  231.53  4953.7  230.88  4968.1  231.85  4975.0  234.28  5003.3  234.95
  5017.7  233.81  5032.1  230.63  5049.9  229.59  5052.7  229.09  5055.9  229.59
  5096.1  231.78  5103.3  233.15  5145.7  234.64  5188.9  237.81  5259.3  240.93
  5302.5  244.10  5308.9  243.87  5331.3  245.55  5337.7  244.65  5345.7  246.56
  5360.0  246.71  5366.5  248.09  5387.3  248.75  5401.7  250.33  5461.0  254.43
#Mann=3,-1,0
  4623.3     0.1       0  5049.9    0.07       0  5055.9     0.1       0
Bank Sta=5049.9,5055.9
Exp/Cntr=0.3,0.1

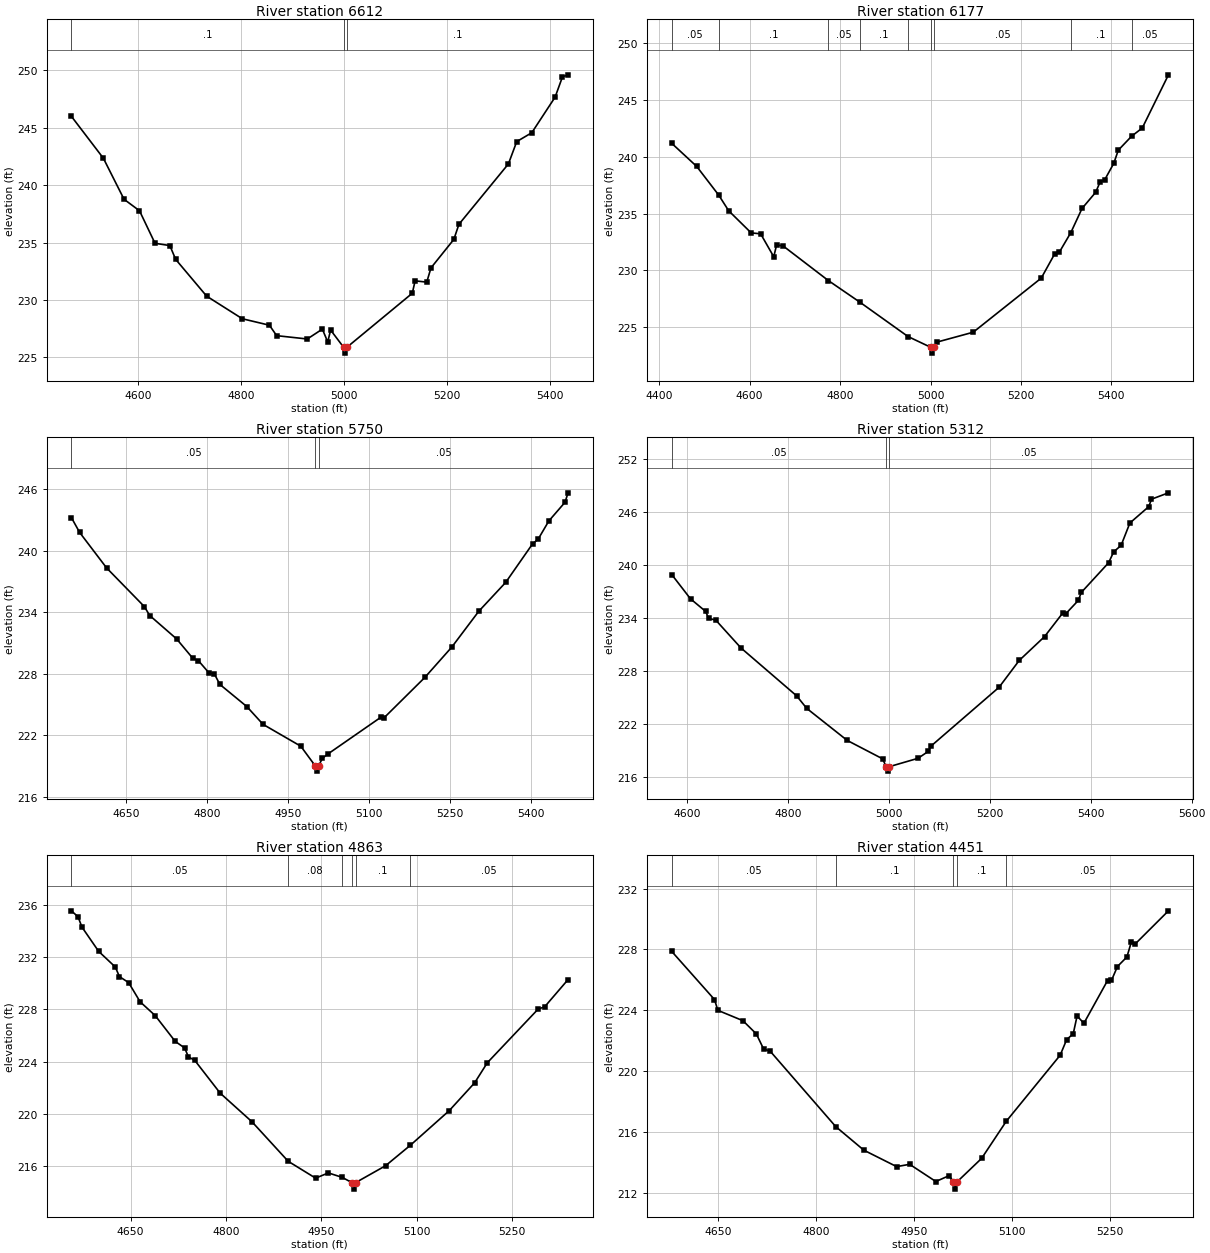
Type RM Length L Ch R = 1,6612,435,435,435
BEGIN DESCRIPTION:
UNT026 IN SPCR 15.0
END DESCRIPTION:
XS GIS Cut Line= 3
      2251731.27     13269024.85      2251748.88     13269324.13
      2252347.49     13269611.70
#Sta/Elev= 30
  4470.4  245.99  4532.5  242.34  4572.6  238.77  4602.6  237.77  4632.7  234.94
  4661.5  234.74  4672.8  233.54  4732.9  230.34  4802.2  228.37  4854.7  227.81
  4868.8  226.90  4928.2  226.61  4957.5  227.47  4967.9  226.35  4973.5  227.39
  4998.9  225.88  5001.6  225.38  5004.9  225.88  5132.0  230.59  5137.5  231.67
  5160.1  231.56  5168.3  232.80  5212.7  235.28  5222.5  236.59  5318.6  241.85
  5334.7  243.79  5363.9  244.56  5409.2  247.66  5423.5  249.43  5434.3  249.60
#Mann=3,-1,0
  4470.4     0.1       0  4998.9    0.07       0  5004.9     0.1       0
Bank Sta=4998.9,5004.9
Exp/Cntr=0.3,0.1

Type RM Length L Ch R = 1,6177,427,427,427
BEGIN DESCRIPTION:
UNT026 IN SPCR 14.0
END DESCRIPTION:
XS GIS Cut Line= 3
      2251173.73     13269564.74      2251373.27     13269717.33
      2252218.34     13269776.02
#Sta/Elev= 30
  4427.8  241.18  4482.9  239.15  4531.7  236.62  4553.6  235.25  4603.4  233.30
  4624.3  233.22  4653.3  231.20  4659.6  232.24  4674.1  232.15  4773.9  229.11
  4843.9  227.20  4950.2  224.18  5001.2  223.22  5004.0  222.72  5007.2  223.22
  5014.2  223.69  5094.4  224.56  5244.8  229.32  5274.9  231.48  5284.9  231.61
  5310.3  233.33  5335.0  235.45  5365.1  236.87  5375.1  237.79  5385.1  237.97
  5405.2  239.42  5415.2  240.58  5444.7  241.81  5468.2  242.53  5526.1  247.21
#Mann=9,-1,0
  4427.8    0.05       0  4531.7     0.1       0  4773.9    0.05       0
  4843.9     0.1       0  4950.2    0.05       0  5001.2    0.03       0
  5007.2    0.05       0  5310.3     0.1       0  5444.7    0.05       0
Bank Sta=5001.2,5007.2
Exp/Cntr=0.3,0.1

Type RM Length L Ch R = 1,5750,438,438,438
BEGIN DESCRIPTION:
UNT026 IN SPCR 13.0
END DESCRIPTION:
XS GIS Cut Line= 2
      2251232.39     13270169.23      2252153.32     13270157.50
#Sta/Elev= 30
  4548.4  243.23  4563.7  241.78  4613.7  238.32  4683.7  234.55  4693.7  233.68
  4743.7  231.39  4773.7  229.50  4783.7  229.29  4803.7  228.08  4813.8  227.96
  4823.8  226.96  4873.8  224.80  4903.8  223.07  4973.8  220.94  5000.8  219.01
  5003.5  218.51  5006.8  219.01  5013.8  219.76  5023.8  220.17  5123.1  223.79
  5128.1  223.70  5203.8  227.64  5253.8  230.60  5303.8  234.09  5353.8  236.91
  5403.8  240.68  5413.8  241.11  5433.8  242.90  5463.8  244.72  5469.4  245.64
#Mann=3,-1,0
  4548.4    0.05       0  5000.8    0.03       0  5006.8    0.05       0
Bank Sta=5000.8,5006.8
Exp/Cntr=0.3,0.1

Type RM Length L Ch R = 1,5312,449,449,449
BEGIN DESCRIPTION:
UNT026 IN SPCR 12.0
END DESCRIPTION:
XS GIS Cut Line= 4
      2251220.68     13270609.39      2251396.75     13270615.26
      2251989.50     13270574.17      2252189.07     13270497.87
#Sta/Elev= 30
  4570.0  238.89  4607.1  236.15  4637.1  234.73  4643.1  233.93  4657.1  233.75
  4707.1  230.60  4817.3  225.19  4837.4  223.77  4917.6  220.15  4987.7  218.07
  4994.7  217.18  4997.5  216.68  5000.7  217.18  5057.9  218.13  5077.9  218.90
  5083.8  219.52  5218.3  226.15  5258.4  229.19  5308.5  231.88  5345.3  234.60
  5350.7  234.47  5375.4  235.97  5381.3  236.87  5435.5  240.23  5445.5  241.46
  5460.2  242.19  5477.6  244.72  5515.0  246.57  5520.4  247.41  5554.0  248.13
#Mann=3,-1,0
  4570.0    0.05       0  4994.7    0.03       0  5000.7    0.05       0
Bank Sta=4994.7,5000.7
Exp/Cntr=0.3,0.1

Type RM Length L Ch R = 1,4863,412,412,412
BEGIN DESCRIPTION:
UNT026 IN SPCR 11.0
END DESCRIPTION:
XS GIS Cut Line= 3
      2251261.75     13270979.11      2251431.96     13271031.94
      2252034.61     13271037.79
#Sta/Elev= 30
  4556.9  235.54  4567.3  235.09  4573.6  234.29  4599.8  232.44  4626.0  231.24
  4632.4  230.51  4646.9  230.05  4665.0  228.58  4688.8  227.52  4720.2  225.55
  4735.0  225.05  4740.9  224.37  4750.9  224.10  4790.9  221.59  4840.9  219.40
  4897.8  216.38  4940.9  215.09  4960.9  215.49  4982.7  215.15  4997.9  214.75
  5000.6  214.25  5003.9  214.75  5050.9  216.04  5089.5  217.59  5150.9  220.25
  5190.9  222.38  5210.9  223.92  5290.9  228.03  5300.9  228.19  5337.8  230.28
#Mann=6,-1,0
  4556.9    0.05       0  4897.8    0.08       0  4982.7     0.1       0
  4997.9    0.07       0  5003.9     0.1       0  5089.5    0.05       0
Bank Sta=4997.9,5003.9
Exp/Cntr=0.3,0.1

Type RM Length L Ch R = 1,4451,367,367,367
BEGIN DESCRIPTION:
UNT026 IN SPCR 10.0
END DESCRIPTION:
XS GIS Cut Line= 4
      2251244.20     13271360.60      2251443.70     13271425.14
      2251854.51     13271436.88      2251970.92     13271361.22
#Sta/Elev= 30
  4579.4  227.87  4644.7  224.71  4649.9  224.00  4688.2  223.32  4708.7  222.45
  4719.7  221.47  4730.2  221.30  4830.1  216.36  4873.1  214.81  4923.2  213.73
  4943.2  213.88  4983.2  212.75  5003.2  213.13  5010.2  212.75  5012.9  212.25
  5016.2  212.75  5053.2  214.27  5090.9  216.71  5173.3  221.05  5183.3  222.08
  5193.3  222.46  5199.2  223.63  5209.6  223.15  5245.8  225.96  5251.8  225.97
  5260.9  226.88  5275.4  227.51  5282.0  228.47  5288.0  228.36  5338.9  230.54
#Mann=5,-1,0
  4579.4    0.05       0  4830.1     0.1       0  5010.2    0.07       0
  5016.2     0.1       0  5090.9    0.05       0
Bank Sta=5010.2,5016.2
Exp/Cntr=0.3,0.1

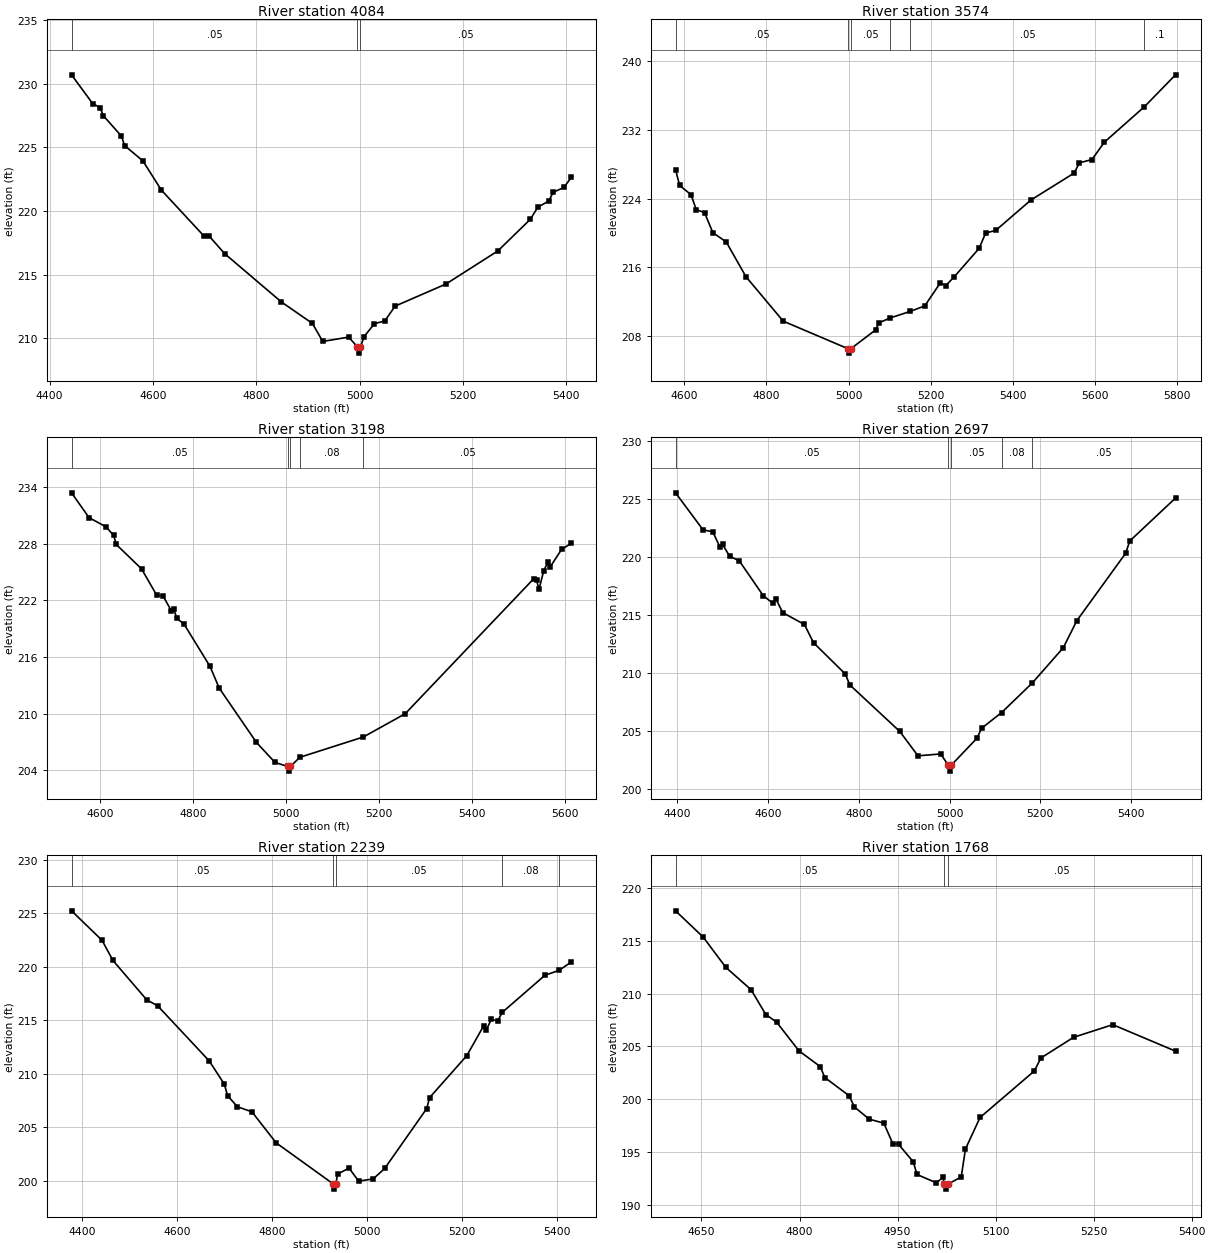
Type RM Length L Ch R = 1,4084,510,510,510
BEGIN DESCRIPTION:
UNT026 IN SPCR 9.0
END DESCRIPTION:
XS GIS Cut Line= 4
      2251068.11     13271718.59      2251279.37     13271771.40
      2251748.88     13271789.01      2251912.35     13271561.31
#Sta/Elev= 30
  4442.4  230.72  4483.2  228.46  4497.9  228.13  4503.8  227.51  4539.1  225.89
  4545.1  225.15  4580.4  223.95  4616.4  221.64  4698.5  218.04  4708.5  218.04
  4738.6  216.65  4848.6  212.84  4908.7  211.15  4928.7  209.73  4978.7  210.07
  4995.8  209.31  4998.5  208.81  5001.8  209.31  5008.8  210.11  5028.8  211.13
  5048.8  211.34  5068.8  212.51  5167.2  214.25  5267.8  216.86  5330.5  219.34
  5345.2  220.30  5366.5  220.79  5374.7  221.47  5395.6  221.85  5410.3  222.67
#Mann=3,-1,0
  4442.4    0.05       0  4995.8   0.035       0  5001.8    0.05       0
Bank Sta=4995.8,5001.8
Exp/Cntr=0.3,0.1

Type RM Length L Ch R = 1,3574,376,376,376
BEGIN DESCRIPTION:
UNT026 IN SPCR 8.0
END DESCRIPTION:
XS GIS Cut Line= 3
      2251037.77     13272196.86      2251437.72     13272246.85
      2252237.71     13272396.85
#Sta/Elev= 30
  4578.8  227.36  4588.8  225.52  4616.5  224.45  4629.1  222.71  4649.3  222.37
  4669.5  220.04  4702.2  218.95  4750.1  214.92  4840.8  209.75  4999.2  206.53
  5002.0  206.03  5005.2  206.53  5065.8  208.73  5073.4  209.54  5101.3  210.12
  5150.7  210.89  5185.4  211.52  5223.5  214.21  5236.2  213.87  5256.6  214.87
  5317.6  218.20  5333.7  219.99  5358.3  220.30  5443.9  223.83  5549.1  226.96
  5561.8  228.15  5592.3  228.53  5622.8  230.56  5720.3  234.68  5795.8  238.38
#Mann=6,-1,0
  4578.8    0.05       0  4999.2   0.035       0  5005.2    0.05       0
  5101.3    0.08       0  5150.7    0.05       0  5720.3     0.1       0
Bank Sta=4999.2,5005.2
Exp/Cntr=0.3,0.1

Type RM Length L Ch R = 1,3198,501,501,501
BEGIN DESCRIPTION:
UNT026 IN SPCR 7.0
END DESCRIPTION:
XS GIS Cut Line= 4
      2250939.03     13272516.75      2251162.00     13272610.64
      2251819.30     13272598.90      2251983.17     13272534.52
#Sta/Elev= 30
  4538.2  233.38  4575.9  230.75  4612.7  229.77  4628.8  228.86  4634.4  227.91
  4688.7  225.33  4721.2  222.55  4734.6  222.49  4752.9  220.88  4758.4  221.05
  4764.6  220.08  4780.1  219.48  4835.9  215.01  4855.9  212.69  4935.9  206.94
  4975.9  204.82  5002.9  204.40  5005.6  203.90  5008.9  204.40  5029.6  205.37
  5166.1  207.52  5255.9  209.98  5532.5  224.29  5538.4  224.14  5543.7  223.15
  5554.0  225.15  5562.8  226.02  5568.2  225.56  5592.6  227.41  5613.6  228.04
#Mann=5,-1,0
  4538.2    0.05       0  5002.9   0.035       0  5008.9    0.05       0
  5029.6    0.08       0  5166.1    0.05       0
Bank Sta=5002.9,5008.9
Exp/Cntr=0.3,0.1

Type RM Length L Ch R = 1,2697,458,458,458
BEGIN DESCRIPTION:
UNT026 IN SPCR 6.0
END DESCRIPTION:
XS GIS Cut Line= 4
      2250950.77     13272951.05      2251179.61     13273086.01
      2251825.17     13273080.14      2252001.25     13273009.71
#Sta/Elev= 30
  4396.7  225.50  4457.2  222.31  4478.6  222.14  4494.3  220.84  4500.1  221.06
  4515.7  220.04  4537.2  219.63  4589.9  216.63  4611.4  215.97  4617.2  216.39
  4632.8  215.17  4680.5  214.15  4700.5  212.58  4770.5  209.88  4780.5  208.94
  4890.5  204.93  4930.5  202.83  4980.5  202.99  4997.5  202.01  5000.2  201.51
  5003.5  202.01  5060.5  204.35  5070.5  205.20  5114.7  206.56  5182.3  209.11
  5250.5  212.15  5280.5  214.49  5387.8  220.29  5396.9  221.35  5497.6  225.05
#Mann=5,-1,0
  4396.7    0.05       0  4997.5   0.035       0  5003.5    0.05       0
  5114.7    0.08       0  5182.3    0.05       0
Bank Sta=4997.5,5003.5
Exp/Cntr=0.3,0.1

Type RM Length L Ch R = 1,2239,471,471,471
BEGIN DESCRIPTION:
UNT026 IN SPCR 5.0
END DESCRIPTION:
XS GIS Cut Line= 4
      2250933.14     13273303.16      2251179.61     13273455.74
      2251707.79     13273567.24      2251912.95     13273479.32
#Sta/Elev= 30
  4378.1  225.21  4442.3  222.46  4465.3  220.57  4536.4  216.90  4559.8  216.32
  4668.0  211.19  4699.7  209.03  4706.9  207.93  4727.4  206.91  4758.0  206.43
  4809.1  203.53  4928.8  199.71  4931.5  199.21  4934.8  199.71  4938.3  200.60
  4962.4  201.18  4982.9  199.95  5013.5  200.17  5037.8  201.15  5126.0  206.73
  5132.2  207.76  5210.5  211.68  5246.3  214.49  5251.8  214.10  5262.1  215.07
  5275.3  214.92  5285.6  215.74  5375.1  219.19  5404.4  219.64  5431.0  220.44
#Mann=5,-1,0
  4378.1    0.05       0  4928.8   0.035       0  4934.8    0.05       0
  5285.6    0.08       0  5404.4    0.05       0
Bank Sta=4928.8,4934.8
Exp/Cntr=0.3,0.1

Type RM Length L Ch R = 1,1768,67,67,67
BEGIN DESCRIPTION:
UNT026 IN SPCR 3.0
END DESCRIPTION:
XS GIS Cut Line= 3
      2250938.64     13273761.43      2251385.73     13273978.47
      2251653.74     13273978.47
#Sta/Elev= 30
  4610.3  217.84  4652.6  215.35  4687.1  212.49  4725.9  210.36  4748.4  208.01
  4764.9  207.29  4799.1  204.57  4831.6  203.08  4838.7  202.04  4876.1  200.30
  4883.8  199.26  4906.4  198.10  4929.0  197.71  4942.8  195.76  4951.5  195.71
  4974.1  194.04  4979.7  192.85  5009.5  192.05  5019.2  192.57  5021.8  191.96
  5024.5  191.46  5027.8  191.96  5047.4  192.61  5053.9  195.26  5076.2  198.25
  5159.3  202.66  5169.3  203.89  5219.3  205.85  5279.3  207.05  5375.3  204.54
#Mann=3,-1,0
  4610.3    0.05       0  5021.8   0.035       0  5027.8    0.05       0
Bank Sta=5021.8,5027.8
Exp/Cntr=0.3,0.1

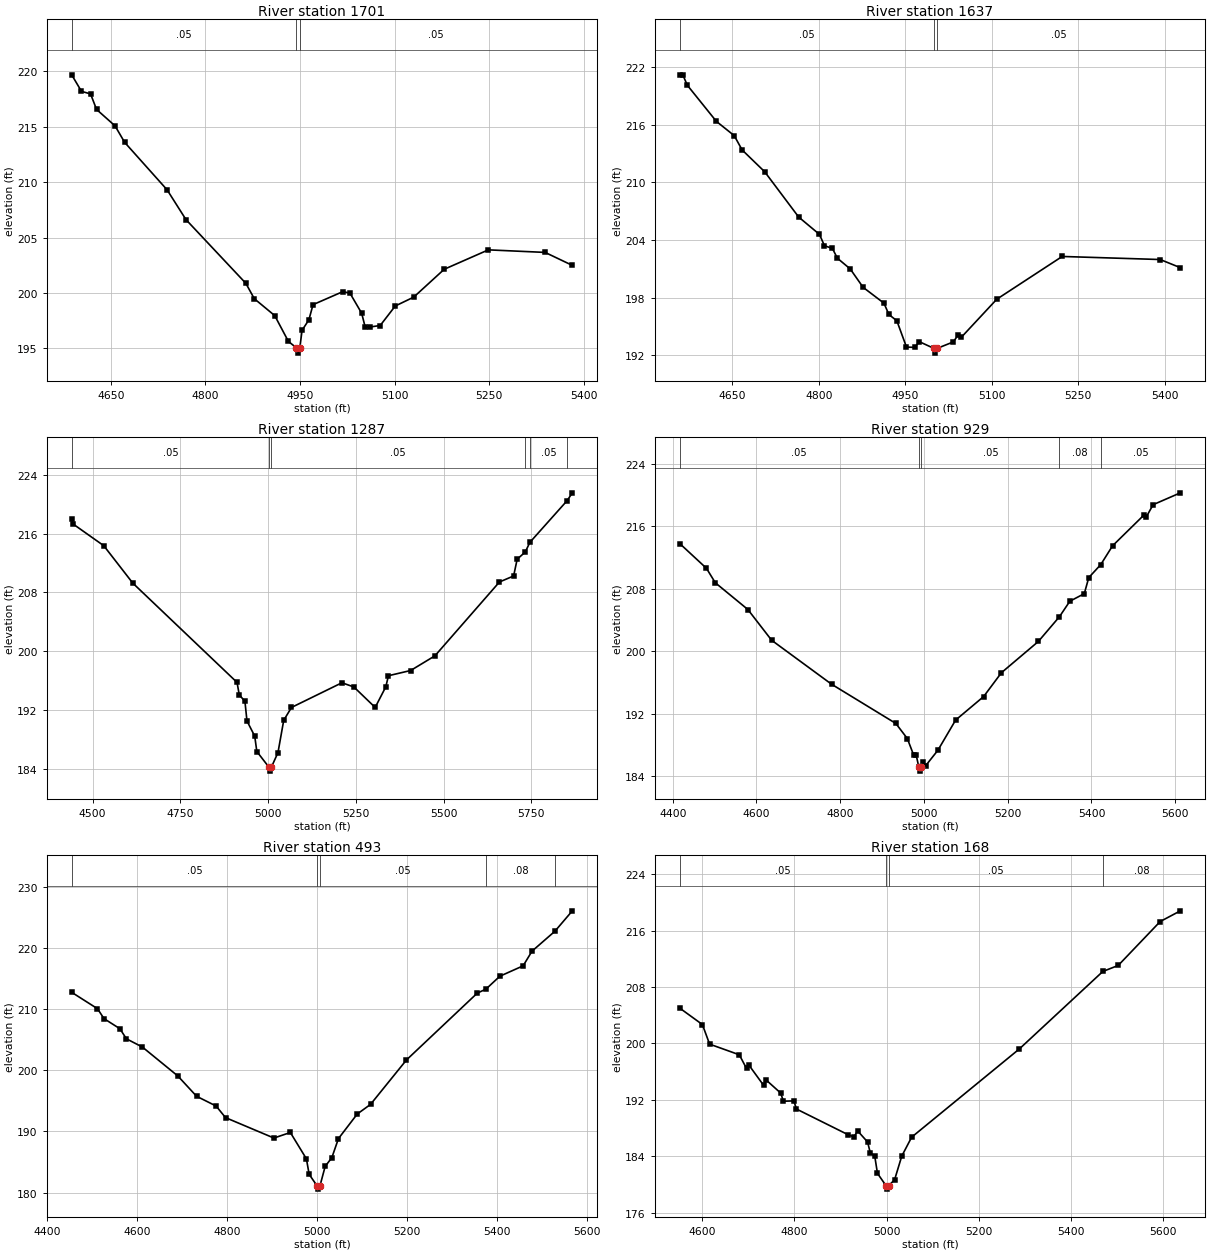
Type RM Length L Ch R = 1,1701,64,64,64
BEGIN DESCRIPTION:
Mapping XS 650c7c72
END DESCRIPTION:
XS GIS Cut Line= 3
      2250880.12     13273835.25      2251405.26     13274052.25
      2251630.91     13274056.59
#Sta/Elev= 30
  4588.0  219.67  4603.5  218.18  4617.9  217.95  4627.4  216.55  4656.7  215.07
  4672.0  213.58  4739.3  209.30  4769.3  206.61  4864.2  200.87  4877.5  199.49
  4910.0  197.96  4931.6  195.64  4943.8  195.08  4946.5  194.58  4949.8  195.08
  4953.3  196.64  4964.1  197.58  4970.7  198.95  5018.2  200.13  5029.3  199.98
  5047.8  198.18  5053.3  196.95  5061.5  196.94  5077.2  197.07  5101.1  198.83
  5130.4  199.63  5178.7  202.14  5248.7  203.89  5338.7  203.66  5381.9  202.49
#Mann=3,-1,0
  4588.0    0.05       0  4943.8   0.035       0  4949.8    0.05       0
Bank Sta=4943.8,4949.8
Exp/Cntr=0.3,0.1

Type RM Length L Ch R = 1,1637,350,350,350
BEGIN DESCRIPTION:
UNT026 IN SPCR 4.0
END DESCRIPTION:
XS GIS Cut Line= 3
      2250843.22     13273854.78      2251342.33     13274104.34
      2251652.68     13274100.00
#Sta/Elev= 30
  4558.6  221.22  4563.9  221.22  4571.8  220.13  4622.1  216.37  4653.1  214.88
  4666.8  213.39  4706.0  211.11  4764.9  206.39  4801.0  204.58  4809.6  203.40
  4823.4  203.12  4832.0  202.10  4854.3  200.98  4876.7  199.06  4912.8  197.41
  4921.4  196.23  4935.2  195.57  4951.9  192.83  4966.1  192.80  4974.3  193.39
  4999.3  192.70  5002.0  192.20  5005.3  192.70  5033.2  193.37  5041.4  194.09
  5047.0  193.85  5108.5  197.82  5222.0  202.28  5392.0  201.96  5427.0  201.11
#Mann=3,-1,0
  4558.6    0.05       0  4999.3   0.035       0  5005.3    0.05       0
Bank Sta=4999.3,5005.3
Exp/Cntr=0.3,0.1

Type RM Length L Ch R = 1,1287,358,358,358
BEGIN DESCRIPTION:
Mapping XS e432a85e
END DESCRIPTION:
XS GIS Cut Line= 3
      2250660.53     13274130.08      2251242.01     13274434.67
      2252003.10     13274549.98
#Sta/Elev= 30
  4440.4  218.04  4443.6  217.34  4531.8  214.36  4614.4  209.27  4911.4  195.75
  4917.7  194.07  4933.9  193.16  4939.7  190.50  4961.8  188.43  4967.8  186.34
  5002.9  184.17  5005.7  183.67  5008.9  184.17  5028.0  186.19  5044.4  190.59
  5066.5  192.34  5210.2  195.70  5244.2  195.13  5304.9  192.34  5335.2  195.15
  5342.7  196.66  5406.0  197.37  5475.2  199.37  5658.9  209.42  5699.3  210.24
  5709.4  212.52  5732.6  213.51  5745.5  214.81  5851.6  220.49  5866.6  221.56
#Mann=6,-1,0
  4440.4    0.05       0  5002.9   0.035       0  5008.9    0.05       0
  5732.6    0.08       0  5745.5    0.05       0  5851.6     0.1       0
Bank Sta=5002.9,5008.9
Exp/Cntr=0.3,0.1

Type RM Length L Ch R = 1,929,436,436,436
BEGIN DESCRIPTION:
UNT026 IN SPCR 2.0
END DESCRIPTION:
XS GIS Cut Line= 4
      2250710.08     13274394.71      2250927.25     13274588.41
      2251355.67     13274858.37      2251543.11     13275209.83
#Sta/Elev= 30
  4416.7  213.79  4480.5  210.62  4501.6  208.77  4579.4  205.34  4636.2  201.40
  4779.2  195.77  4932.8  190.74  4960.2  188.81  4975.5  186.67  4981.4  186.69
  4987.8  185.13  4990.5  184.63  4993.8  185.13  4996.7  185.77  5003.8  185.31
  5033.2  187.30  5075.6  191.17  5142.6  194.19  5185.0  197.24  5273.1  201.24
  5323.6  204.42  5348.4  206.40  5382.9  207.37  5393.6  209.43  5422.2  211.09
  5450.4  213.50  5525.3  217.44  5531.0  217.21  5547.3  218.77  5612.4  220.29
#Mann=5,-1,0
  4416.7    0.05       0  4987.8   0.035       0  4993.8    0.05       0
  5323.6    0.08       0  5422.2    0.05       0
Bank Sta=4987.8,4993.8
Exp/Cntr=0.3,0.1

Type RM Length L Ch R = 1,493,325,325,325
BEGIN DESCRIPTION:
Mapping XS 02c04357
END DESCRIPTION:
XS GIS Cut Line= 4
      2250510.56     13274764.47      2250839.22     13275016.83
      2251314.59     13275357.22      2251424.40     13275386.12
#Sta/Elev= 30
  4455.4  212.75  4512.7  210.07  4527.2  208.45  4562.5  206.80  4577.0  205.15
  4612.4  203.81  4691.2  199.08  4732.9  195.76  4776.4  194.16  4797.2  192.27
  4904.8  188.93  4941.3  189.84  4977.0  185.53  4983.1  183.00  5001.0  181.08
  5003.8  180.58  5007.0  181.08  5018.7  184.30  5033.5  185.72  5048.2  188.84
  5090.0  192.86  5119.5  194.43  5199.3  201.69  5356.6  212.61  5376.1  213.28
  5406.9  215.38  5458.6  217.08  5478.4  219.48  5529.2  222.73  5568.0  226.07
#Mann=5,-1,0
  4455.4    0.05       0  5001.0   0.035       0  5007.0    0.05       0
  5376.1    0.08       0  5529.2    0.05       0
Bank Sta=5001,5007
Exp/Cntr=0.3,0.1

Type RM Length L Ch R = 1,168,0,0,0
BEGIN DESCRIPTION:
UNT026 IN SPCR 1.0
END DESCRIPTION:
XS GIS Cut Line= 4
      2250399.05     13274987.46      2250522.30     13275198.76
      2250962.46     13275456.99      2251291.11     13275509.81
#Sta/Elev= 30
  4550.7  205.02  4599.9  202.69  4615.6  199.91  4680.1  198.40  4695.8  196.46
  4701.6  196.88  4733.0  194.06  4738.8  194.80  4770.0  192.97  4776.0  191.81
  4798.6  191.86  4804.4  190.70  4915.9  187.08  4929.1  186.74  4937.3  187.60
  4958.8  186.03  4964.6  184.53  4974.5  183.99  4980.3  181.58  4998.8  179.84
  5001.5  179.34  5004.8  179.84  5017.5  180.66  5033.1  184.02  5054.6  186.71
  5288.5  199.22  5470.0  210.22  5503.4  211.07  5594.6  217.30  5638.5  218.82
#Mann=4,-1,0
  4550.7    0.05       0  4998.8   0.035       0  5004.8    0.05       0
  5470.0    0.08       0
Bank Sta=4998.8,5004.8
Exp/Cntr=0.3,0.1

Chan Stop Cuts=-1