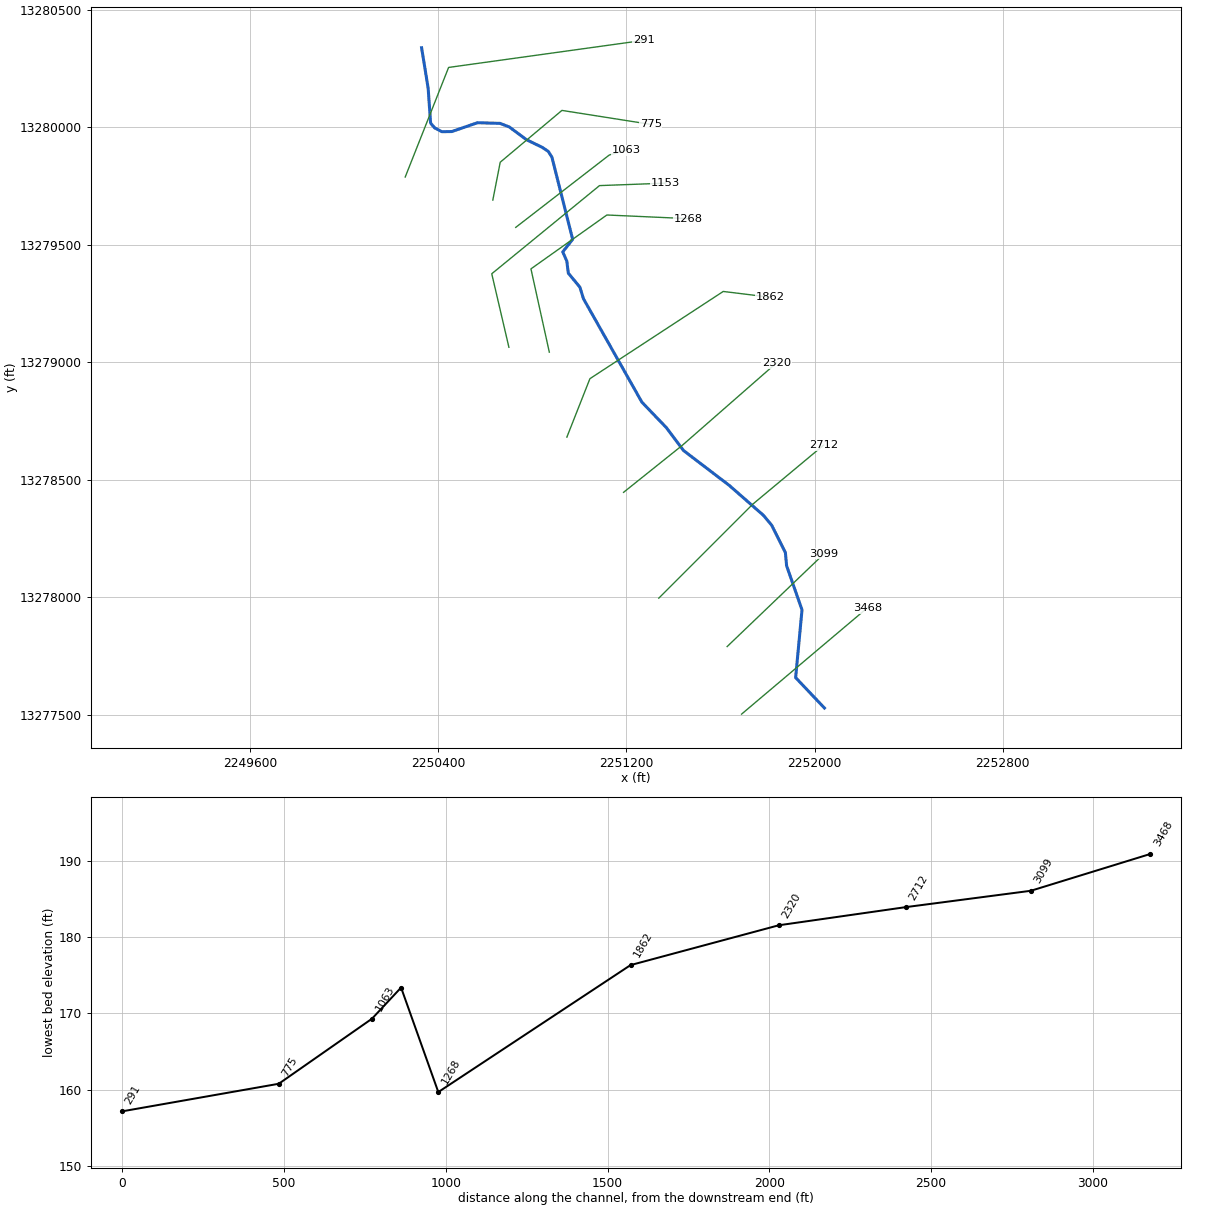
--- UNT027 IN SPCR.prj (project) ---

Proj Title=UNT027 IN SPCR Base Level Engineering
Current Plan=p01
Default Exp/Contr=0.3,0.1
English Units
Geom File=g01
Flow File=f01
Plan File=p01
BEGIN DESCRIPTION:
UNT027 IN SPCR
END DESCRIPTION:

--- UNT027 IN SPCR.p01 (plan) ---

Plan Title=Multiple Run
Short Identifier=Multiple
Geom File=g01
Flow File=f01
Subcritical Flow
K Sum by GR= 0
Std Step Tol= 0.01
Critical Tol= 0.01
Num of Std Step Trials= 20
Max Error Tol= 0.3
Flow Tol Ratio= 0.001
Split Flow NTrial= 30
Split Flow Tol= 0.02
Split Flow Ratio= 0.02
Log Output Level= 0
Friction Slope Method= 1
Unsteady Friction Slope Method= 2
Unsteady Bridges Friction Slope Method= 1
Parabolic Critical Depth
Global Vel Dist=  1 , 1 , 1
Global Log Level= 0
CheckData=True
Encroach Param= -1, 0, 0, 0
BEGIN DESCRIPTION:
Multiple Run
END DESCRIPTION:

--- UNT027 IN SPCR.f01 (steady flow) ---

Flow Title=Multiple
Number of Profiles=7
Profile Names=10-year,25-year,50-year,1pct_min,100-year,1pct_plu,500-year
River Rch & RM= UNT027 IN SPCR,Reach-1,3468
     244     342     423     387     523     707     809
Boundary for River Rch & Prof#=UNT027 IN SPCR,Reach-1,1
Up Type=0
Dn Type=3
Dn Slope=0.005
Boundary for River Rch & Prof#=UNT027 IN SPCR,Reach-1,2
Up Type=0
Dn Type=3
Dn Slope=0.005
Boundary for River Rch & Prof#=UNT027 IN SPCR,Reach-1,3
Up Type=0
Dn Type=3
Dn Slope=0.005
Boundary for River Rch & Prof#=UNT027 IN SPCR,Reach-1,4
Up Type=0
Dn Type=3
Dn Slope=0.005
Boundary for River Rch & Prof#=UNT027 IN SPCR,Reach-1,5
Up Type=0
Dn Type=3
Dn Slope=0.005
Boundary for River Rch & Prof#=UNT027 IN SPCR,Reach-1,6
Up Type=0
Dn Type=3
Dn Slope=0.005
Boundary for River Rch & Prof#=UNT027 IN SPCR,Reach-1,7
Up Type=0
Dn Type=3
Dn Slope=0.005

--- UNT027 IN SPCR.g01 (geometry) ---

Geom Title=Existing Conditions

River Reach=UNT027 IN SPCR,Reach-1
Reach XY= 30
      2252042.08     13277529.45      2251919.58     13277658.76
      2251946.66     13277946.91      2251881.15     13278134.53
      2251875.96     13278190.77      2251817.72     13278306.85
      2251782.58     13278348.97      2251637.85     13278475.84
      2251442.82     13278624.54      2251369.26     13278722.39
      2251265.74     13278830.27      2251017.17     13279270.21
      2251002.07     13279319.25      2250952.77     13279378.86
      2250946.21     13279430.66      2250929.03     13279469.40
      2250971.21     13279522.98      2250883.01     13279872.29
      2250867.74     13279896.59      2250842.04     13279913.95
      2250774.68     13279946.59      2250701.76     13280000.76
      2250662.18     13280016.04      2250566.35     13280018.82
      2250457.32     13279981.32      2250414.96     13279980.62
      2250383.71     13279997.29      2250367.04     13280017.43
      2250356.63     13280165.34      2250328.75     13280337.66

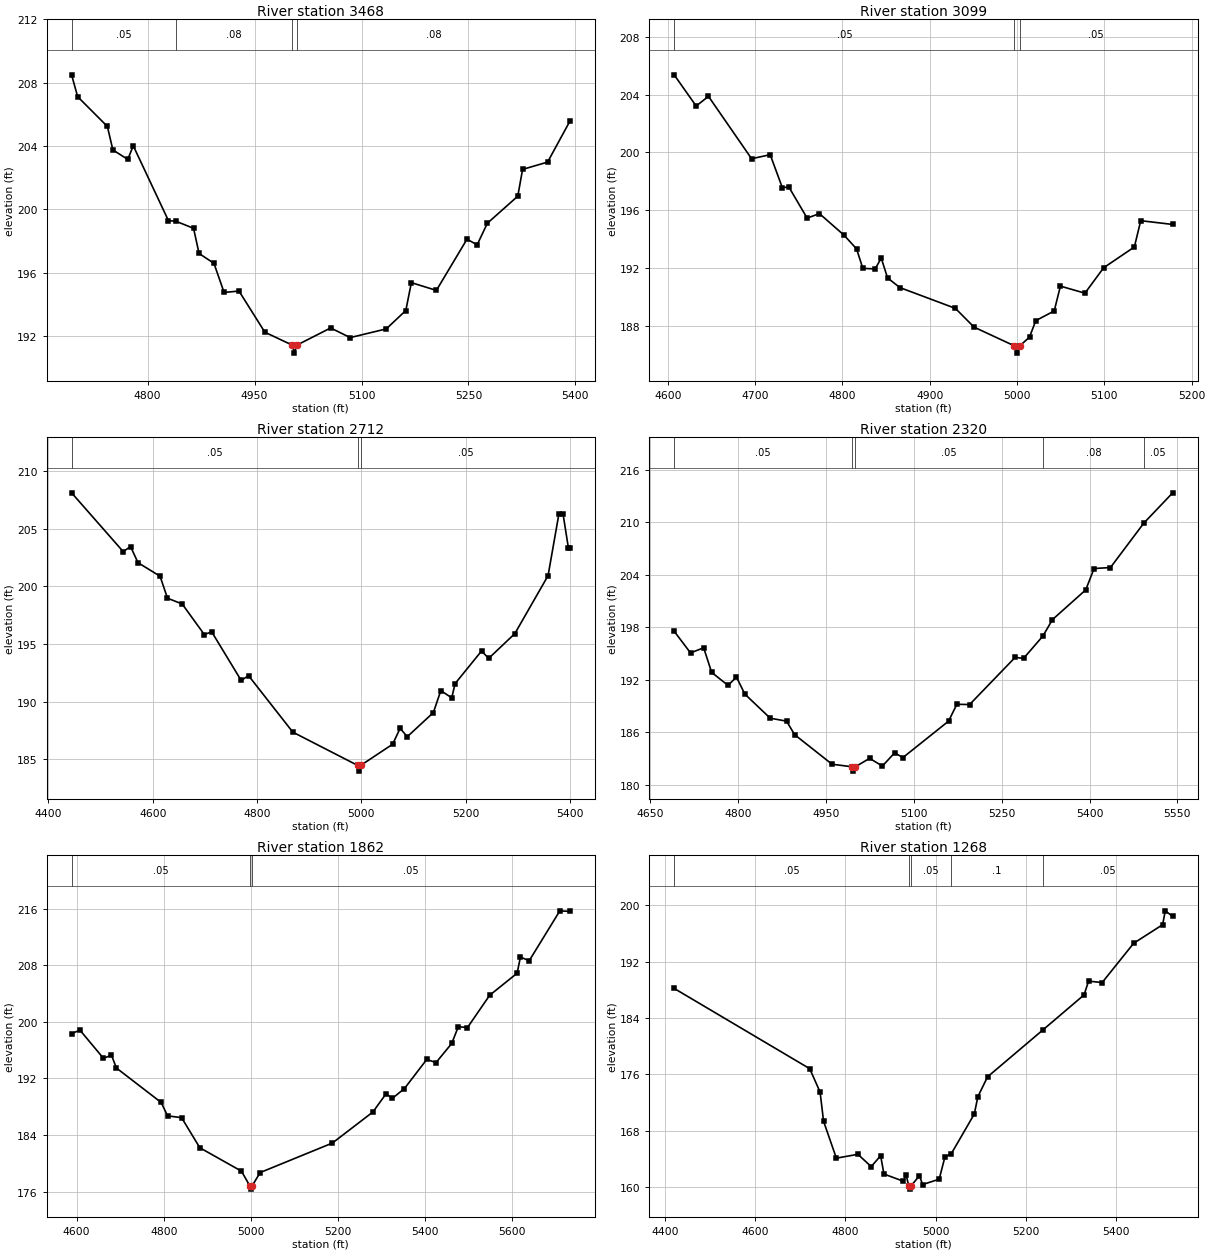
Type RM Length L Ch R = 1,3468,369,369,369
BEGIN DESCRIPTION:
UNT027 IN SPCR 4.0
END DESCRIPTION:
XS GIS Cut Line= 2
      2251689.63     13277503.50      2252223.81     13277954.79
#Sta/Elev= 30
  4693.3  208.50  4701.8  207.12  4743.5  205.24  4751.2  203.76  4772.1  203.16
  4779.8  204.02  4829.2  199.29  4839.4  199.26  4864.4  198.81  4872.1  197.22
  4893.0  196.60  4907.2  194.76  4928.1  194.85  4964.4  192.25  5003.1  191.43
  5005.8  190.93  5009.1  191.43  5056.7  192.52  5084.1  191.91  5134.7  192.46
  5162.1  193.62  5169.9  195.38  5205.0  194.89  5247.9  198.12  5262.2  197.77
  5276.5  199.13  5319.2  200.84  5325.9  202.53  5361.0  202.99  5392.6  205.60
#Mann=4,-1,0
  4693.3    0.05       0  4839.4    0.08       0  5003.1    0.07       0
  5009.1    0.08       0
Bank Sta=5003.1,5009.1
Exp/Cntr=0.3,0.1

Type RM Length L Ch R = 1,3099,387,387,387
BEGIN DESCRIPTION:
Mapping XS c8d66a75
END DESCRIPTION:
XS GIS Cut Line= 2
      2251628.28     13277790.84      2252040.62     13278185.82
#Sta/Elev= 30
  4607.2  205.37  4632.4  203.21  4646.5  203.88  4695.9  199.56  4717.2  199.84
  4731.2  197.54  4738.4  197.62  4759.5  195.45  4773.6  195.76  4801.9  194.26
  4816.1  193.32  4823.3  191.97  4837.4  191.93  4844.4  192.68  4851.6  191.31
  4865.7  190.64  4929.3  189.20  4950.7  187.90  4997.0  186.60  4999.8  186.10
  5003.0  186.60  5014.2  187.21  5021.4  188.35  5042.5  189.02  5049.6  190.74
  5077.7  190.25  5099.1  192.01  5134.3  193.45  5141.6  195.27  5178.2  195.01
#Mann=3,-1,0
  4607.2    0.05       0  4997.0    0.03       0  5003.0    0.05       0
Bank Sta=4997,5003
Exp/Cntr=0.3,0.1

Type RM Length L Ch R = 1,2712,392,392,392
BEGIN DESCRIPTION:
UNT027 IN SPCR 3.0
END DESCRIPTION:
XS GIS Cut Line= 3
      2251337.72     13277996.85      2251737.72     13278396.85
      2252037.72     13278646.85
#Sta/Elev= 30
  4444.3  208.14  4543.3  203.03  4557.4  203.47  4571.6  202.07  4614.0  200.89
  4628.2  198.98  4656.4  198.48  4698.9  195.82  4713.0  196.06  4769.6  191.83
  4783.7  192.25  4868.6  187.34  4992.9  184.45  4995.6  183.95  4998.9  184.45
  5060.1  186.29  5074.4  187.67  5088.1  186.94  5138.2  189.04  5152.5  190.95
  5173.4  190.32  5179.9  191.56  5230.6  194.39  5244.3  193.75  5294.4  195.90
  5358.2  200.94  5379.0  206.31  5386.8  206.34  5397.3  203.32  5400.5  203.32
#Mann=3,-1,0
  4444.3    0.05       0  4992.9    0.03       0  4998.9    0.05       0
Bank Sta=4992.9,4998.9
Exp/Cntr=0.3,0.1

Type RM Length L Ch R = 1,2320,458,458,458
BEGIN DESCRIPTION:
UNT027 IN SPCR 2.0
END DESCRIPTION:
XS GIS Cut Line= 3
      2251187.74     13278446.87      2251437.72     13278646.85
      2251837.69     13278996.83
#Sta/Elev= 30
  4690.5  197.56  4718.5  195.08  4740.9  195.67  4754.5  192.86  4782.5  191.37
  4796.9  192.32  4811.3  190.37  4854.6  187.62  4882.6  187.28  4896.2  185.74
  4960.2  182.36  4994.0  182.07  4996.8  181.57  5000.0  182.07  5024.4  183.03
  5046.2  182.15  5067.1  183.66  5081.3  183.12  5159.2  187.28  5173.4  189.21
  5195.2  189.18  5273.1  194.58  5287.3  194.45  5320.5  197.02  5336.7  198.89
  5393.6  202.29  5407.8  204.73  5435.8  204.84  5492.8  209.92  5542.1  213.38
#Mann=5,-1,0
  4690.5    0.05       0  4994.0    0.03       0  5000.0    0.05       0
  5320.5    0.08       0  5492.8    0.05       0
Bank Sta=4994,5000
Exp/Cntr=0.3,0.1

Type RM Length L Ch R = 1,1862,594,594,594
BEGIN DESCRIPTION:
Mapping XS acb065f5
END DESCRIPTION:
XS GIS Cut Line= 4
      2250946.64     13278681.68      2251044.64     13278930.20
      2251611.64     13279301.20      2251811.11     13279276.70
#Sta/Elev= 30
  4588.3  198.32  4607.4  198.82  4661.6  194.83  4679.9  195.28  4691.3  193.46
  4794.2  188.59  4808.8  186.70  4841.1  186.44  4883.0  182.19  4978.6  178.88
  4997.6  176.84  5000.3  176.34  5003.6  176.84  5021.6  178.68  5187.5  182.85
  5280.9  187.25  5311.2  189.84  5325.2  189.16  5353.3  190.56  5404.6  194.68
  5425.7  194.22  5461.9  196.93  5477.0  199.30  5498.1  199.18  5549.2  203.75
  5612.2  206.86  5619.8  209.15  5639.9  208.62  5710.4  215.68  5734.0  215.59
#Mann=3,-1,0
  4588.3    0.05       0  4997.6    0.03       0  5003.6    0.05       0
Bank Sta=4997.6,5003.6
Exp/Cntr=0.3,0.1

Type RM Length L Ch R = 1,1268,115,115,115
BEGIN DESCRIPTION:
Mapping XS 496d92ca
END DESCRIPTION:
XS GIS Cut Line= 4
      2250871.94     13279043.03      2250793.81     13279397.21
      2251116.73     13279626.38      2251464.21     13279610.82
#Sta/Elev= 30
  4419.8  188.20  4720.7  176.79  4743.7  173.46  4751.4  169.32  4779.8  164.07
  4827.6  164.62  4857.2  162.87  4878.1  164.42  4885.4  161.82  4928.5  160.79
  4934.7  161.69  4940.3  160.17  4943.1  159.67  4946.3  160.17  4964.2  161.59
  4971.2  160.32  5008.0  161.08  5020.8  164.25  5034.8  164.69  5086.0  170.35
  5093.9  172.82  5115.5  175.64  5237.5  182.26  5329.6  187.28  5339.6  189.24
  5369.7  189.03  5439.7  194.62  5504.0  197.26  5509.8  199.23  5526.3  198.44
#Mann=5,-1,0
  4419.8    0.05       0  4940.3    0.03       0  4946.3    0.05       0
  5034.8     0.1       0  5237.5    0.05       0
Bank Sta=4940.3,4946.3
Exp/Cntr=0.3,0.1

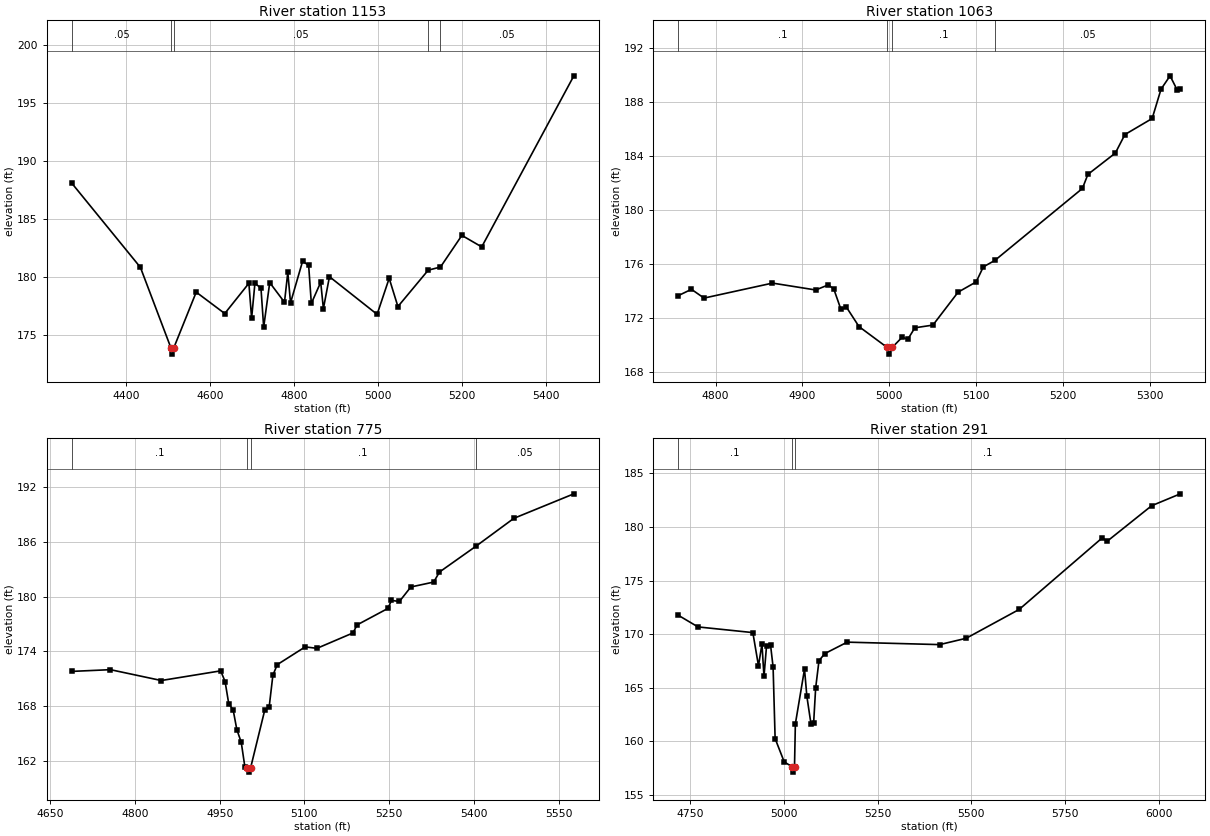
Type RM Length L Ch R = 1,1153,90,90,90
BEGIN DESCRIPTION:
Mapping XS e8a8afaa
END DESCRIPTION:
XS GIS Cut Line= 4
      2250700.07     13279063.85      2250627.14     13279376.38
      2251085.48     13279751.38      2251366.77     13279761.80
#Sta/Elev= 30
  4270.7  188.09  4434.0  180.85  4507.0  173.89  4509.7  173.39  4513.0  173.89
  4566.8  178.72  4634.7  176.88  4692.1  179.48  4698.6  176.48  4706.5  179.49
  4720.9  179.05  4727.3  175.70  4741.7  179.54  4776.8  177.85  4784.7  180.42
  4791.2  177.80  4819.9  181.38  4834.3  181.02  4840.7  177.75  4863.0  179.57
  4869.4  177.30  4883.8  180.05  4997.2  176.81  5025.9  179.91  5046.7  177.48
  5118.8  180.61  5148.0  180.88  5198.9  183.60  5246.1  182.61  5465.3  197.32
#Mann=5,-1,0
  4270.7    0.05       0  4507.0    0.03       0  4513.0    0.05       0
  5118.8     0.1       0  5148.0    0.05       0
Bank Sta=4507,4513
Exp/Cntr=0.3,0.1

Type RM Length L Ch R = 1,1063,288,288,288
BEGIN DESCRIPTION:
Mapping XS 41f34605
END DESCRIPTION:
XS GIS Cut Line= 3
      2250729.15     13279573.71      2251127.14     13279881.59
      2251199.09     13279902.14
#Sta/Elev= 30
  4757.0  173.63  4772.2  174.10  4786.7  173.45  4865.5  174.56  4915.3  174.05
  4929.8  174.43  4936.1  174.12  4944.3  172.61  4950.6  172.78  4965.1  171.34
  4997.4  169.80  5000.2  169.30  5003.4  169.80  5014.9  170.56  5021.2  170.39
  5029.4  171.25  5050.2  171.45  5079.2  173.89  5100.0  174.65  5108.2  175.76
  5121.5  176.24  5222.3  181.57  5228.6  182.61  5260.2  184.19  5271.2  185.56
  5302.6  186.75  5312.8  188.92  5323.2  189.91  5331.2  188.89  5335.0  188.94
#Mann=4,-1,0
  4757.0     0.1       0  4997.4    0.07       0  5003.4     0.1       0
  5121.5    0.05       0
Bank Sta=4997.4,5003.4
Exp/Cntr=0.3,0.1

Type RM Length L Ch R = 1,775,484,484,484
BEGIN DESCRIPTION:
Mapping XS df53fe1d
END DESCRIPTION:
XS GIS Cut Line= 4
      2250631.65     13279689.74      2250663.14     13279850.70
      2250925.64     13280071.20      2251302.67     13280011.85
#Sta/Elev= 30
  4688.3  171.81  4756.7  172.00  4846.7  170.81  4951.8  171.87  4959.6  170.70
  4966.1  168.26  4973.9  167.58  4980.4  165.43  4988.2  164.03  4994.7  161.31
  4998.9  161.26  5001.7  160.76  5004.9  161.26  5029.9  167.59  5037.6  167.89
  5044.2  171.39  5051.9  172.55  5101.4  174.50  5122.2  174.34  5186.0  176.03
  5193.2  176.91  5247.8  178.72  5254.1  179.60  5268.1  179.48  5288.3  181.07
  5328.8  181.61  5339.0  182.71  5403.3  185.53  5470.6  188.60  5576.8  191.29
#Mann=4,-1,0
  4688.3     0.1       0  4998.9    0.07       0  5004.9     0.1       0
  5403.3    0.05       0
Bank Sta=4998.9,5004.9
Exp/Cntr=0.3,0.1

Type RM Length L Ch R = 1,291,0,0,0
BEGIN DESCRIPTION:
UNT027 IN SPCR 1.0
END DESCRIPTION:
XS GIS Cut Line= 3
      2250259.06     13279787.86      2250443.65     13280253.95
      2251273.48     13280369.20
#Sta/Elev= 30
  4718.4  171.77  4771.1  170.68  4917.4  170.15  4932.4  167.06  4941.7  169.08
  4947.1  166.06  4953.9  168.90  4964.7  168.96  4971.4  166.94  4976.8  160.27
  5001.1  158.09  5022.5  157.64  5025.2  157.14  5028.5  157.64  5030.8  161.64
  5055.2  166.74  5061.5  164.20  5072.3  161.67  5079.5  161.71  5084.9  164.98
  5093.8  167.53  5109.2  168.19  5169.1  169.26  5415.6  169.03  5486.3  169.62
  5627.7  172.31  5849.8  179.00  5861.8  178.65  5981.0  181.98  6057.5  183.09
#Mann=3,-1,0
  4718.4     0.1       0  5022.5    0.07       0  5028.5     0.1       0
Bank Sta=5022.5,5028.5
Exp/Cntr=0.3,0.1

Chan Stop Cuts=-1