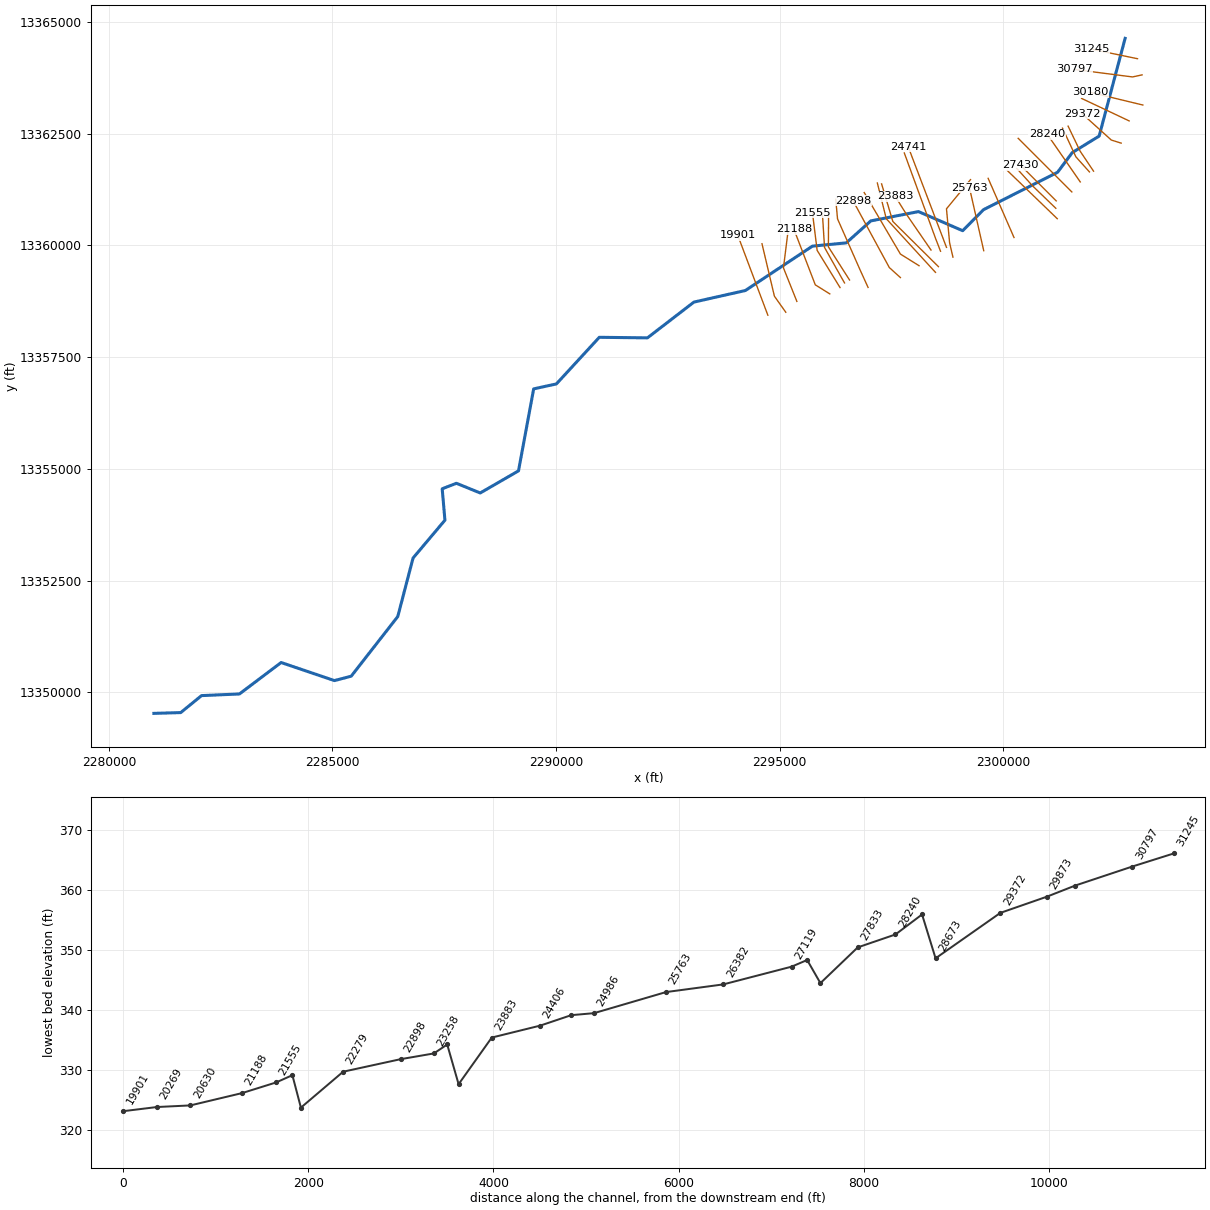
--- UNT029 IN SPCR.prj (project) ---

Proj Title=UNT029 IN SPCR Base Level Engineering
Current Plan=p01
Default Exp/Contr=0.3,0.1
English Units
Geom File=g01
Flow File=f01
Plan File=p01
Y Axis Title=Elevation
X Axis Title(PF)=Main Channel Distance
X Axis Title(XS)=Station
BEGIN DESCRIPTION:
UNT029 IN SPCR
END DESCRIPTION:
DSS Export Rating Curves= 0
DSS Export Rating Curve Sorted= 0
DSS Export Volume Flow Curves= 0
DXF OffsetX= 0
DXF OffsetY= 0
DXF ScaleX= 1
DXF ScaleY= 10

--- UNT029 IN SPCR.p01 (plan) ---

Plan Title=Multiple Run
Short Identifier=Multiple
Geom File=g01
Flow File=f01
Subcritical Flow
K Sum by GR= 0
Std Step Tol= 0.01
Critical Tol= 0.01
Num of Std Step Trials= 20
Max Error Tol= 0.3
Flow Tol Ratio= 0.001
Split Flow NTrial= 30
Split Flow Tol= 0.02
Split Flow Ratio= 0.02
Log Output Level= 0
Friction Slope Method= 1
Unsteady Friction Slope Method= 2
Unsteady Bridges Friction Slope Method= 1
Parabolic Critical Depth
Global Vel Dist=  1 , 1 , 1
Global Log Level= 0
CheckData=True
Encroach Param= -1, 0, 0, 0
BEGIN DESCRIPTION:
Multiple Run
END DESCRIPTION:

--- UNT029 IN SPCR.f01 (steady flow) ---

Flow Title=Multiple
Program Version=4.10
Number of Profiles= 7
Profile Names=10-year,25-year,50-year,1pct_min,100-year,1pct_plu,500-year
River Rch & RM=UNT029 IN SPCR,Reach-1         ,31245
     652     926    1157    1056    1428    1931    2185
River Rch & RM=UNT029 IN SPCR,Reach-1         ,30180
    1042    1514    1919    1773    2398    3243    3763
River Rch & RM=UNT029 IN SPCR,Reach-1         ,24741
    1506    2228    2858    2670    3611    4883    5791
River Rch & RM=UNT029 IN SPCR,Reach-1         ,23883
    1506    2228    2858    2670    3611    4883    5791
River Rch & RM=UNT029 IN SPCR,Reach-1         ,21188
    1647    2445    3145    2944    3981    5384    6413
River Rch & RM=UNT029 IN SPCR,Reach-1         ,19301
    1729    2568    3303    3091    4180    5653    6731
River Rch & RM=UNT029 IN SPCR,Reach-1         ,16447
    1805    2682    3452    3232    4371    5911    7048
River Rch & RM=UNT029 IN SPCR,Reach-1         ,10343
    1797    2668    3433    3215    4348    5879    7017
River Rch & RM=UNT029 IN SPCR,Reach-1         ,6315
    1763    2618    3370    3158    4271    5776    6913
River Rch & RM=UNT029 IN SPCR,Reach-1         ,1174
    1987    2988    3880    3669    4963    6711    8180
Boundary for River Rch & Prof#=UNT029 IN SPCR,Reach-1         , 1
Up Type= 0
Dn Type= 3
Dn Slope=0.005
Boundary for River Rch & Prof#=UNT029 IN SPCR,Reach-1         , 2
Up Type= 0
Dn Type= 3
Dn Slope=0.005
Boundary for River Rch & Prof#=UNT029 IN SPCR,Reach-1         , 3
Up Type= 0
Dn Type= 3
Dn Slope=0.005
Boundary for River Rch & Prof#=UNT029 IN SPCR,Reach-1         , 4
Up Type= 0
Dn Type= 3
Dn Slope=0.005
Boundary for River Rch & Prof#=UNT029 IN SPCR,Reach-1         , 5
Up Type= 0
Dn Type= 3
Dn Slope=0.005
Boundary for River Rch & Prof#=UNT029 IN SPCR,Reach-1         , 6
Up Type= 0
Dn Type= 3
Dn Slope=0.005
Boundary for River Rch & Prof#=UNT029 IN SPCR,Reach-1         , 7
Up Type= 0
Dn Type= 3
Dn Slope=0.005
DSS Import GetInterval= 0
DSS Import GetPeak= 0
DSS Import FillOption= 0

--- UNT029 IN SPCR.g01 (geometry) ---

Geom Title=Existing Conditions
Program Version=4.10

River Reach=UNT029 IN SPCR  ,Reach-1
Reach XY= 30
      2302729.25     13364634.38      2302148.06     13362446.61
      2301545.41     13362075.42       2301218.4     13361636.55
      2299561.41     13360799.25      2299096.69     13360329.17
      2298107.72     13360756.86      2297040.97     13360548.18
      2296492.79     13360056.92      2295735.63     13359983.58
      2294236.28     13358990.64      2293085.37     13358731.49
      2292046.35     13357931.06      2290969.21     13357943.27
      2290010.16      13356900.4      2289501.58     13356789.06
      2289162.13     13354954.22      2288306.43      13354459.6
      2287773.42     13354676.41      2287455.59     13354553.42
      2287517.01     13353850.48      2286804.17     13353003.61
      2286462.18     13351694.26      2285420.73     13350359.13
      2285045.81     13350260.43      2283853.53      13350664.9
      2282920.64     13349961.25      2282073.72      13349924.5
      2281607.87      13349544.5      2281007.72     13349526.85

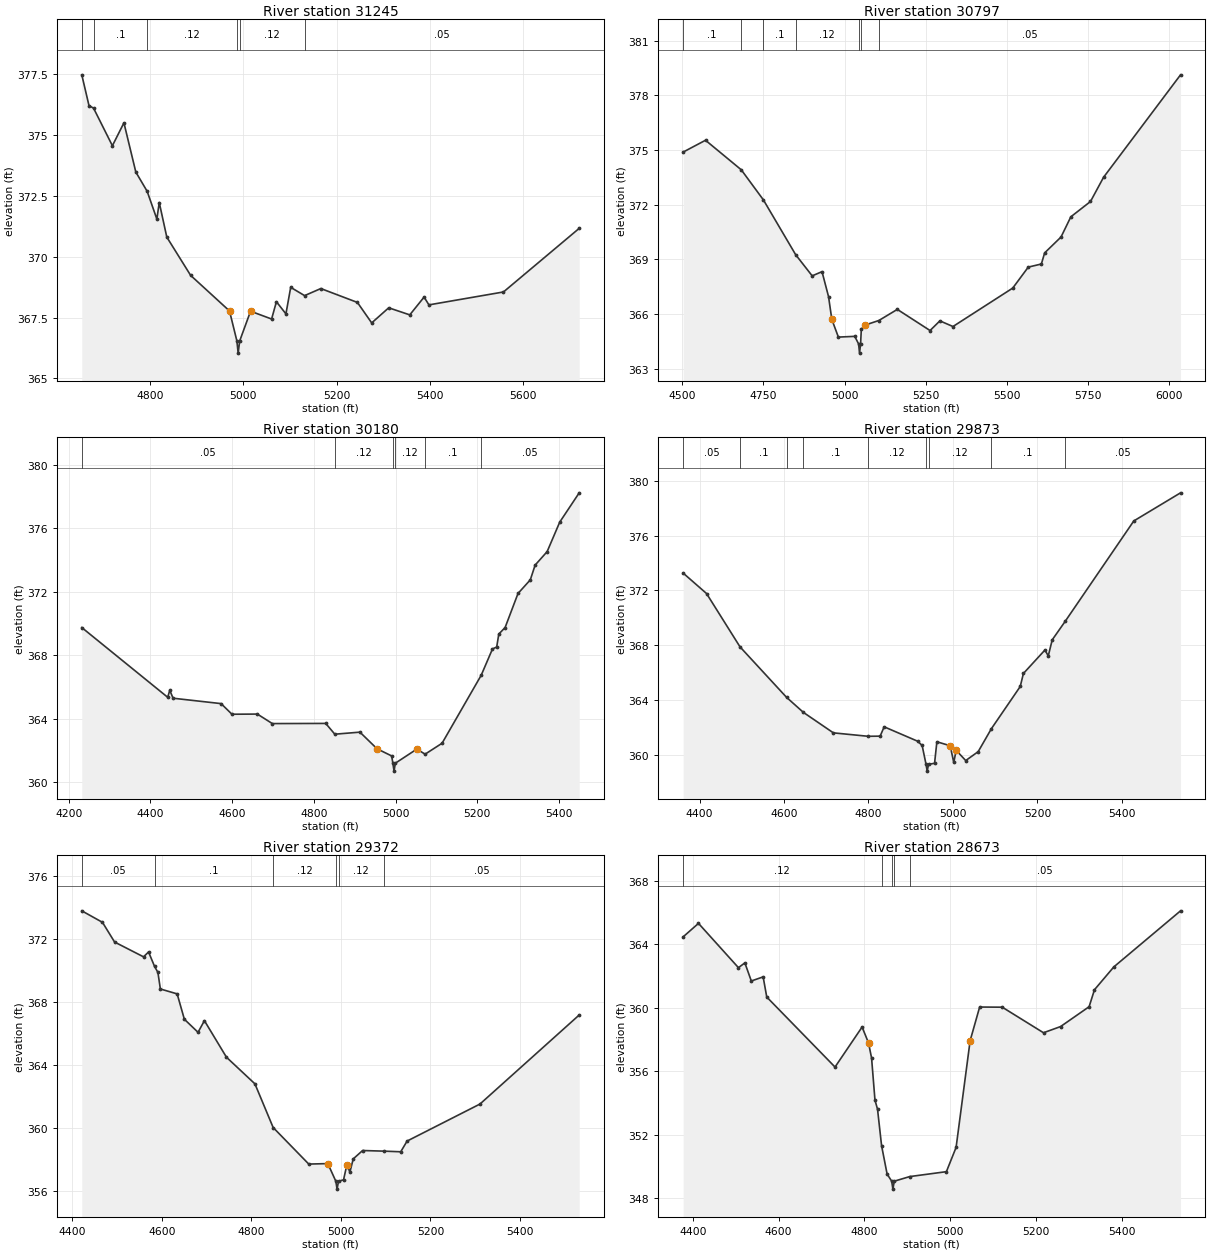
Type RM Length L Ch R = 1 ,31245   ,448,448,448
BEGIN DESCRIPTION:
UNT029 IN SPCR 63.0
END DESCRIPTION:
XS GIS Cut Line= 2
      2303006.13     13364178.38      2301962.26     13364394.44
#Sta/Elev= 30
  4653.7  377.46  4669.1   376.2    4679  376.09  4719.3  374.55    4744  375.49
  4769.5  373.47  4793.8  372.68  4814.6  371.54  4819.7  372.22  4835.9   370.8
    4887  369.23  4970.3  367.77  4986.1  366.54  4988.8  366.04  4992.1  366.54
  5015.4  367.76  5060.5  367.44  5070.8  368.15  5091.2  367.65  5101.4  368.74
  5131.2   368.4    5166  368.69  5244.4  368.12    5275  367.28  5311.5   367.9
  5356.6  367.61  5387.3  368.34  5397.6  368.02  5557.4  368.55  5719.7  371.16
#Mann= 6 ,-1 , 0
  4653.7     .05       0    4679      .1       0  4793.8     .12       0
  4986.1     .07       0  4992.1     .12       0  5131.2     .05       0
Bank Sta=4970.3,5015.4
XS Rating Curve= 0 ,0
Exp/Cntr=0.3,0.1

Type RM Length L Ch R = 1 ,30797   ,617,617,617
BEGIN DESCRIPTION:
UNT029 IN SPCR 62.0
END DESCRIPTION:
XS GIS Cut Line= 3
      2303108.74      13363816.7      2302894.64     13363770.41
      2301592.65     13363938.22
#Sta/Elev= 30
  4502.7  374.89  4571.6  375.54  4681.7  373.92  4749.8  372.27  4849.3  369.26
  4900.1   368.1  4930.4  368.33  4950.5  366.96  4960.6  365.71  4980.8  364.74
  5031.2  364.78  5043.2  364.36  5045.9  363.86  5049.2  364.36  5051.4  365.16
  5061.5  365.39  5105.4  365.65  5162.3  366.26  5263.1   365.1  5293.4  365.63
  5333.7  365.32  5517.8  367.43  5565.6  368.58  5605.9  368.75    5616  369.36
  5666.4  370.23  5696.7  371.34  5757.2  372.18  5797.5  373.51  6034.5  379.13
#Mann= 7 ,-1 , 0
  4502.7      .1       0  4681.7     .05       0  4749.8      .1       0
  4849.3     .12       0  5043.2     .07       0  5049.2     .12       0
  5105.4     .05       0
Bank Sta=4960.6,5061.5
XS Rating Curve= 0 ,0
Exp/Cntr=0.3,0.1

Type RM Length L Ch R = 1 ,30180   ,307,307,307
BEGIN DESCRIPTION:
UNT029 IN SPCR 61.0
END DESCRIPTION:
XS GIS Cut Line= 2
      2303124.98     13363141.94      2301941.38     13363428.08
#Sta/Elev= 30
  4231.9  369.75  4442.2  365.35  4447.3  365.79  4455.4  365.29  4572.9  364.95
  4599.5  364.28  4661.7  364.29  4698.4  363.69  4829.1   363.7  4851.3  363.02
  4912.8  363.15  4954.7   362.1  4990.4  361.65  4993.5  361.19  4996.3  360.69
  4999.5  361.19  5052.1  362.08  5072.4  361.76  5113.9  362.45  5209.7  366.74
  5237.3   368.4  5247.6  368.52  5252.8  369.34  5268.2  369.75  5299.8   371.9
  5329.9  372.76  5341.7  373.69  5371.1  374.54  5401.9   376.4  5449.6  378.25
#Mann= 6 ,-1 , 0
  4231.9     .05       0  4851.3     .12       0  4993.5     .07       0
  4999.5     .12       0  5072.4      .1       0  5209.7     .05       0
Bank Sta=4954.7,5052.1
XS Rating Curve= 0 ,0
Exp/Cntr=0.3,0.1

Type RM Length L Ch R = 1 ,29873   ,501,501,501
BEGIN DESCRIPTION:
UNT029 IN SPCR 60.0
END DESCRIPTION:
XS GIS Cut Line= 2
      2302819.42      13362786.6      2301754.55      13363290.1
#Sta/Elev= 30
  4361.1  373.27  4416.5  371.78  4495.8  367.89    4606  364.21    4646  363.11
  4716.9  361.62  4799.2  361.37  4827.6  361.38  4837.2  362.06  4916.5  361.01
  4927.1   360.7  4936.3  359.33    4939  358.83  4942.3  359.33  4956.5   359.4
    4962  360.97  4993.5  360.68    5002  359.46  5007.6  360.35  5030.3   359.6
  5059.8  360.25    5091  361.92  5159.4     365  5166.9  365.95  5217.9  367.66
  5225.8  367.23  5235.1   368.4  5265.6  369.74  5428.3  377.07    5539  379.12
#Mann= 9 ,-1 , 0
  4361.1     .05       0  4495.8      .1       0    4606     .05       0
    4646      .1       0  4799.2     .12       0  4936.3     .07       0
  4942.3     .12       0    5091      .1       0  5265.6     .05       0
Bank Sta=4993.5,5007.6
XS Rating Curve= 0 ,0
Exp/Cntr=0.3,0.1

Type RM Length L Ch R = 1 ,29372   ,699,699,699
BEGIN DESCRIPTION:
UNT029 IN SPCR 59.0
END DESCRIPTION:
XS GIS Cut Line= 3
      2302639.97     13362288.94       2302420.1     13362358.37
      2301766.17     13362948.64
#Sta/Elev= 30
  4420.9   373.8  4467.1  373.07  4494.2  371.82  4558.9  370.88  4570.1  371.19
  4583.4  370.28    4591  369.89  4596.5  368.84    4634  368.53  4650.1  366.92
  4680.7  366.09  4694.9  366.83  4744.2  364.51  4807.8  362.82  4848.5  360.05
  4928.1  357.73  4970.7  357.76  4988.6  356.64  4991.3  356.14  4994.6  356.64
  5005.8  356.73  5013.3  357.69    5020  357.22  5027.5  358.06  5048.4  358.59
  5096.5  358.55  5133.6  358.51  5147.8  359.19  5310.7  361.54  5532.4  367.19
#Mann= 6 ,-1 , 0
  4420.9     .05       0  4583.4      .1       0  4848.5     .12       0
  4988.6     .07       0  4994.6     .12       0  5096.5     .05       0
Bank Sta=4970.7,5013.3
XS Rating Curve= 0 ,0
Exp/Cntr=0.3,0.1

Type RM Length L Ch R = 1 ,28673   ,146,146,146
BEGIN DESCRIPTION:
UNT029 IN SPCR 58.0
END DESCRIPTION:
XS GIS Cut Line= 3
      2302022.56     13361661.93       2301723.1     13362108.94
      2301453.98     13362668.88
#Sta/Elev= 30
  4377.7  364.47  4413.5  365.32  4506.6  362.53  4521.6  362.83  4536.6  361.69
  4564.2  361.95  4572.6  360.68  4731.7  356.27  4794.8  358.79  4809.8  357.79
  4816.9  356.84  4824.8  354.19  4830.8  353.61  4840.2  351.32  4853.1  349.53
  4863.8  349.08  4866.6  348.58  4869.8  349.08  4905.8  349.37  4991.3  349.68
  5013.9  351.21  5046.6  357.93  5068.8  360.05  5121.5  360.04  5217.6  358.43
  5257.4  358.82  5323.9  360.07  5336.4  361.14  5381.6  362.58    5537  366.11
#Mann= 5 ,-1 , 0
  4377.7     .12       0  4840.2      .1       0  4863.8     .03       0
  4869.8      .1       0  4905.8     .05       0
Bank Sta=4809.8,5046.6
XS Rating Curve= 0 ,0
Exp/Cntr=0.3,0.1

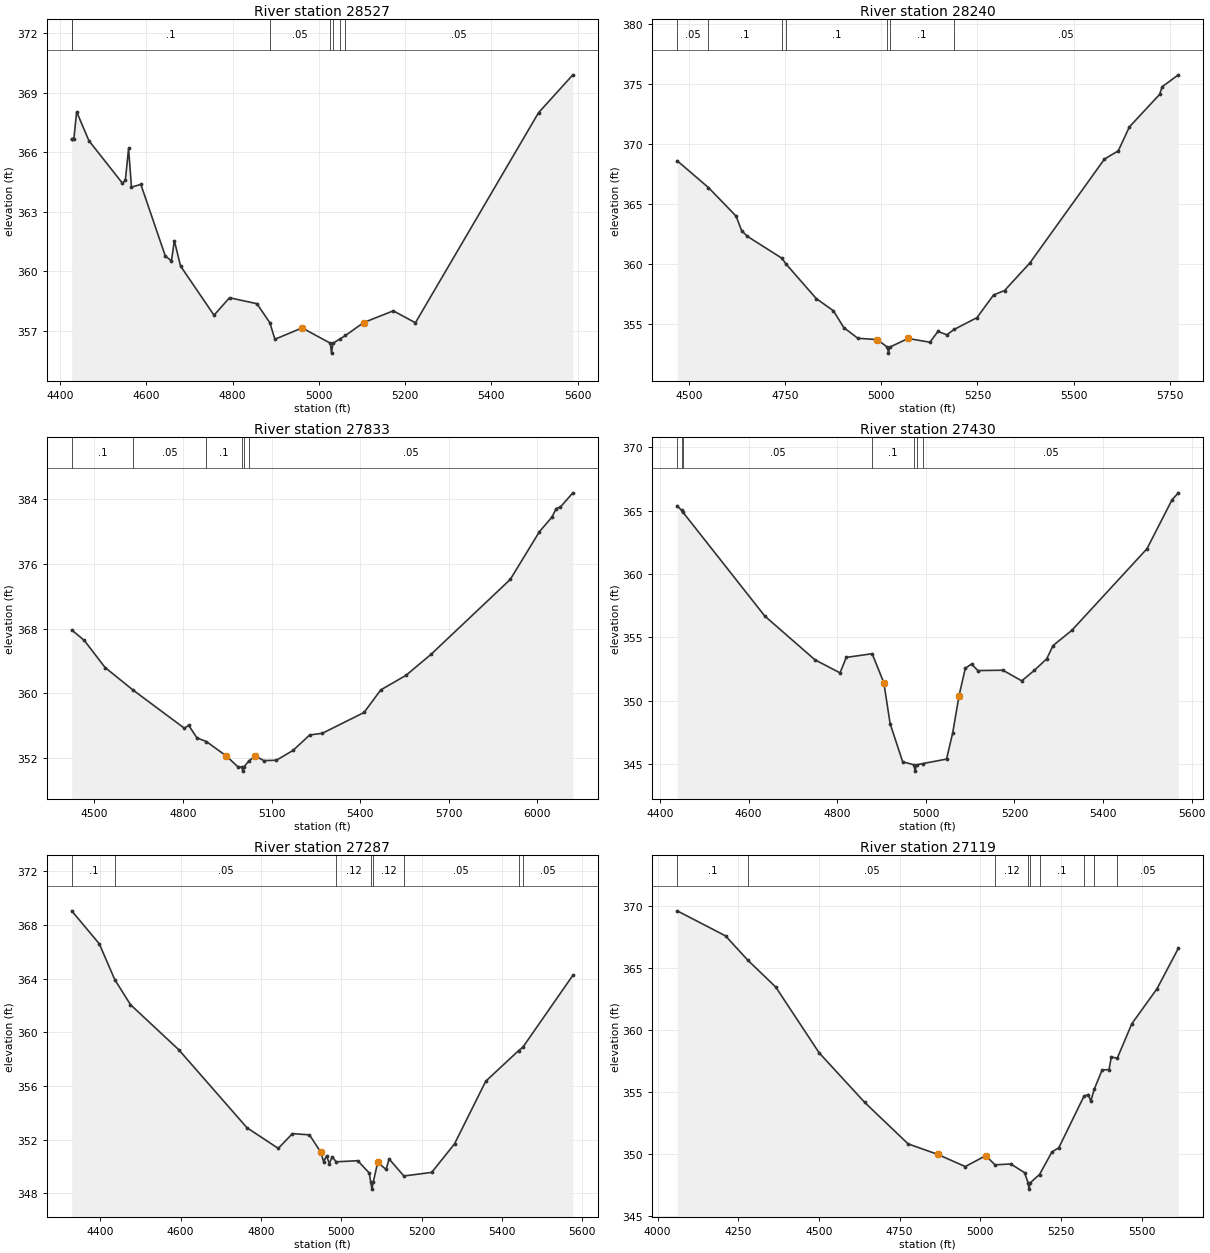
Type RM Length L Ch R = 1 ,28527   ,287,287,287
BEGIN DESCRIPTION:
Mapping XS 85859742
END DESCRIPTION:
XS GIS Cut Line= 3
      2301931.44     13361644.53      2301627.61     13361983.08
      2301328.95     13362623.69
#Sta/Elev= 30
  4427.1  366.65  4427.6  366.65    4432  366.65  4438.5  368.04    4467  366.58
  4544.7  364.44  4551.4  364.58  4558.9  366.19  4565.6  364.24  4587.3  364.38
  4644.1  360.77  4658.3  360.53    4665  361.55  4679.3  360.27    4757  357.79
  4792.9  358.67  4856.4  358.37  4886.4  357.41  4898.1  356.58  4961.2  357.15
  5026.6  356.38  5029.3  355.88  5032.6  356.38  5050.1  356.61  5061.7  356.77
  5103.9  357.42  5172.5  358.01  5223.8  357.41  5509.2  367.99  5588.8   369.9
#Mann= 7 ,-1 , 0
  4427.1     .12       0  4427.6      .1       0  4886.4     .05       0
  5026.6     .03       0  5032.6     .05       0  5050.1      .1       0
  5061.7     .05       0
Bank Sta=4961.2,5103.9
XS Rating Curve= 0 ,0
Exp/Cntr=0.3,0.1

Type RM Length L Ch R = 1 ,28240   ,407,407,407
BEGIN DESCRIPTION:
UNT029 IN SPCR 57.0
END DESCRIPTION:
XS GIS Cut Line= 2
      2301725.64      13361420.9      2300984.94     13362491.43
#Sta/Elev= 30
  4469.8  368.59  4551.2  366.35    4623  363.97  4637.2  362.77    4652  362.29
    4742  360.46  4751.8  360.01  4831.1   357.1  4875.7  356.08  4902.7  354.68
  4939.1  353.79  4989.2  353.68    5016  353.05  5018.7  352.55    5022  353.05
  5069.7  353.77  5126.4  353.46  5147.4  354.36  5170.2  354.08  5189.7  354.53
  5248.7  355.51  5291.8   357.4  5320.4  357.77  5385.9  360.06  5579.9  368.73
  5615.7  369.41  5644.4   371.4  5723.1  374.12  5729.6  374.75  5771.6  375.75
#Mann= 7 ,-1 , 0
  4469.8     .05       0  4551.2      .1       0    4742     .05       0
  4751.8      .1       0    5016     .07       0    5022      .1       0
  5189.7     .05       0
Bank Sta=4989.2,5069.7
XS Rating Curve= 0 ,0
Exp/Cntr=0.3,0.1

Type RM Length L Ch R = 1 ,27833   ,403,403,403
BEGIN DESCRIPTION:
UNT029 IN SPCR 56.0
END DESCRIPTION:
XS GIS Cut Line= 3
      2301537.69     13361196.89      2301137.72     13361596.85
      2300337.73     13362396.85
#Sta/Elev= 30
    4423  367.83  4465.4  366.54  4536.1  363.19  4630.7  360.41  4804.8  355.69
  4818.9  356.06  4847.2   354.5  4879.2  354.05  4946.2  352.28  4985.1  350.96
  4999.8   350.9  5002.5   350.4  5005.8   350.9  5023.1  351.68  5045.2  352.27
  5073.5   351.7  5115.9  351.74  5172.5  352.96  5229.1  354.87  5271.5  355.07
  5412.9  357.64  5469.5  360.43  5554.3  362.21  5639.2   364.8  5907.9  374.06
  6006.9  379.97  6049.3  381.77  6063.4  382.81  6077.6     383    6120  384.76
#Mann= 6 ,-1 , 0
    4423      .1       0  4630.7     .05       0  4879.2      .1       0
  4999.8     .07       0  5005.8      .1       0  5023.1     .05       0
Bank Sta=4946.2,5045.2
XS Rating Curve= 0 ,0
Exp/Cntr=0.3,0.1

Type RM Length L Ch R = 1 ,27430   ,143,143,143
BEGIN DESCRIPTION:
UNT029 IN SPCR 55.0
END DESCRIPTION:
XS GIS Cut Line= 3
      2301187.69     13360996.88      2300787.72     13361396.85
      2300387.74     13361796.83
#Sta/Elev= 30
  4438.6  365.37  4448.5  365.03  4450.8  364.91  4636.5  356.68  4749.7  353.23
  4806.3   352.2  4820.4  353.42  4878.8  353.71  4905.2  351.42  4919.4  348.19
  4947.7  345.19    4973  344.95  4975.7  344.45    4979  344.95  4993.9  345.05
  5046.7   345.4  5060.8  347.49    5075  350.41  5089.1  352.56  5103.2   352.9
  5117.4  352.38    5174  352.41  5216.4  351.57  5244.7  352.39  5272.9  353.31
  5287.1  354.35  5329.5  355.55  5499.2  361.99  5555.8  365.85  5569.9   366.4
#Mann= 7 ,-1 , 0
  4438.6     .05       0  4448.5      .1       0  4450.8     .05       0
  4878.8      .1       0    4973     .03       0    4979      .1       0
  4993.9     .05       0
Bank Sta=4905.2,5075
XS Rating Curve= 0 ,0
Exp/Cntr=0.3,0.1

Type RM Length L Ch R = 1 ,27287   ,168,168,168
BEGIN DESCRIPTION:
Mapping XS b13f52ac
END DESCRIPTION:
XS GIS Cut Line= 3
      2301178.84     13360831.15       2300660.6     13361331.17
      2300306.44     13361721.78
#Sta/Elev= 30
  4328.9  369.06  4397.5   366.6  4436.2  363.92  4475.2  362.06  4595.3   358.7
  4765.1  352.88    4843  351.34  4878.3  352.44  4920.7  352.35    4949  351.05
    4956  350.34  4963.2  350.79  4970.1  350.21  4977.3  350.71  4987.1  350.34
  5040.9  350.42  5069.6   349.5  5073.3   348.8  5076.1   348.3  5079.3   348.8
  5090.5  350.29  5111.4  349.77  5118.9  350.55  5155.7  349.28    5225  349.55
  5281.8  351.68  5359.5  356.35  5441.5  358.64  5451.7  358.88  5576.3  364.25
#Mann= 8 ,-1 , 0
  4328.9      .1       0  4436.2     .05       0  4987.1     .12       0
  5073.3     .07       0  5079.3     .12       0  5155.7     .05       0
  5441.5      .1       0  5451.7     .05       0
Bank Sta=4949,5090.5
XS Rating Curve= 0 ,0
Exp/Cntr=0.3,0.1

Type RM Length L Ch R = 1 ,27119   ,737,737,737
BEGIN DESCRIPTION:
UNT029 IN SPCR 54.0
END DESCRIPTION:
XS GIS Cut Line= 2
      2301211.15     13360598.33      2300093.93     13361676.48
#Sta/Elev= 30
  4060.6  369.64  4210.5  367.62  4279.1  365.67  4366.1  363.49  4500.4  358.19
  4641.9  354.18  4776.2  350.84  4868.3  349.99  4953.2  349.01  5016.7  349.89
  5045.4  349.15  5094.4  349.22  5136.9  348.52    5148  347.69  5150.8  347.19
    5154  347.69  5183.3  348.37  5221.7  350.19  5243.1  350.53  5321.2   354.7
  5334.9  354.82  5342.1  354.27  5352.5  355.23  5377.4  356.81  5398.7  356.83
  5405.7  357.85  5424.1  357.75  5469.2  360.53  5547.2  363.35  5613.2  366.61
#Mann= 9 ,-1 , 0
  4060.6      .1       0  4279.1     .05       0  5045.4     .12       0
    5148     .03       0    5154     .12       0  5183.3      .1       0
  5321.2     .05       0  5352.5      .1       0  5424.1     .05       0
Bank Sta=4868.3,5016.7
XS Rating Curve= 0 ,0
Exp/Cntr=0.3,0.1

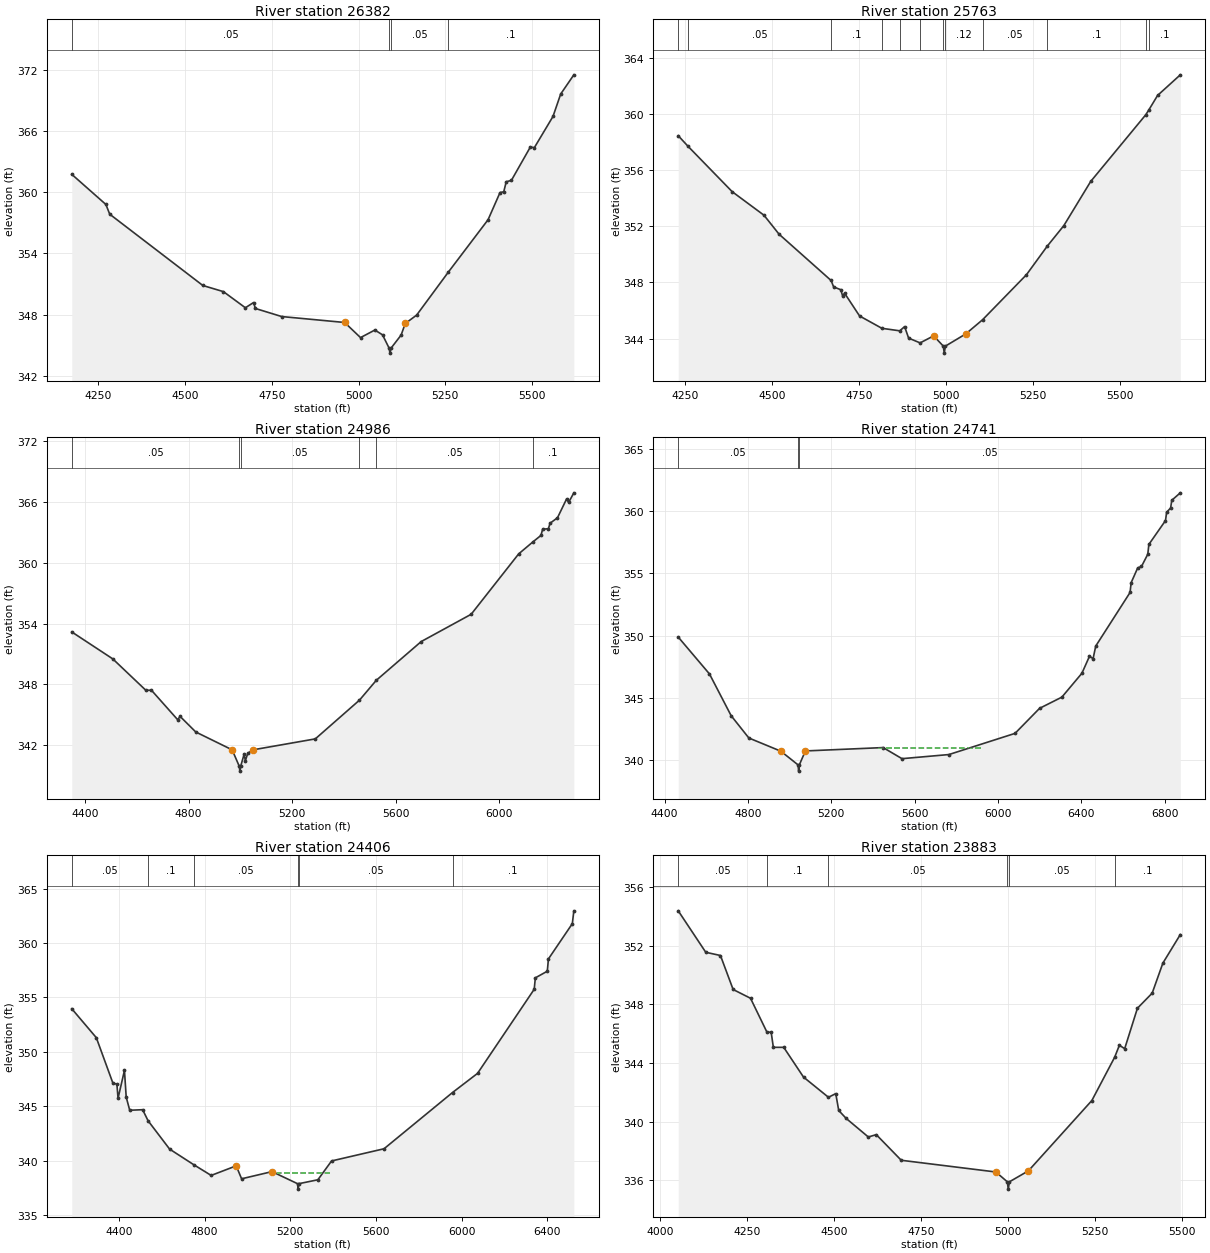
Type RM Length L Ch R = 1 ,26382   ,619,619,619
BEGIN DESCRIPTION:
UNT029 IN SPCR 53.0
END DESCRIPTION:
XS GIS Cut Line= 2
      2300244.16     13360176.68      2299665.49     13361501.84
#Sta/Elev= 30
  4174.1  361.74  4272.4  358.79  4283.4  357.84  4551.6  350.86  4610.8  350.26
  4674.1  348.68  4697.5  349.19    4703  348.61  4778.7  347.82    4960  347.24
  5005.7  345.76    5047   346.5  5069.1  346.03  5087.9  344.74  5090.6  344.24
  5093.9  344.74  5122.7  346.01  5134.5  347.14  5167.3  347.96  5258.2  352.15
  5373.1   357.3  5407.5  359.96  5418.2  360.03  5425.4  361.02  5440.1  361.14
  5494.6   364.4  5506.5  364.36  5560.1  367.41  5582.2   369.6  5620.1  371.48
#Mann= 4 ,-1 , 0
  4174.1     .05       0  5087.9     .03       0  5093.9     .05       0
  5258.2      .1       0
Bank Sta=4960,5134.5
XS Rating Curve= 0 ,0
Exp/Cntr=0.3,0.1

Type RM Length L Ch R = 1 ,25763   ,777,777,777
BEGIN DESCRIPTION:
UNT029 IN SPCR 52.0
END DESCRIPTION:
XS GIS Cut Line= 2
      2299567.09     13359881.53       2299248.8     13361287.76
#Sta/Elev= 30
  4231.3  358.46  4259.6   357.7  4386.2  354.47  4477.6  352.79  4520.8  351.44
  4670.2  348.14  4677.6  347.68  4698.1  347.48  4703.7  347.01  4708.8  347.24
    4752  345.61  4816.1  344.73  4867.4  344.55  4881.4  344.85  4892.9  344.03
  4925.9  343.69  4964.7  344.19  4992.5  343.46  4995.2  342.96  4998.5  343.46
    5057  344.33  5105.3  345.34  5231.3  348.55  5290.8  350.58  5338.6  352.05
  5415.8   355.2  5573.8  359.95  5581.8  360.26  5607.8  361.33  5673.1   362.8
#Mann= 12 ,-1 , 0
  4231.3      .1       0  4259.6     .05       0  4670.2      .1       0
  4816.1     .05       0  4867.4      .1       0  4925.9     .12       0
  4992.5     .07       0  4998.5     .12       0  5105.3     .05       0
  5290.8      .1       0  5573.8     .05       0  5581.8      .1       0
Bank Sta=4964.7,5057
XS Rating Curve= 0 ,0
Exp/Cntr=0.3,0.1

Type RM Length L Ch R = 1 ,24986   ,245,245,245
BEGIN DESCRIPTION:
UNT029 IN SPCR 51.0
END DESCRIPTION:
XS GIS Cut Line= 4
      2298878.42     13359736.89       2298803.2     13360060.91
      2298733.76     13360819.02      2299271.48     13361472.38
#Sta/Elev= 30
  4348.9  353.18  4507.4  350.52  4635.3  347.42  4656.8  347.43  4757.8  344.53
  4767.8  344.84  4828.1  343.31  4968.7  341.55  4995.8  339.95  4998.6  339.45
  5001.8  339.95  5014.8  341.11  5019.8  340.48  5028.9   341.2    5049  341.55
    5290  342.63  5460.6  346.45  5525.7  348.41  5699.2  352.23  5892.2  354.92
  6075.9  360.88  6129.4  362.03  6161.9   362.7  6168.4  363.31  6190.6  363.36
  6197.1   363.9  6225.8  364.44    6261   366.3  6268.8  365.95    6289   366.9
#Mann= 6 ,-1 , 0
  4348.9     .05       0  4995.8     .03       0  5001.8     .05       0
  5460.6      .1       0  5525.7     .05       0  6129.4      .1       0
Bank Sta=4968.7,5049
XS Rating Curve= 0 ,0
Exp/Cntr=0.3,0.1

Type RM Length L Ch R = 1 ,24741   ,335,335,335
BEGIN DESCRIPTION:
UNT029 IN SPCR 50.0
END DESCRIPTION:
XS GIS Cut Line= 2
      2298733.75     13359956.77      2297877.26     13362207.94
#Sta/Elev= 30
  4465.8  349.88  4615.7  346.92  4719.6  343.57  4804.5  341.78  4958.1  340.72
  5040.7  339.62  5043.4  339.12  5046.7  339.62  5075.8  340.74  5448.9  341.01
  5539.2  340.12  5764.1  340.45  6081.5  342.15  6199.2  344.16  6306.2  345.06
  6402.5  346.98  6438.6  348.34    6456  348.15  6468.7  349.16  6633.3  353.46
  6638.6  354.25  6669.9  355.43  6688.2  355.55  6718.3  356.53  6723.6  357.32
  6803.2  359.23    6809   359.9    6828  360.25  6833.4  360.86  6874.4  361.46
#Mann= 3 ,-1 , 0
  4465.8     .05       0  5040.7     .04       0  5046.7     .05       0
#XS Ineff= 1 ,-1
 5423.91  5928.2  341.01
Permanent Ineff=
       F
Bank Sta=4958.1,5075.8
XS Rating Curve= 0 ,0
Exp/Cntr=0.3,0.1

Type RM Length L Ch R = 1 ,24406   ,523,523,523
BEGIN DESCRIPTION:
Mapping XS 7477af78
END DESCRIPTION:
XS GIS Cut Line= 3
      2298600.64     13359869.98       2298490.7     13360153.51
      2297790.46     13362069.03
#Sta/Elev= 30
  4180.2  353.96  4294.8   351.3  4371.7  347.15  4390.9  347.02  4396.2  345.73
  4426.1  348.29  4434.3  345.84  4450.7  344.63    4511  344.68  4536.5  343.66
  4636.9  341.06  4750.8  339.61  4830.9  338.64  4947.7  339.52  4972.9  338.33
    5115  338.99  5234.1  337.88  5236.8  337.38  5240.1  337.88    5329  338.24
  5392.9  339.97  5637.8  341.09  5957.5  346.26  6074.3  348.02  6338.8  355.75
  6344.1   356.8  6399.9  357.41  6405.2  358.54  6516.7  361.78  6523.8  362.96
#Mann= 6 ,-1 , 0
  4180.2     .05       0  4536.5      .1       0  4750.8     .05       0
  5234.1     .03       0  5240.1     .05       0  5957.5      .1       0
#XS Ineff= 1 ,-1
 5136.26 5386.23  338.87
Permanent Ineff=
       F
Bank Sta=4947.7,5115
XS Rating Curve= 0 ,0
Exp/Cntr=0.3,0.1

Type RM Length L Ch R = 1 ,23883   ,358,358,358
BEGIN DESCRIPTION:
UNT029 IN SPCR 48.0
END DESCRIPTION:
XS GIS Cut Line= 3
      2298387.71     13359896.88      2297837.72     13360696.85
      2297587.72     13361096.86
#Sta/Elev= 30
  4052.1  354.39  4131.2  351.56  4173.4  351.34  4209.8  349.02  4259.8  348.42
  4306.9  346.11  4319.1   346.1  4325.4  345.07  4355.2  345.07    4412  343.04
  4483.7  341.66  4504.7  341.91  4513.2  340.76  4534.5  340.22  4598.2  338.95
  4621.1  339.11  4692.8  337.36  4964.7  336.56  4997.6  335.89  5000.3  335.39
  5003.6  335.89  5058.3  336.64  5240.5  341.44  5306.1   344.4  5319.5  345.21
  5334.8  344.98  5371.4  347.74  5413.8  348.77  5444.5  350.82  5494.6  352.77
#Mann= 6 ,-1 , 0
  4052.1     .05       0  4306.9      .1       0  4483.7     .05       0
  4997.6     .03       0  5003.6     .05       0  5306.1      .1       0
Bank Sta=4964.7,5058.3
XS Rating Curve= 0 ,0
Exp/Cntr=0.3,0.1

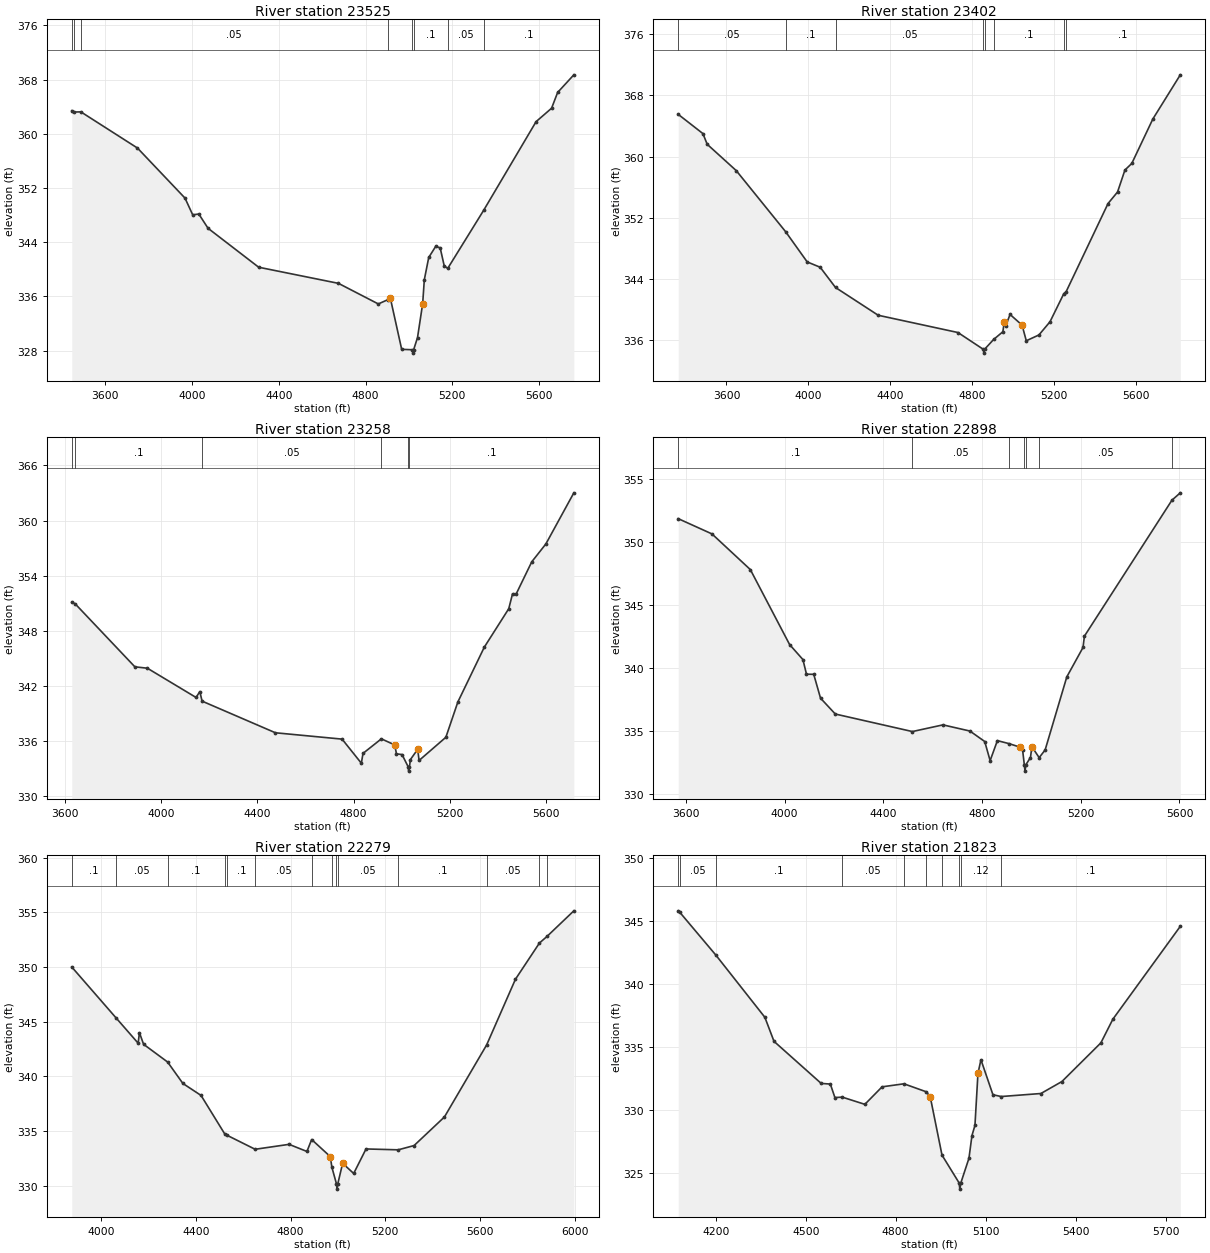
Type RM Length L Ch R = 1 ,23525   ,123,123,123
BEGIN DESCRIPTION:
Mapping XS 57e613a2
END DESCRIPTION:
XS GIS Cut Line= 3
      2298553.92     13359524.76      2297533.97     13360536.03
      2297282.47     13361377.24
#Sta/Elev= 30
  3445.9  363.41  3454.2  363.22    3488  363.24  3748.8   357.9  3967.9  350.51
  4003.3  348.05  4031.6  348.16    4074  346.06  4307.4  340.31  4675.1  337.93
  4858.9  334.89  4901.6   335.5  4914.4  335.74  4966.6  328.19  5015.7  328.13
  5018.5  327.63  5021.7  328.13  5039.6  329.92  5063.4  334.94  5070.9  338.45
  5091.3  341.75  5123.1  343.37    5144  343.18  5162.8   340.5  5178.9  340.14
  5344.1  348.69  5586.2   361.8  5657.6  363.78  5685.5  366.11  5760.2  368.71
#Mann= 8 ,-1 , 0
  3445.9     .05       0  3454.2      .1       0    3488     .05       0
  4901.6      .1       0  5015.7     .07       0  5021.7      .1       0
  5178.9     .05       0  5344.1      .1       0
Bank Sta=4914.4,5063.4
XS Rating Curve= 0 ,0
Exp/Cntr=0.3,0.1

Type RM Length L Ch R = 1 ,23402   ,144,144,144
BEGIN DESCRIPTION:
UNT029 IN SPCR 47.0
END DESCRIPTION:
XS GIS Cut Line= 3
      2298487.74     13359396.83      2297387.72     13360596.85
      2297187.73     13361396.82
#Sta/Elev= 30
  3364.3  365.52  3484.9     363  3505.8   361.6  3647.7  358.15  3888.8  350.15
  3994.2  346.19  4057.7  345.49  4132.5  342.84  4341.1   339.2  4730.5  336.94
  4854.5  334.74  4857.2  334.24  4860.5  334.74  4904.9  336.03    4950  337.04
  4956.8  338.31  4964.2  337.83  4985.1  339.31  5043.8  337.91  5064.4  335.86
  5126.2  336.62  5180.3  338.35  5247.7  342.03  5259.1  342.29  5463.8  353.84
  5510.2  355.35  5546.3  358.23  5579.8  359.09  5682.8  364.92  5816.8   370.7
#Mann= 8 ,-1 , 0
  3364.3     .05       0  3888.8      .1       0  4132.5     .05       0
  4854.5     .07       0  4860.5     .05       0  4904.9      .1       0
  5247.7     .05       0  5259.1      .1       0
Bank Sta=4956.8,5043.8
XS Rating Curve= 0 ,0
Exp/Cntr=0.3,0.1

Type RM Length L Ch R = 1 ,23258   ,360,360,360
BEGIN DESCRIPTION:
Mapping XS ce503ed4
END DESCRIPTION:
XS GIS Cut Line= 3
      2298120.31     13359545.88      2297703.66     13359806.29
      2296894.02     13361182.69
#Sta/Elev= 30
  3627.8  351.14    3642  350.94  3890.3  344.09  3942.2  343.94  4144.7  340.76
  4160.4   341.4  4169.8  340.36  4474.8  336.92  4752.1  336.23  4832.2  333.61
  4839.1  334.68  4915.5  336.26  4970.8   335.6  4978.3  334.63  5001.5  334.55
  5026.4  333.25  5029.1  332.75  5032.4  333.25  5036.3  334.01  5066.5  335.12
  5072.3  333.91  5183.7  336.43  5233.6  340.27  5343.8  346.24  5445.3  350.41
    5461  352.03  5476.6  352.04    5541  355.51  5599.6  357.45    5716  363.01
#Mann= 6 ,-1 , 0
  3627.8     .05       0    3642      .1       0  4169.8     .05       0
  4915.5      .1       0  5026.4     .07       0  5032.4      .1       0
Bank Sta=4970.8,5066.5
XS Rating Curve= 0 ,0
Exp/Cntr=0.3,0.1

Type RM Length L Ch R = 1 ,22898   ,619,619,619
BEGIN DESCRIPTION:
UNT029 IN SPCR 46.0
END DESCRIPTION:
XS GIS Cut Line= 3
      2297703.66     13359279.67      2297454.82     13359505.36
      2296644.66     13360998.37
#Sta/Elev= 30
  3568.7  351.82  3705.4  350.61  3860.9  347.78  4020.1  341.83    4074  340.64
  4088.4  339.48  4117.8  339.47  4145.3  337.58  4205.2  336.32  4517.5  334.93
  4641.5  335.46  4750.8  334.97  4810.7  334.14  4832.6  332.62    4862  334.21
  4909.5  333.97  4952.4   333.7  4964.4  333.43  4971.2  332.29    4974  331.79
  4977.2  332.29  4996.1  332.87  5001.8  333.73  5031.3  332.86  5055.5  333.47
  5143.4  339.27    5209   341.6  5214.7   342.5  5569.5  353.29  5603.3  353.87
#Mann= 7 ,-1 , 0
  3568.7      .1       0  4517.5     .05       0  4909.5      .1       0
  4971.2     .07       0  4977.2      .1       0  5031.3     .05       0
  5569.5      .1       0
Bank Sta=4952.4,5001.8
XS Rating Curve= 0 ,0
Exp/Cntr=0.3,0.1

Type RM Length L Ch R = 1 ,22279   ,456,456,456
BEGIN DESCRIPTION:
UNT029 IN SPCR 44.0
END DESCRIPTION:
XS GIS Cut Line= 4
      2296980.27     13359059.79      2296800.89     13359453.28
      2296297.41     13360593.32      2296256.97     13361032.45
#Sta/Elev= 30
  3876.2     350  4062.4  345.37  4156.4  343.04  4161.9     344  4179.4  342.94
  4280.8  341.32  4345.4  339.36  4421.9  338.27  4521.2  334.78  4533.5  334.61
  4650.4  333.35  4793.6   333.8    4869  333.15    4889  334.24  4967.7  332.68
  4974.3  331.71  4993.5  330.21  4996.2  329.71  4999.5  330.21  5019.8  332.07
  5066.4  331.14  5118.5  333.38  5254.3   333.3  5321.4  333.69  5449.5   336.3
  5627.7  342.88  5749.3  348.88  5850.7  352.19  5882.5  352.79  5995.9  355.13
#Mann= 14 ,-1 , 0
  3876.2      .1       0  4062.4     .05       0  4280.8      .1       0
  4521.2     .05       0  4533.5      .1       0  4650.4     .05       0
    4889     .12       0  4974.3     .05       0  4993.5     .03       0
  4999.5     .05       0  5254.3      .1       0  5627.7     .05       0
  5850.7      .1       0  5882.5     .05       0
Bank Sta=4967.7,5019.8
XS Rating Curve= 0 ,0
Exp/Cntr=0.3,0.1

Type RM Length L Ch R = 1 ,21823   ,92,92,92
BEGIN DESCRIPTION:
Mapping XS cf5f46c6
END DESCRIPTION:
XS GIS Cut Line= 3
       2296566.1     13359225.24        2296093.     13359967.45
      2296097.34     13360761.76
#Sta/Elev= 30
  4074.9  345.82  4079.5  345.72  4200.6   342.3  4363.8  337.37  4394.3  335.46
  4551.7  332.12  4582.2  332.07  4597.4     331  4622.2  331.03  4697.3  330.46
  4754.8  331.85  4827.6  332.09  4902.8  331.45  4915.6  331.03  4954.6  326.43
  5011.5  324.23  5014.2  323.73  5017.5  324.23  5044.5  326.18  5054.5  327.98
  5064.5  328.79  5074.5  332.91  5084.5     334  5124.5  331.22  5152.1  331.08
  5284.5  331.32  5354.5  332.27  5484.5  335.34  5524.5  337.22  5749.4  344.59
#Mann= 10 ,-1 , 0
  4074.9      .1       0  4079.5     .05       0  4200.6      .1       0
  4622.2     .05       0  4827.6     .12       0  4902.8     .05       0
  4954.6     .12       0  5011.5     .07       0  5017.5     .12       0
  5152.1      .1       0
Bank Sta=4915.6,5074.5
XS Rating Curve= 0 ,0
Exp/Cntr=0.3,0.1

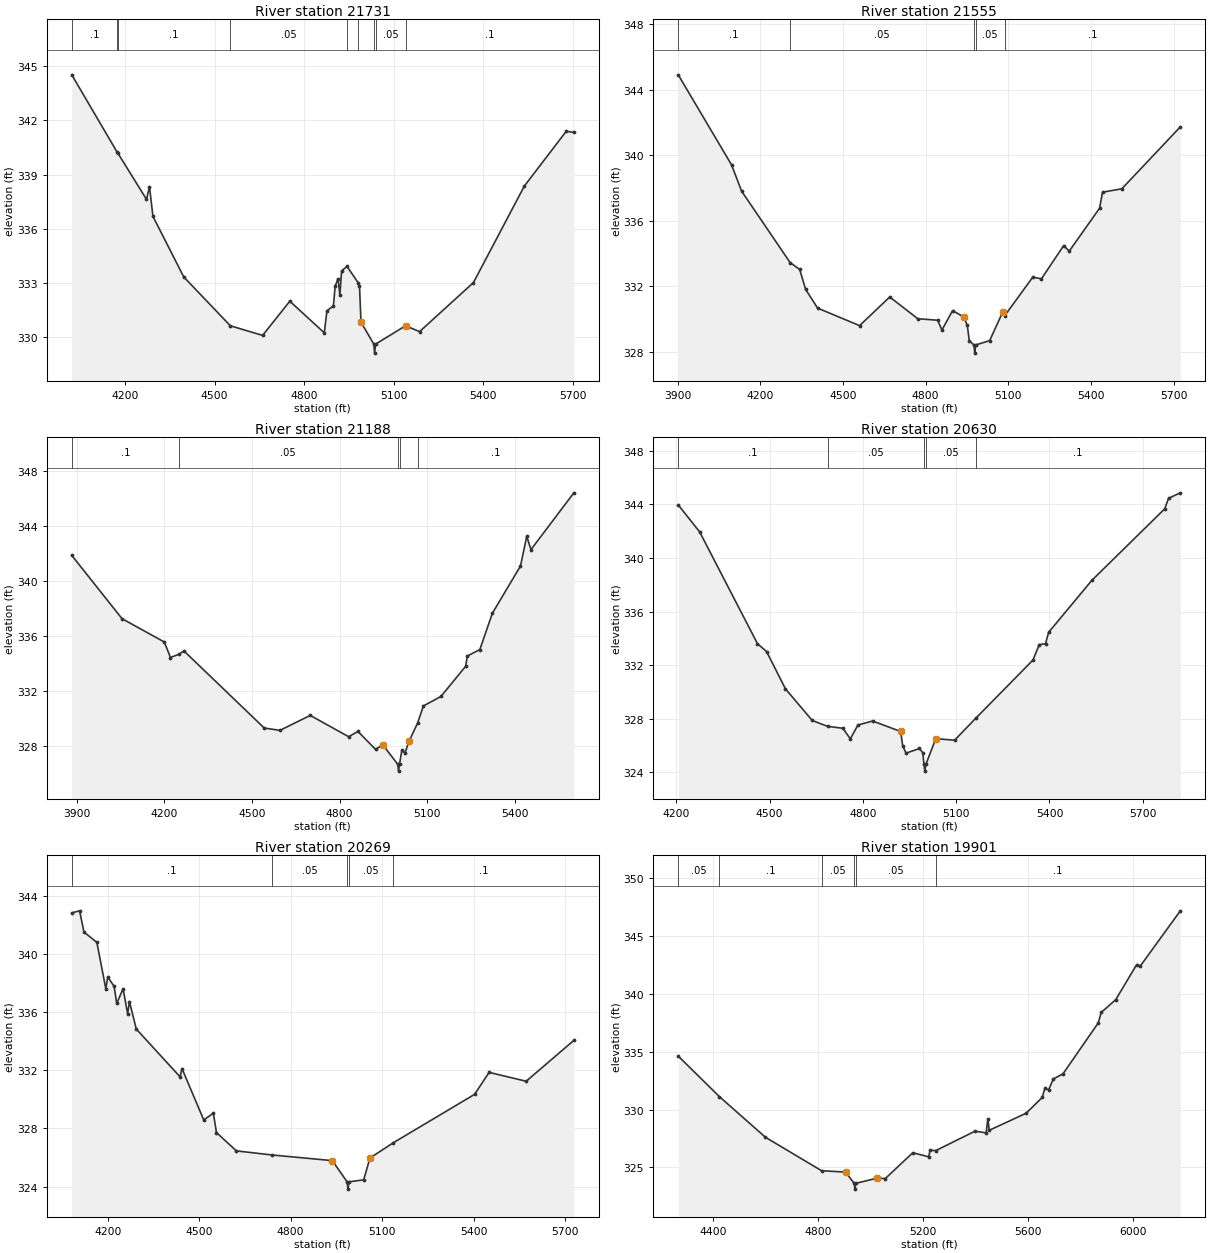
Type RM Length L Ch R = 1 ,21731   ,176,176,176
BEGIN DESCRIPTION:
Mapping XS cfe5a060
END DESCRIPTION:
XS GIS Cut Line= 3
      2296453.25     13359160.14      2296006.19     13359954.43
      2295958.47     13360722.29
#Sta/Elev= 30
    4022  344.51  4173.4  340.25  4175.6   340.2  4272.1  337.63  4282.2  338.33
  4293.7  336.69  4396.9  333.34    4553  330.64  4660.8  330.11    4752     332
  4867.4  330.25  4876.2  331.47  4897.9  331.74  4903.7  332.82  4913.3  333.25
  4919.6  332.35  4925.3  333.68  4943.5  333.92  4980.8  333.02  4985.2  332.86
  4990.2  330.84  5033.1  329.63  5035.8  329.13  5039.1  329.63  5139.3  330.64
  5186.4  330.32  5366.7  333.03    5537  338.36  5677.3  341.39  5702.8  341.33
#Mann= 9 ,-1 , 0
    4022      .1       0  4173.4     .05       0  4175.6      .1       0
    4553     .05       0  4943.5     .12       0  4980.8     .05       0
  5033.1     .03       0  5039.1     .05       0  5139.3      .1       0
Bank Sta=4990.2,5139.3
XS Rating Curve= 0 ,0
Exp/Cntr=0.3,0.1

Type RM Length L Ch R = 1 ,21555   ,367,367,367
BEGIN DESCRIPTION:
Mapping XS 081c0b88
END DESCRIPTION:
XS GIS Cut Line= 3
      2296353.43     13359055.97      2295841.26     13359889.33
       2295737.1     13360727.01
#Sta/Elev= 30
  3902.1  344.92  4095.6  339.42  4132.3  337.81  4308.3  333.45    4343  333.03
  4364.3  331.82  4407.9  330.67  4560.4   329.6  4669.7  331.35  4771.7  330.02
  4843.7  329.93  4859.1  329.33  4897.9  330.52  4938.2  330.13  4951.4  329.61
  4958.4  328.68  4975.5  328.42  4978.3  327.92  4981.5  328.42  5032.3  328.68
  5079.3  330.41  5087.3  330.21  5188.9  332.56  5220.4  332.46    5301  334.49
  5321.2  334.15  5431.3  336.77  5442.1  337.75  5512.2  337.96  5724.4  341.74
#Mann= 5 ,-1 , 0
  3902.1      .1       0  4308.3     .05       0  4975.5     .03       0
  4981.5     .05       0  5087.3      .1       0
Bank Sta=4938.2,5079.3
XS Rating Curve= 0 ,0
Exp/Cntr=0.3,0.1

Type RM Length L Ch R = 1 ,21188   ,558,558,558
BEGIN DESCRIPTION:
UNT029 IN SPCR 42.0
END DESCRIPTION:
XS GIS Cut Line= 3
      2296123.83     13358915.07      2295799.73     13359117.63
       2295319.4     13360367.63
#Sta/Elev= 30
  3882.1  341.87  4054.4  337.26  4199.3  335.56  4220.5  334.43  4248.8  334.66
  4266.6  334.91    4542  329.29  4595.7  329.12  4699.7  330.21  4831.2  328.66
  4863.4  329.04  4923.7  327.73  4948.3  328.07  4999.7  326.65  5002.4  326.15
  5005.7  326.65  5013.7  327.67  5024.1  327.46  5038.4  328.33  5067.7  329.65
  5087.7   330.9  5147.7  331.59  5232.4  333.79  5238.3  334.54  5281.2  335.01
    5324  337.65  5420.5   341.1  5441.9  343.26  5456.4  342.29  5603.4  346.43
#Mann= 5 ,-1 , 0
  3882.1      .1       0  4248.8     .05       0  4999.7     .03       0
  5005.7     .05       0  5067.7      .1       0
Bank Sta=4948.3,5038.4
XS Rating Curve= 0 ,0
Exp/Cntr=0.3,0.1

Type RM Length L Ch R = 1 ,20630   ,361,361,361
BEGIN DESCRIPTION:
UNT029 IN SPCR 41.0
END DESCRIPTION:
XS GIS Cut Line= 3
      2295387.72     13358746.85      2295087.72     13359496.85
      2295187.72     13360296.85
#Sta/Elev= 30
  4206.6  343.97  4275.3  341.96  4461.1  333.62  4490.7  333.02  4551.3  330.24
  4637.4  327.88  4686.8  327.44  4735.7   327.3  4759.9  326.51  4784.2  327.54
  4831.3  327.84  4921.5  327.06  4928.2  325.99    4939  325.44  4982.1  325.79
  4992.8  325.47  4996.6   324.6  4999.3   324.1  5002.6   324.6  5034.5  326.52
    5095  326.41  5163.2  328.05  5346.9  332.39  5367.1  333.54  5387.3  333.61
  5397.3  334.46  5535.9  338.33  5770.2  343.67  5782.8  344.46  5820.6  344.87
#Mann= 5 ,-1 , 0
  4206.6      .1       0  4686.8     .05       0  4996.6     .03       0
  5002.6     .05       0  5163.2      .1       0
Bank Sta=4921.5,5034.5
XS Rating Curve= 0 ,0
Exp/Cntr=0.3,0.1

Type RM Length L Ch R = 1 ,20269   ,368,368,368
BEGIN DESCRIPTION:
UNT029 IN SPCR 40.0
END DESCRIPTION:
XS GIS Cut Line= 3
      2295139.99     13358504.22      2294885.38       13358863.
       2294607.6     13360037.76
#Sta/Elev= 30
    4082  342.83  4107.7  342.97    4122  341.51  4164.3   340.8  4193.8   337.6
    4200  338.42  4220.9  337.78  4229.5   336.6  4250.4  337.61  4265.2  335.89
  4271.3  336.72  4293.7  334.84  4437.4  331.55  4443.6  332.12  4514.9  328.59
  4546.5  329.05  4556.7  327.72    4622  326.46  4738.6  326.18  4936.9  325.79
  4985.3  324.33  4988.1  323.83  4991.3  324.33  5039.7  324.47  5060.2  325.97
  5136.9  327.02  5403.6  330.35    5451  331.86  5572.7  331.25  5729.1  334.06
#Mann= 5 ,-1 , 0
    4082      .1       0  4738.6     .05       0  4985.3     .03       0
  4991.3     .05       0  5136.9      .1       0
Bank Sta=4936.9,5060.2
XS Rating Curve= 0 ,0
Exp/Cntr=0.3,0.1

Type RM Length L Ch R = 1 ,19901   ,600,600,600
BEGIN DESCRIPTION:
UNT029 IN SPCR 39.0
END DESCRIPTION:
XS GIS Cut Line= 2
      2294738.65     13358438.15      2294065.04      13360229.8
#Sta/Elev= 30
  4267.5  334.61  4424.7  331.11  4599.8  327.61  4813.9  324.72  4905.6   324.6
  4938.2  323.63    4941  323.13  4944.2  323.63  5026.6  324.08  5056.8  324.04
  5161.7  326.27  5222.2  325.92  5227.6  326.48  5249.8  326.46  5398.6  328.13
  5441.3  327.99    5448  329.19  5453.3  328.21  5593.8  329.68    5655  331.04
  5665.6  331.85  5679.2  331.69  5697.7  332.64  5734.3  333.08  5868.6  337.47
  5880.1  338.38  5935.3  339.48  6015.3  342.51  6028.9  342.38  6181.6  347.15
#Mann= 6 ,-1 , 0
  4267.5     .05       0  4424.7      .1       0  4813.9     .05       0
  4938.2     .03       0  4944.2     .05       0  5249.8      .1       0
Bank Sta=4905.6,5026.6
XS Rating Curve= 0 ,0
Exp/Cntr=0.3,0.1