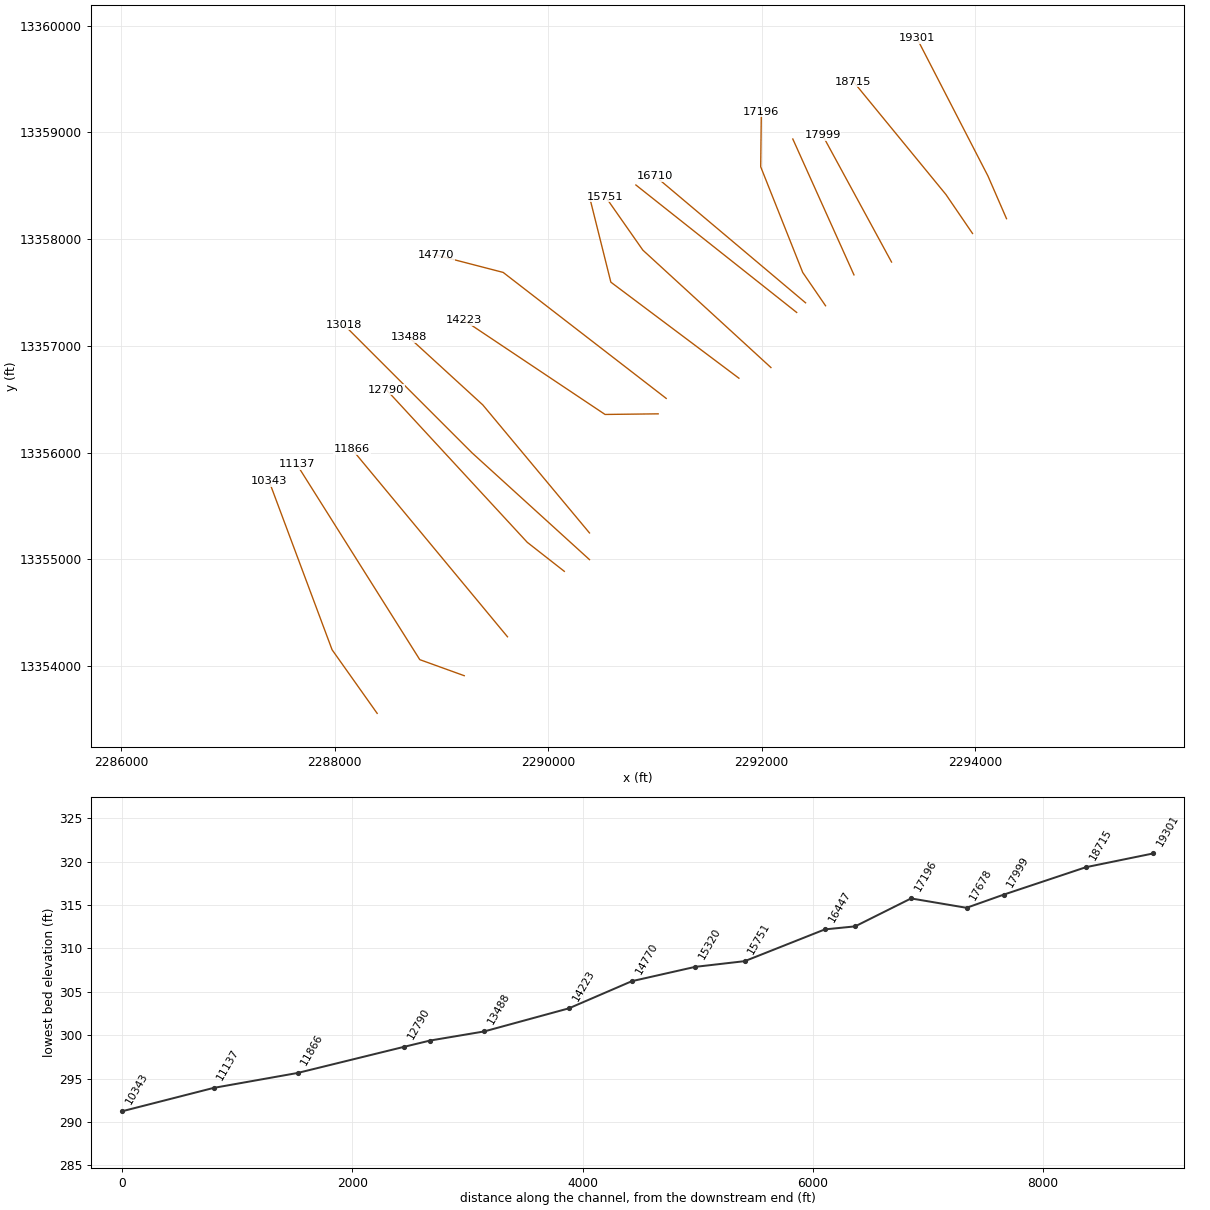
HEC-RAS study UNT029 IN SPCR.prj: UNT029 IN SPCR Base Level Engineering

--- UNT029 IN SPCR.g01 (geometry) --- (continued)

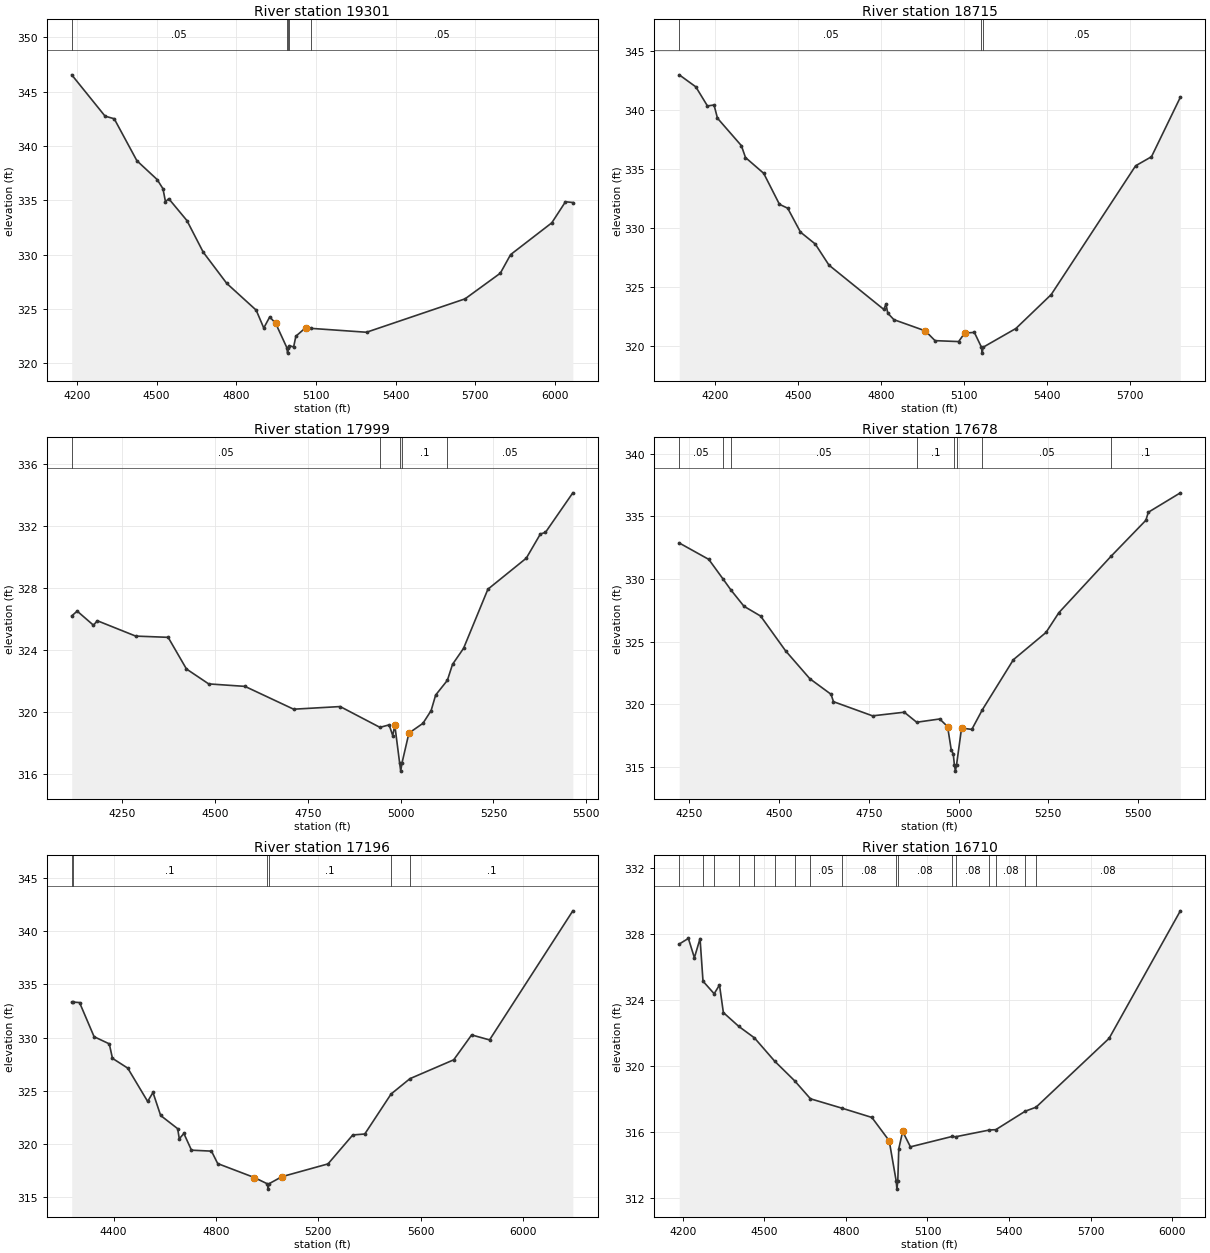
Type RM Length L Ch R = 1 ,19301   ,586,586,586
BEGIN DESCRIPTION:
UNT029 IN SPCR 38.0
END DESCRIPTION:
XS GIS Cut Line= 3
       2294295.1     13358191.71      2294121.49     13358591.01
      2293455.98     13359881.51
#Sta/Elev= 30
  4180.3  346.54  4305.9  342.74  4340.4   342.5  4425.8  338.64  4502.1  336.91
  4523.9  336.07  4533.4  334.88  4545.8  335.15  4614.2  333.14  4675.7  330.23
  4764.3  327.36  4875.1   324.9  4903.6  323.26  4926.1  324.28  4948.6  323.68
  4990.6  321.45  4993.3  320.95  4996.6  321.45  5000.3  321.63  5016.1  321.52
  5024.6  322.51  5061.1  323.28  5079.8  323.23  5290.6  322.87  5661.7  325.94
  5794.6   328.3  5833.3  330.01  5988.4  332.93    6040  334.87  6067.7   334.8
#Mann= 5 ,-1 , 0
  4180.3     .05       0  4990.6     .03       0  4996.6     .05       0
  5000.3      .1       0  5079.8     .05       0
Bank Sta=4948.6,5061.1
XS Rating Curve= 0 ,0
Exp/Cntr=0.3,0.1

Type RM Length L Ch R = 1 ,18715   ,716,716,716
BEGIN DESCRIPTION:
UNT029 IN SPCR 37.0
END DESCRIPTION:
XS GIS Cut Line= 3
      2293976.82      13358052.8      2293727.97      13358417.4
      2292859.88     13359476.46
#Sta/Elev= 30
  4069.8  342.98  4129.7  341.96  4171.7  340.34  4195.5  340.42  4207.9   339.3
  4294.3  336.97  4309.2  335.96    4375  334.62  4431.9  331.99  4461.7  331.66
  4507.9  329.63  4561.3  328.62  4610.8  326.83  4808.9  323.07  4816.8  323.52
  4823.3  322.75  4845.5   322.2  4958.9  321.25  4994.1  320.42  5079.4  320.34
    5101  321.06  5136.2  321.12  5161.9  319.86  5164.6  319.36  5167.9  319.86
  5286.2  321.45  5413.9  324.33  5718.9  335.26  5776.3  336.03  5880.6  341.08
#Mann= 3 ,-1 , 0
  4069.8     .05       0  5161.9     .03       0  5167.9     .05       0
Bank Sta=4958.9,5101
XS Rating Curve= 0 ,0
Exp/Cntr=0.3,0.1

Type RM Length L Ch R = 1 ,17999   ,321,321,321
BEGIN DESCRIPTION:
UNT029 IN SPCR 35.0
END DESCRIPTION:
XS GIS Cut Line= 2
      2293217.81     13357785.36      2292572.63     13358971.66
#Sta/Elev= 30
  4113.5  326.19  4128.2   326.5  4172.1  325.59  4182.4  325.88  4285.9  324.89
  4373.3  324.81  4422.7  322.77  4482.6  321.81  4580.4  321.65  4711.5  320.18
  4836.9  320.35  4944.1  319.01  4968.9  319.17  4978.5  318.48  4984.2  319.14
  4997.3  316.69  5000.1  316.19  5003.3  316.69  5022.2  318.64    5060  319.27
    5082  320.09  5094.2  321.09  5125.8  322.04  5139.7  323.07  5169.4   324.1
    5235  327.91  5338.5  329.91  5376.5  331.47  5390.1  331.57  5463.9  334.12
#Mann= 5 ,-1 , 0
  4113.5     .05       0  4944.1      .1       0  4997.3     .07       0
  5003.3      .1       0  5125.8     .05       0
Bank Sta=4984.2,5022.2
XS Rating Curve= 0 ,0
Exp/Cntr=0.3,0.1

Type RM Length L Ch R = 1 ,17678   ,482,482,482
BEGIN DESCRIPTION:
UNT029 IN SPCR 34.0
END DESCRIPTION:
XS GIS Cut Line= 2
      2292865.72     13357665.04      2292292.77     13358938.26
#Sta/Elev= 30
  4221.8  332.88  4304.1  331.57  4343.5  330.02  4366.3  329.11  4402.2  327.83
  4448.5  327.05    4518  324.28  4585.7  322.05  4644.7  320.81  4651.5  320.22
  4760.4  319.09  4848.8  319.38  4883.3  318.58  4947.5  318.84  4969.5  318.23
  4979.7  316.36  4985.2  316.06  4988.4  315.18  4991.2  314.68  4994.4  315.18
  5008.4  318.11    5037  318.01  5066.2  319.57  5152.8  323.57  5243.6  325.74
  5279.5  327.32  5424.9  331.82  5521.9  334.69  5528.7  335.33    5618  336.88
#Mann= 8 ,-1 , 0
  4221.8     .05       0  4343.5      .1       0  4366.3     .05       0
  4883.3      .1       0  4988.4     .07       0  4994.4      .1       0
  5066.2     .05       0  5424.9      .1       0
Bank Sta=4969.5,5008.4
XS Rating Curve= 0 ,0
Exp/Cntr=0.3,0.1

Type RM Length L Ch R = 1 ,17196   ,486,486,486
BEGIN DESCRIPTION:
UNT029 IN SPCR 33.0
END DESCRIPTION:
XS GIS Cut Line= 4
      2292599.48     13357375.76      2292385.38     13357688.23
      2291991.86     13358677.81      2291997.64     13359192.34
#Sta/Elev= 30
  4236.7  333.34  4239.9  333.34  4267.3  333.29  4324.2  330.08  4383.5  329.41
  4395.9  328.05  4455.6  327.13  4533.4     324  4554.3  324.84  4584.2  322.68
  4650.7  321.44  4657.1  320.49    4675  320.99  4704.7  319.42  4782.9  319.33
  4807.2  318.16  4950.2  316.85  5001.2  316.26  5003.9  315.76  5007.2  316.26
  5058.1  316.93  5238.2  318.13    5335  320.85  5381.9  320.94  5484.8   324.7
  5558.5  326.14  5729.5  327.91  5799.5  330.25  5869.5  329.78    6195  341.91
#Mann= 6 ,-1 , 0
  4236.7     .05       0  4239.9      .1       0  5001.2     .07       0
  5007.2      .1       0  5484.8     .05       0  5558.5      .1       0
Bank Sta=4950.2,5058.1
XS Rating Curve= 0 ,0
Exp/Cntr=0.3,0.1

Type RM Length L Ch R = 1 ,16710   ,263,263,263
BEGIN DESCRIPTION:
Mapping XS b0dbf2c2
END DESCRIPTION:
XS GIS Cut Line= 2
      2292412.25     13357403.41      2291002.62     13358590.83
#Sta/Elev= 30
  4187.1  327.38  4220.7  327.72  4242.8  326.55  4263.6  327.71  4274.5  325.13
  4315.5  324.37  4335.1   324.9  4349.4  323.23  4406.3  322.39  4463.5   321.7
    4538  320.29  4611.5   319.1  4669.7  318.01  4785.8  317.44  4895.6  316.88
  4959.3  315.47  4984.9  313.04  4987.7  312.54  4990.9  313.04  4994.5  314.98
  5008.8  316.03  5037.4   315.1    5191  315.73  5203.4  315.71  5328.2  316.12
  5351.4  316.14  5459.9  317.26  5499.4   317.5  5768.2  321.67  6030.2  329.39
#Mann= 17 ,-1 , 0
  4187.1     .08       0  4274.5     .05       0  4315.5     .08       0
  4406.3     .05       0  4463.5     .08       0    4538     .05       0
  4611.5     .08       0  4669.7     .05       0  4785.8     .08       0
  4984.9     .07       0  4990.9     .08       0    5191      .1       0
  5203.4     .08       0  5328.2      .1       0  5351.4     .08       0
  5459.9      .1       0  5499.4     .08       0
Bank Sta=4959.3,5008.8
XS Rating Curve= 0 ,0
Exp/Cntr=0.3,0.1

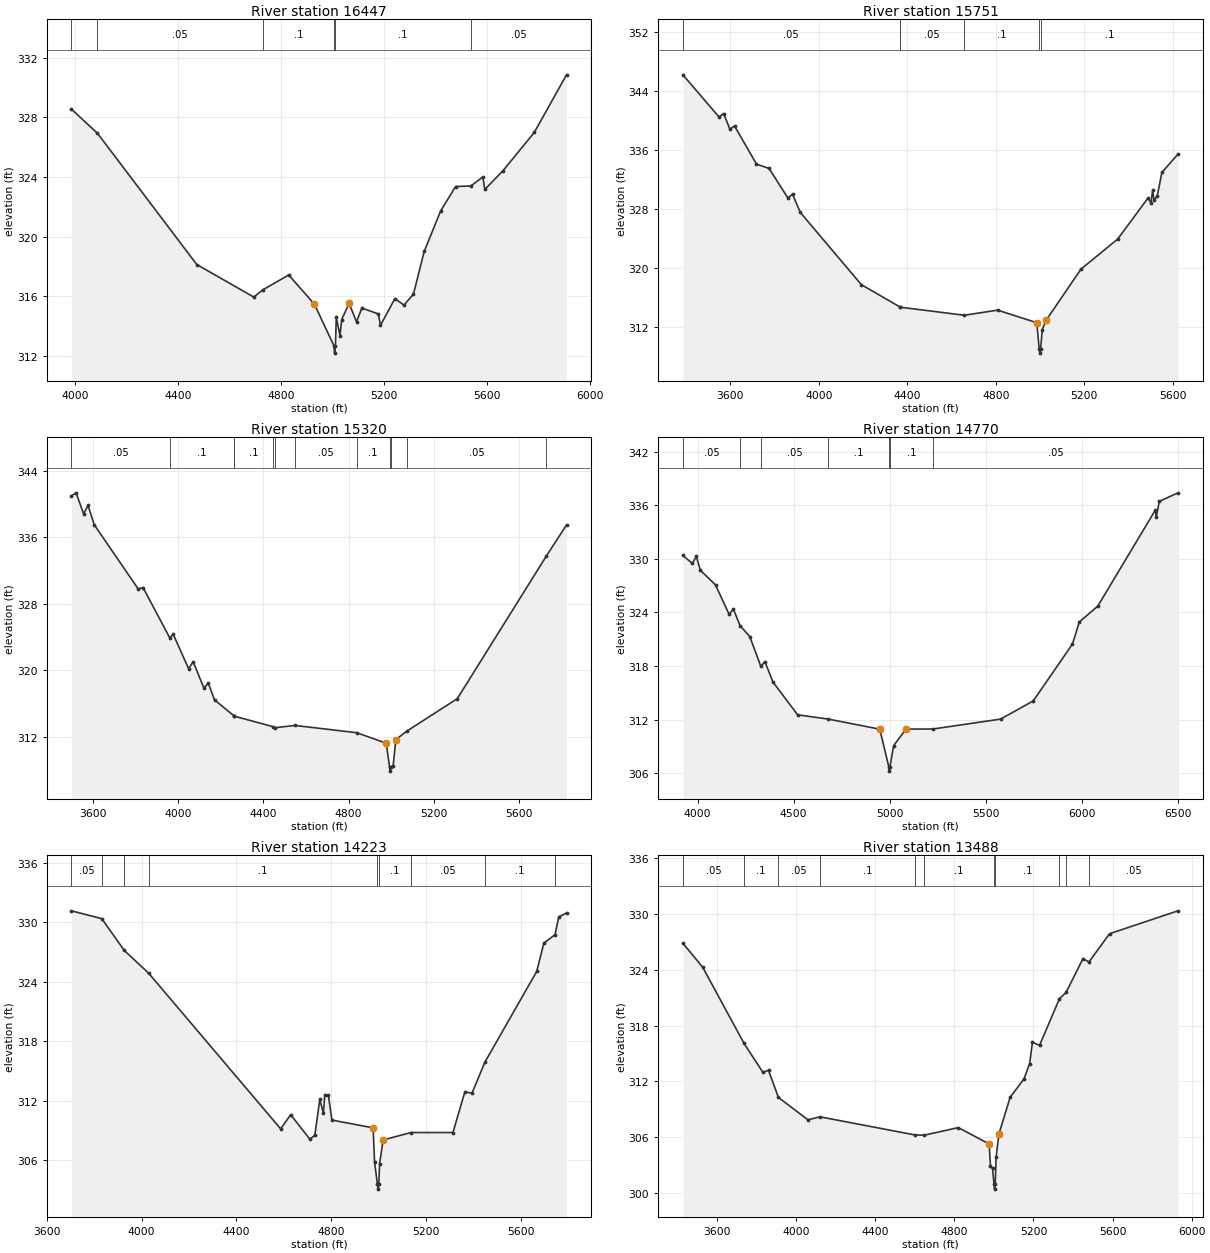
Type RM Length L Ch R = 1 ,16447   ,696,696,696
BEGIN DESCRIPTION:
Mapping XS 0d0a4698
END DESCRIPTION:
XS GIS Cut Line= 2
       2292328.9     13357313.14      2290822.35     13358507.27
#Sta/Elev= 30
  3985.6  328.55  4086.8  326.93  4472.4  318.13  4693.6  315.95  4728.5  316.43
  4829.3  317.43  4929.2  315.47  5004.7  312.69  5007.5  312.19  5010.7  312.69
  5014.1  314.58  5028.5  313.37  5034.9  314.43  5063.7  315.53  5092.6  314.29
  5113.4  315.21  5177.5  314.82  5185.6  314.05  5241.6  315.85  5276.9  315.41
  5313.8  316.15  5355.4  319.01  5419.5  321.73  5477.2  323.36  5536.8   323.4
  5582.9     324    5591  323.17  5661.4  324.42  5783.3     327    5908  330.85
#Mann= 6 ,-1 , 0
  3985.6     .08       0  4086.8     .05       0  4728.5      .1       0
  5004.7     .07       0  5010.7      .1       0  5536.8     .05       0
Bank Sta=4929.2,5063.7
XS Rating Curve= 0 ,0
Exp/Cntr=0.3,0.1

Type RM Length L Ch R = 1 ,15751   ,431,431,431
BEGIN DESCRIPTION:
UNT029 IN SPCR 30.0
END DESCRIPTION:
XS GIS Cut Line= 3
      2292087.74     13356796.83      2290887.72     13357896.85
      2290537.74     13358396.82
#Sta/Elev= 30
  3385.2  346.21    3548  340.52  3569.3  340.96  3597.7  338.85  3618.6  339.29
  3717.9  334.12  3774.6  333.54  3859.7  329.55  3880.7  330.05  3915.8  327.58
  4192.1   317.8  4364.7  314.81  4367.3  314.75  4657.4  313.66  4808.1  314.35
  4985.1  312.65  4996.2  309.03    4999  308.53  5002.2  309.03  5009.7  311.71
  5026.6  312.95  5184.4  319.89    5351  323.98  5487.9  329.53  5501.4  328.87
  5508.8  330.61  5514.9  329.23  5529.7  329.82  5550.6  332.99  5623.4  335.48
#Mann= 6 ,-1 , 0
  3385.2     .05       0  4364.7      .1       0  4367.3     .05       0
  4657.4      .1       0  4996.2     .07       0  5002.2      .1       0
Bank Sta=4985.1,5026.6
XS Rating Curve= 0 ,0
Exp/Cntr=0.3,0.1

Type RM Length L Ch R = 1 ,15320   ,550,550,550
BEGIN DESCRIPTION:
UNT029 IN SPCR 29.0
END DESCRIPTION:
XS GIS Cut Line= 3
       2291787.7     13356696.87      2290587.72     13357596.85
      2290387.72     13358396.86
#Sta/Elev= 30
  3498.2  340.95    3520  341.32  3555.5   338.8  3576.3  339.81  3605.5  337.48
  3811.7  329.77  3834.6  329.93  3959.7   323.9  3976.3  324.32  4048.2  320.19
    4070  321.02    4120  317.86  4140.9  318.43    4170  316.44  4263.4  314.47
  4263.8  314.47  4445.1  313.21  4455.2  313.09    4548  313.36  4837.1  312.49
  4976.3  311.23    4992  308.37  4994.8  307.87    4998  308.37  5008.5  308.45
  5021.4  311.66    5072  312.66    5310  316.58  5726.8  333.67  5822.8  337.46
#Mann= 12 ,-1 , 0
  3498.2     .05       0  3959.7      .1       0  4263.4     .05       0
  4263.8      .1       0  4445.1     .05       0  4455.2      .1       0
    4548     .05       0  4837.1      .1       0    4992     .07       0
    4998      .1       0    5072     .05       0  5726.8      .1       0
Bank Sta=4976.3,5021.4
XS Rating Curve= 0 ,0
Exp/Cntr=0.3,0.1

Type RM Length L Ch R = 1 ,14770   ,547,547,547
BEGIN DESCRIPTION:
UNT029 IN SPCR 28.0
END DESCRIPTION:
XS GIS Cut Line= 3
      2291106.42     13356507.69      2289578.66     13357688.23
      2288953.66     13357850.27
#Sta/Elev= 30
  3923.9  330.39  3972.8   329.5  3993.9  330.28  4014.8  328.73  4093.6  327.09
  4164.2   323.8  4186.9  324.37  4221.5  322.52    4272   321.3  4329.5  317.96
  4350.8  318.49  4392.4  316.21    4521  312.53  4678.9  312.06  4948.5  310.92
  4995.3  306.72    4998  306.22  5001.3  306.72  5020.9  309.09  5084.9  310.93
  5224.4  310.94    5577  312.05  5747.2  314.09  5951.3  320.47  5986.7  322.94
  6082.9  324.71  6382.2  335.47  6387.4  334.73  6403.1  336.45  6500.3  337.41
#Mann= 7 ,-1 , 0
  3923.9     .05       0  4221.5      .1       0  4329.5     .05       0
  4678.9      .1       0  4995.3     .07       0  5001.3      .1       0
  5224.4     .05       0
Bank Sta=4948.5,5084.9
XS Rating Curve= 0 ,0
Exp/Cntr=0.3,0.1

Type RM Length L Ch R = 1 ,14223   ,735,735,735
BEGIN DESCRIPTION:
UNT029 IN SPCR 27.0
END DESCRIPTION:
XS GIS Cut Line= 3
      2291031.24       13356363.      2290533.53     13356357.21
      2289208.83     13357242.27
#Sta/Elev= 30
  3703.3  331.17  3831.4  330.38  3926.6  327.17  4029.4  324.88  4587.1  309.17
  4629.2   310.6  4710.3  308.13  4731.3  308.53  4752.3  312.15  4767.3  310.75
  4773.4  312.62  4788.4  312.59  4803.4  310.06  4977.6  309.27  4983.6  305.81
  4995.6  303.59  4998.4  303.09  5001.6  303.59  5004.6  305.61  5019.6  308.05
  5137.3   308.8  5314.5   308.8    5365  312.91    5395  312.77  5449.3  315.89
  5668.4  325.06  5698.4  327.91  5745.5  328.76  5761.5  330.55  5794.2  330.95
#Mann= 9 ,-1 , 0
  3703.3     .05       0  3831.4      .1       0  3926.6     .05       0
  4029.4      .1       0  4995.6     .07       0  5001.6      .1       0
  5137.3     .05       0  5449.3      .1       0  5745.5     .05       0
Bank Sta=4977.6,5019.6
XS Rating Curve= 0 ,0
Exp/Cntr=0.3,0.1

Type RM Length L Ch R = 1 ,13488   ,470,470,470
BEGIN DESCRIPTION:
UNT029 IN SPCR 25.0
END DESCRIPTION:
XS GIS Cut Line= 3
      2290387.69     13355246.89      2289387.72     13356446.85
      2288693.71     13357082.03
#Sta/Elev= 30
  3428.2  326.85  3527.7   324.3  3737.4  316.09  3832.3  312.99    3861  313.19
  3911.1  310.29  4060.1  307.88  4121.6   308.2  4599.2  306.26  4646.6  306.22
  4820.3  307.04  4976.5  305.29    4983  302.93  4993.6  302.65  5001.1  300.93
  5003.8  300.43  5007.1  300.93  5011.5  303.87  5025.7  306.36  5082.4  310.29
  5152.9  312.29  5181.1  313.93  5195.2  316.21    5231  315.88  5331.8   320.9
  5365.3  321.57  5450.5   325.2  5481.1  324.85    5585  327.88    5931  330.34
#Mann= 11 ,-1 , 0
  3428.2     .05       0  3737.4      .1       0  3911.1     .05       0
  4121.6      .1       0  4599.2     .05       0  4646.6      .1       0
  5001.1     .07       0  5007.1      .1       0  5331.8     .05       0
  5365.3      .1       0  5481.1     .05       0
Bank Sta=4976.5,5025.7
XS Rating Curve= 0 ,0
Exp/Cntr=0.3,0.1

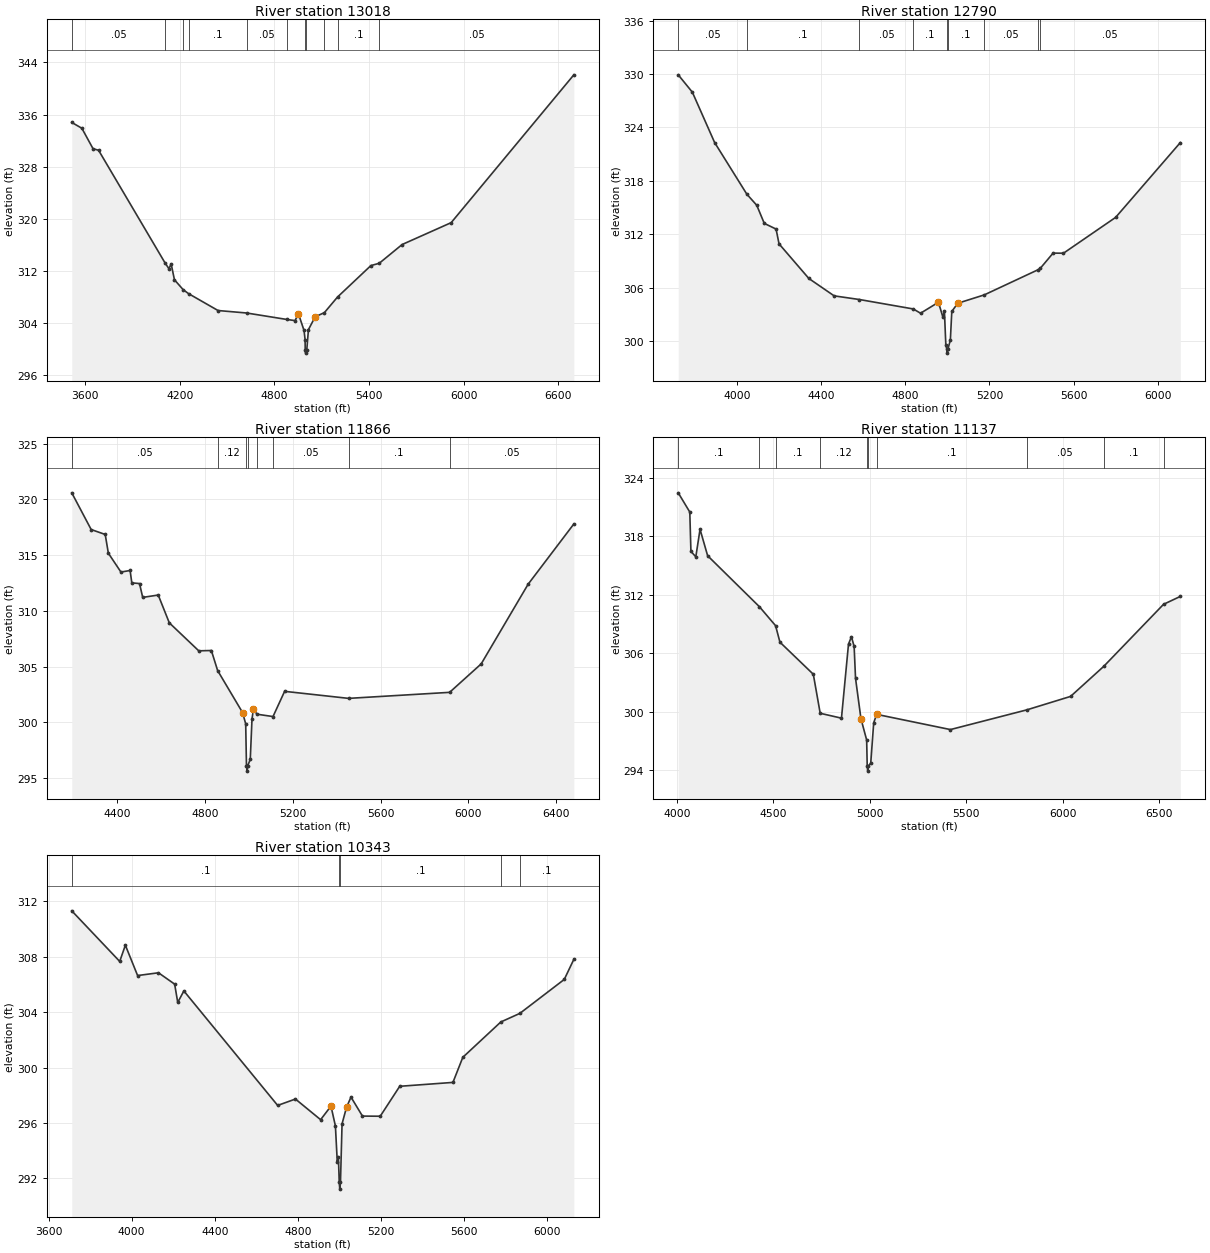
Type RM Length L Ch R = 1 ,13018   ,228,228,228
BEGIN DESCRIPTION:
UNT029 IN SPCR 24.0
END DESCRIPTION:
XS GIS Cut Line= 3
      2290387.74     13354996.83      2289287.72     13355996.85
      2288087.72     13357196.86
#Sta/Elev= 30
  3515.4  334.79  3579.3   333.9  3650.2  330.76  3685.4  330.52  4106.3  313.25
  4131.4  312.34  4145.6  313.07  4166.5  310.64  4221.8  309.12    4256  308.51
  4442.9  305.92  4624.2  305.54  4878.6  304.55  4931.4  304.37  4952.4  305.44
  4988.2  302.86  4994.9  301.47  4995.7  299.88  4998.4  299.38  5001.7  299.88
  5005.6  299.88  5016.2  302.99  5058.6  304.95  5117.4   305.6  5200.5  307.99
  5412.2  312.82    5465  313.17  5610.2  316.05  5921.3  319.41  6699.1   342.1
#Mann= 11 ,-1 , 0
  3515.4     .05       0  4106.3      .1       0  4221.8     .05       0
    4256      .1       0  4624.2     .05       0  4878.6      .1       0
  4995.7     .07       0  5001.7      .1       0  5117.4     .05       0
  5200.5      .1       0    5465     .05       0
Bank Sta=4952.4,5058.6
XS Rating Curve= 0 ,0
Exp/Cntr=0.3,0.1

Type RM Length L Ch R = 1 ,12790   ,924,924,924
BEGIN DESCRIPTION:
UNT029 IN SPCR 23.0
END DESCRIPTION:
XS GIS Cut Line= 3
      2290151.56     13354887.32      2289804.36     13355159.29
      2288484.93     13356588.68
#Sta/Elev= 30
    3721   329.9  3788.1  327.95  3893.9   322.3    4047   316.5  4094.3  315.25
  4129.9  313.22    4186  312.58  4200.1  310.92  4341.9  307.03  4462.1  305.08
    4582  304.67  4838.1  303.61  4872.7  303.13  4957.7  304.36  4978.7  302.71
  4986.1  303.36  4992.9  299.55  4997.2  299.15    5000  298.65  5003.2  299.15
  5014.4  300.12  5021.2  303.33  5049.6  304.25  5175.6  305.19    5430     308
  5441.7  308.17  5502.6  309.88    5552  309.87  5799.8  313.89  6107.3  322.29
#Mann= 9 ,-1 , 0
    3721     .05       0    4047      .1       0    4582     .05       0
  4838.1      .1       0  4997.2     .07       0  5003.2      .1       0
  5175.6     .05       0    5430      .1       0  5441.7     .05       0
Bank Sta=4957.7,5049.6
XS Rating Curve= 0 ,0
Exp/Cntr=0.3,0.1

Type RM Length L Ch R = 1 ,11866   ,729,729,729
BEGIN DESCRIPTION:
UNT029 IN SPCR 22.0
END DESCRIPTION:
XS GIS Cut Line= 2
      2289619.16      13354273.9      2288160.83     13356033.15
#Sta/Elev= 30
  4194.5  320.58  4282.8  317.29  4346.7  316.85    4361  315.17  4418.3  313.48
    4460  313.62  4467.8  312.51  4502.9  312.45  4517.3  311.21    4588  311.42
  4638.4  308.93  4772.5  306.42  4829.8  306.45  4858.4  304.65  4971.8  300.89
  4986.1  299.88  4989.6  296.14  4992.4  295.64  4995.6  296.14  5006.9  296.69
  5014.8  300.32  5021.3  301.18  5037.6  300.74  5110.4  300.53  5163.2  302.79
  5454.4  302.16  5914.2   302.7  6057.9  305.25  6271.5  312.39  6479.6  317.79
#Mann= 8 ,-1 , 0
  4194.5     .05       0  4858.4     .12       0  4989.6     .07       0
  4995.6     .12       0  5037.6      .1       0  5110.4     .05       0
  5454.4      .1       0  5914.2     .05       0
Bank Sta=4971.8,5021.3
XS Rating Curve= 0 ,0
Exp/Cntr=0.3,0.1

Type RM Length L Ch R = 1 ,11137   ,794,794,794
BEGIN DESCRIPTION:
UNT029 IN SPCR 20.0
END DESCRIPTION:
XS GIS Cut Line= 3
      2289214.09     13353909.29      2288797.41     13354059.76
       2287645.8     13355888.45
#Sta/Elev= 30
  4006.2  322.45  4066.1  320.48    4072  316.45  4097.4  315.89  4119.3  318.71
  4158.7     316  4427.5  310.77  4511.1  308.83  4533.7  307.14  4706.8  303.85
  4742.5  299.85  4852.8  299.35  4889.3  306.94  4904.6   307.7  4918.5   306.7
  4925.8  303.43  4953.9  299.29  4983.5  297.11  4986.4  294.42  4989.1  293.92
  4992.4  294.42  5004.7  294.75    5020  298.87  5035.2  299.74  5417.9  298.18
  5814.2   300.2  6041.2  301.58  6213.2  304.66  6523.3  311.02  6610.3  311.83
#Mann= 10 ,-1 , 0
  4006.2      .1       0  4427.5     .05       0  4511.1      .1       0
  4742.5     .12       0  4986.4     .07       0  4992.4     .12       0
  5035.2      .1       0  5814.2     .05       0  6213.2      .1       0
  6523.3     .05       0
Bank Sta=4953.9,5035.2
XS Rating Curve= 0 ,0
Exp/Cntr=0.3,0.1

Type RM Length L Ch R = 1 ,10343   ,314,314,314
BEGIN DESCRIPTION:
UNT029 IN SPCR 19.0
END DESCRIPTION:
XS GIS Cut Line= 3
      2288398.08     13353556.32      2287975.65     13354152.35
      2287385.44     13355732.05
#Sta/Elev= 30
  3711.7  311.31  3942.5  307.66  3969.7  308.83  4028.6  306.64  4129.1  306.84
    4207  306.02  4221.8   304.7  4251.3  305.53  4702.8  297.27  4788.4  297.73
  4909.6  296.24  4959.5  297.22  4980.8  295.79  4989.8   293.2  4995.2  293.57
  4999.2  291.73  5001.9  291.23  5005.2  291.73  5012.8  295.94  5034.2  297.13
  5055.8  297.87    5111   296.5  5196.6  296.49  5290.4  298.65  5546.6  298.93
  5594.1  300.74    5777  303.29  5868.7  303.91  6082.5  306.36  6128.6  307.81
#Mann= 5 ,-1 , 0
  3711.7      .1       0  4999.2     .07       0  5005.2      .1       0
    5777     .05       0  5868.7      .1       0
Bank Sta=4959.5,5034.2
XS Rating Curve= 0 ,0
Exp/Cntr=0.3,0.1