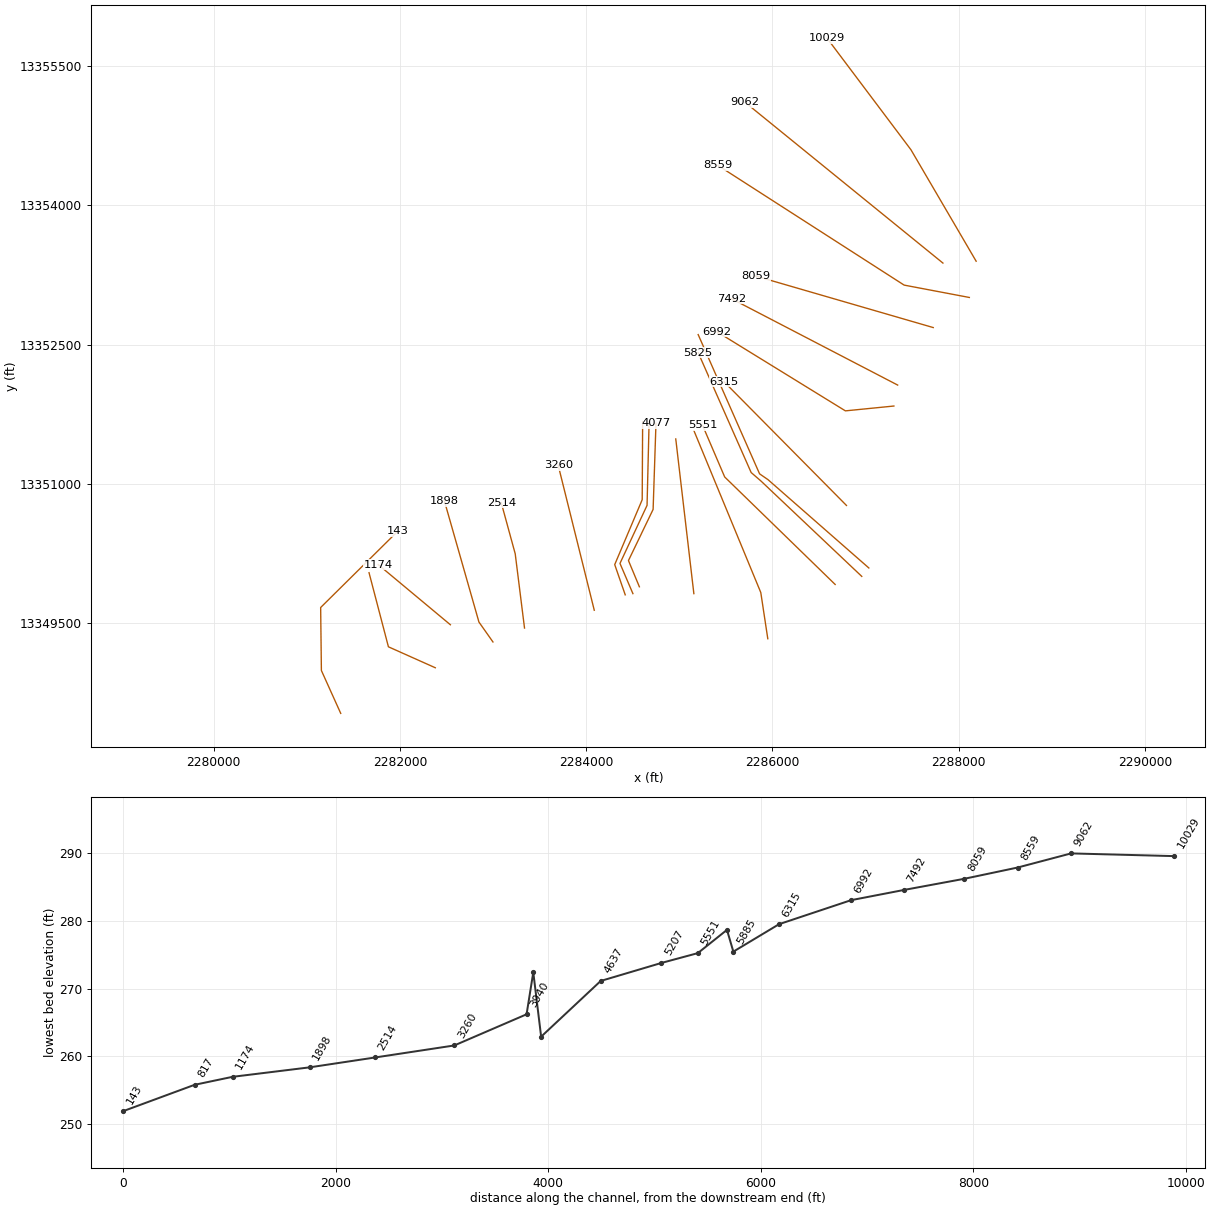
HEC-RAS study UNT029 IN SPCR.prj: UNT029 IN SPCR Base Level Engineering

--- UNT029 IN SPCR.g01 (geometry) --- (continued)

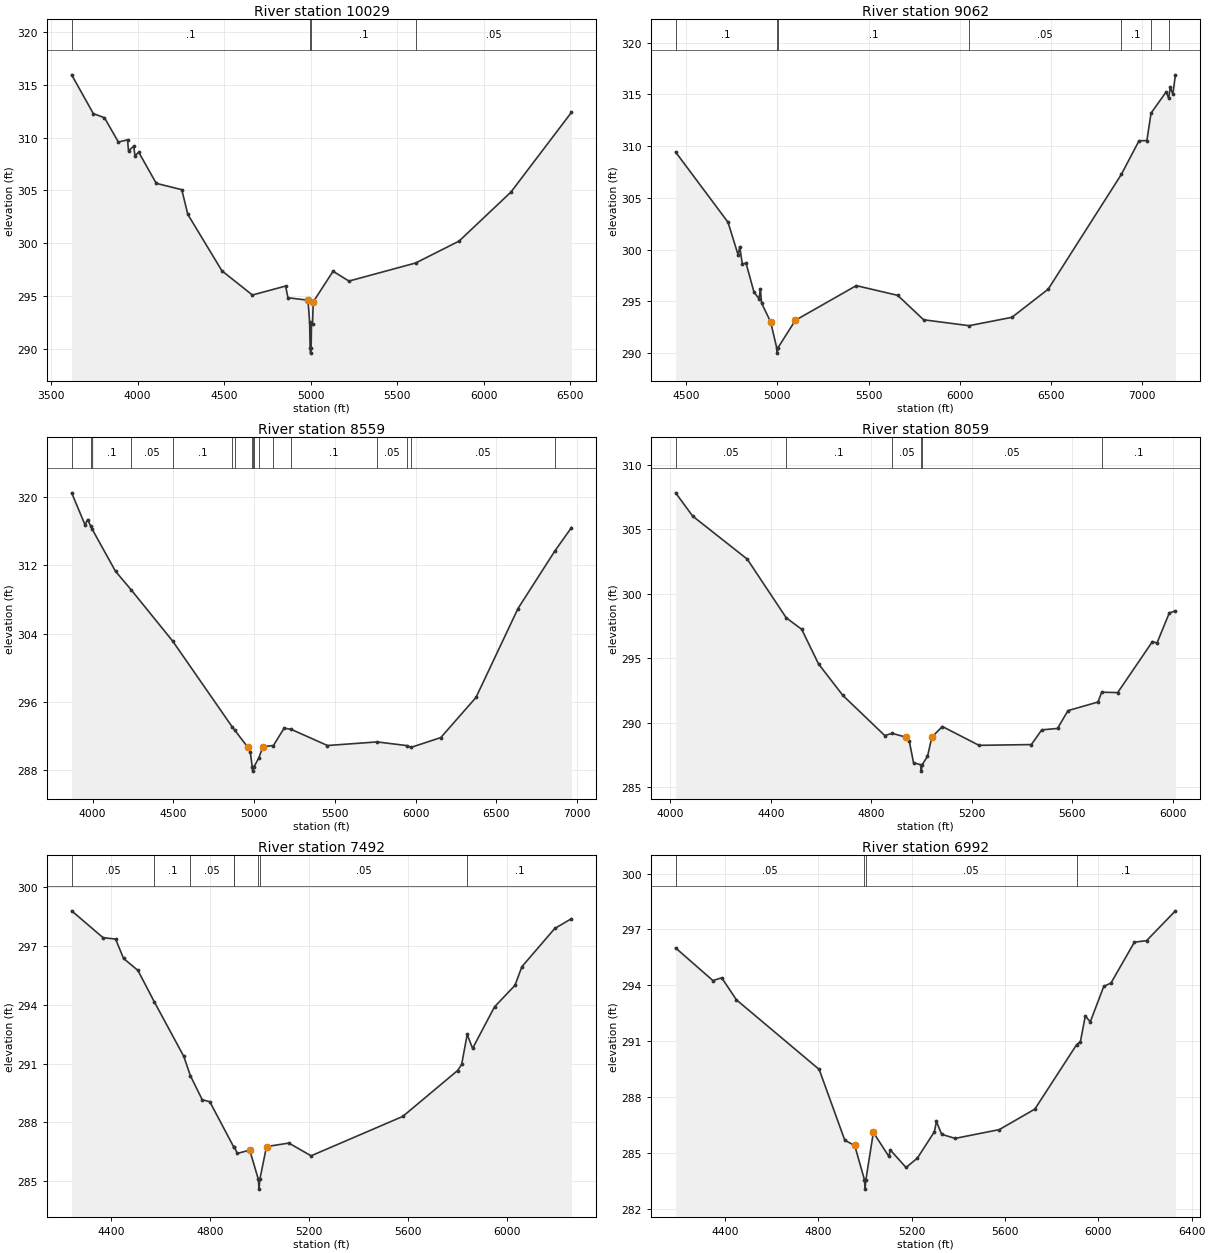
Type RM Length L Ch R = 1 ,10029   ,967,967,967
BEGIN DESCRIPTION:
UNT029 IN SPCR 18.0
END DESCRIPTION:
XS GIS Cut Line= 3
      2288187.72     13353396.85      2287487.72     13354596.85
      2286587.75     13355796.82
#Sta/Elev= 30
  3618.7  315.94    3744  312.27  3808.5  311.88  3888.7  309.58  3941.6  309.79
  3947.4  308.75  3977.6  309.19  3984.6  308.27  4006.1  308.62  4107.8  305.67
  4255.4  305.07  4290.2  302.73  4487.4  297.39  4663.5   295.1  4855.4  295.95
    4869  294.84  4984.8  294.61  4994.3  292.56  4997.1   290.1  4999.8   289.6
  5003.1   290.1  5005.1  292.38  5011.1  292.38  5015.2  294.45  5129.8  297.35
  5221.5  296.42    5607  298.13  5857.9   300.2  6157.9  304.84  6507.9  312.39
#Mann= 4 ,-1 , 0
  3618.7      .1       0  4997.1     .07       0  5003.1      .1       0
    5607     .05       0
Bank Sta=4984.8,5015.2
XS Rating Curve= 0 ,0
Exp/Cntr=0.3,0.1

Type RM Length L Ch R = 1 ,9062    ,503,503,503
BEGIN DESCRIPTION:
UNT029 IN SPCR 17.0
END DESCRIPTION:
XS GIS Cut Line= 2
      2287831.01     13353376.86      2285707.15      13355107.2
#Sta/Elev= 30
  4442.8  309.42    4730  302.64    4786  299.45  4793.9  300.29  4808.2  298.64
  4829.1  298.67  4872.2   295.9  4899.5  295.25  4907.4  296.21  4913.8  294.84
  4963.4  293.02    4997   290.5  4999.8     290    5003   290.5  5099.1  293.17
    5433  296.52    5660  295.58  5802.1  293.22  6051.5  292.65  6286.2  293.46
    6485  296.18  6885.7  307.26  6982.7  310.51  7025.8  310.53  7048.6  313.18
  7131.4  315.23  7145.3  314.62  7153.7  315.66    7168  315.03  7182.3  316.88
#Mann= 7 ,-1 , 0
  4442.8      .1       0    4997     .07       0    5003      .1       0
  6051.5     .05       0  6885.7      .1       0  7048.6     .08       0
  7145.3      .1       0
Bank Sta=4963.4,5099.1
XS Rating Curve= 0 ,0
Exp/Cntr=0.3,0.1

Type RM Length L Ch R = 1 ,8559    ,500,500,500
BEGIN DESCRIPTION:
UNT029 IN SPCR 15.0
END DESCRIPTION:
XS GIS Cut Line= 3
      2288114.58     13353006.51      2287414.31     13353139.62
      2285412.39     13354429.88
#Sta/Elev= 30
  3870.7   320.5  3953.4  316.76  3969.3  317.37  3987.9  316.64  3998.1  316.23
  4142.3  311.31  4238.8  309.15  4497.3  303.11  4865.1  293.08  4881.7  292.67
  4961.5  290.71  4976.6  290.16  4988.8  288.41  4991.6  287.91  4994.8  288.41
  5000.9  288.45  5029.7  289.47  5055.3  290.78    5120  290.91  5186.2  292.95
  5231.6  292.79  5454.5  290.91  5761.2  291.33  5946.3   290.9  5971.9  290.69
  6156.2  291.84  6374.1  296.54  6634.1  306.95  6863.4  313.72  6965.2  316.43
#Mann= 17 ,-1 , 0
  3870.7      .1       0  3987.9     .05       0  3998.1      .1       0
  4238.8     .05       0  4497.3      .1       0  4865.1     .05       0
  4881.7      .1       0  4988.8     .07       0  4994.8      .1       0
  5000.9     .05       0  5029.7      .1       0    5120     .05       0
  5231.6      .1       0  5761.2     .05       0  5946.3      .1       0
  5971.9     .05       0  6863.4      .1       0
Bank Sta=4961.5,5055.3
XS Rating Curve= 0 ,0
Exp/Cntr=0.3,0.1

Type RM Length L Ch R = 1 ,8059    ,567,567,567
BEGIN DESCRIPTION:
UNT029 IN SPCR 14.0
END DESCRIPTION:
XS GIS Cut Line= 2
      2287726.83     13352682.44       2285817.1       13353238.
#Sta/Elev= 30
  4021.3  307.83  4089.4  306.02  4306.2  302.69  4461.8  298.13  4522.9  297.25
    4590  294.56  4686.9  292.12  4853.5  289.01  4882.8  289.18  4936.9  288.89
  4951.2  288.56  4968.1   286.9  4996.3  286.75  4999.1  286.25  5002.3  286.75
  5023.5  287.39    5041  288.89  5082.7  289.71  5228.5  288.25  5436.8  288.31
  5478.4  289.45  5540.9  289.56  5582.6  290.94  5702.1  291.61  5716.6  292.37
  5780.4  292.34  5918.8   296.3  5936.7  296.18  5985.9  298.52  6010.2  298.67
#Mann= 6 ,-1 , 0
  4021.3     .05       0  4461.8      .1       0  4882.8     .05       0
  4996.3     .03       0  5002.3     .05       0  5716.6      .1       0
Bank Sta=4936.9,5041
XS Rating Curve= 0 ,0
Exp/Cntr=0.3,0.1

Type RM Length L Ch R = 1 ,7492    ,500,500,500
BEGIN DESCRIPTION:
UNT029 IN SPCR 13.0
END DESCRIPTION:
XS GIS Cut Line= 2
      2287344.87     13352063.23      2285556.64     13352994.96
#Sta/Elev= 30
    4242   298.8  4368.7  297.43  4419.2  297.36  4451.4  296.37  4509.4  295.76
  4574.9  294.17  4694.5  291.37  4720.9  290.39  4768.8  289.16  4799.3  289.06
  4895.9  286.75  4898.7  286.76  4909.8  286.42  4960.4  286.59  4995.2   285.1
  4997.9   284.6  5001.2   285.1  5028.1  286.77  5118.3  286.95  5207.9   286.3
  5577.9  288.31  5798.9  290.65  5815.3  290.96  5837.7  292.49  5859.5  291.78
  5947.9   293.9  6030.6     295  6058.4  295.95    6191   297.9  6258.4   298.4
#Mann= 8 ,-1 , 0
    4242     .05       0  4574.9      .1       0  4720.9     .05       0
  4895.9      .1       0  4898.7     .05       0  4995.2     .03       0
  5001.2     .05       0  5837.7      .1       0
Bank Sta=4960.4,5028.1
XS Rating Curve= 0 ,0
Exp/Cntr=0.3,0.1

Type RM Length L Ch R = 1 ,6992    ,677,677,677
BEGIN DESCRIPTION:
UNT029 IN SPCR 12.0
END DESCRIPTION:
XS GIS Cut Line= 3
      2287304.37     13351837.54      2286783.53     13351785.45
      2285406.21     13352636.15
#Sta/Elev= 30
  4188.2  296.01  4348.2  294.26  4385.8  294.41  4448.7  293.23  4803.3   289.5
  4913.3   285.7  4955.8  285.42  4997.6  283.58  5000.3  283.08  5003.6  283.58
  5035.8  286.12  5102.4  284.83  5108.3  285.18  5175.8  284.24  5224.2  284.74
  5297.5  286.16  5306.2  286.71  5328.3  286.02  5386.2   285.8  5575.4  286.27
  5727.9  287.37  5907.2  290.83    5923  290.98  5944.2  292.36  5965.5  292.05
  6023.4  293.95  6054.2  294.13  6154.7  296.32  6206.7   296.4  6330.5     298
#Mann= 4 ,-1 , 0
  4188.2     .05       0  4997.6     .03       0  5003.6     .05       0
  5907.2      .1       0
Bank Sta=4955.8,5035.8
XS Rating Curve= 0 ,0
Exp/Cntr=0.3,0.1

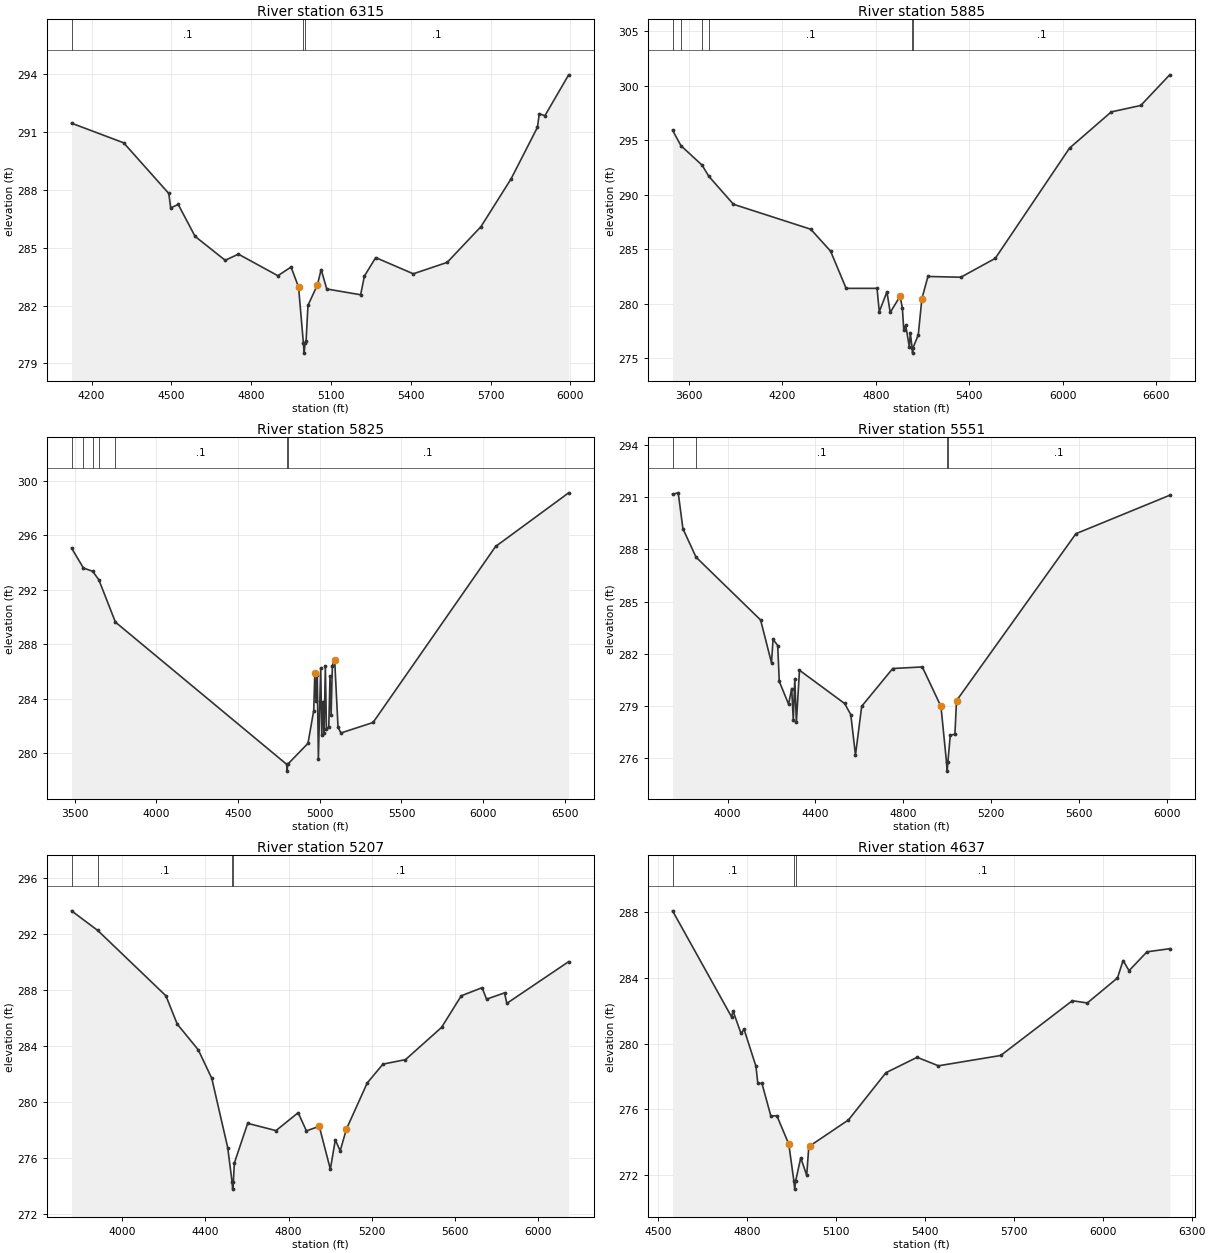
Type RM Length L Ch R = 1 ,6315    ,430,430,430
BEGIN DESCRIPTION:
UNT029 IN SPCR 10.0
END DESCRIPTION:
XS GIS Cut Line= 2
      2286795.07     13350766.96      2285482.06     13352097.33
#Sta/Elev= 30
  4124.6  291.47  4320.7  290.45  4490.3  287.82  4497.4  287.07  4525.7  287.25
  4589.3  285.59  4702.5  284.35    4752  284.67  4900.5  283.55    4950     284
  4978.3  282.96  4996.5  280.03  4999.2  279.53  5002.5  280.03  5006.6  280.18
  5013.6  282.01    5049  283.07  5063.2  283.87  5084.3  282.86  5211.6  282.56
  5225.8  283.53  5268.2  284.49  5409.6  283.65  5536.9  284.24  5664.2   286.1
  5777.3  288.58  5876.3  291.25  5883.4  291.96  5904.6  291.86  5993.8  293.98
#Mann= 3 ,-1 , 0
  4124.6      .1       0  4996.5     .07       0  5002.5      .1       0
Bank Sta=4978.3,5049
XS Rating Curve= 0 ,0
Exp/Cntr=0.3,0.1

Type RM Length L Ch R = 1 ,5885    ,60,60,60
BEGIN DESCRIPTION:
Mapping XS a65ae829
END DESCRIPTION:
XS GIS Cut Line= 4
      2287035.51     13350093.51       2285952.2     13351044.88
      2285861.92     13351107.38      2285202.45      13352606.8
#Sta/Elev= 30
  3495.5  295.91  3549.4  294.49  3684.8  292.71  3727.9  291.69  3886.1  289.12
  4382.4  286.83  4509.5  284.82  4609.1  281.41  4807.5  281.41  4821.7  279.27
    4871  281.09  4891.9   279.2  4955.2  280.68  4970.1  279.61  4978.9  277.59
  4991.4  278.03  5014.7  276.02  5020.8   277.3  5032.6  275.97  5035.4  275.47
  5038.6  275.97  5071.9  277.14  5095.2  280.46  5133.9   282.5    5345  282.43
    5566  284.16  6042.4  294.27  6310.1  297.59  6499.4  298.18  6685.1  300.99
#Mann= 6 ,-1 , 0
  3495.5     .05       0  3549.4      .1       0  3684.8     .08       0
  3727.9      .1       0  5032.6     .07       0  5038.6      .1       0
Bank Sta=4955.2,5095.2
XS Rating Curve= 0 ,0
Exp/Cntr=0.3,0.1

Type RM Length L Ch R = 1 ,5825    ,274,274,274
BEGIN DESCRIPTION:
Mapping XS 3c619fac
END DESCRIPTION:
XS GIS Cut Line= 4
      2286959.17     13350003.19      2285875.81     13351030.99
      2285771.65     13351121.27      2285202.68     13352411.85
#Sta/Elev= 30
  3481.2  295.07  3554.1   293.6  3610.4  293.36  3648.2  292.74  3749.7  289.63
  4797.5  279.19  4800.3  278.69  4803.5  279.19  4927.9  280.73  4963.1  283.14
  4969.8   285.9  4977.2  283.81  4984.9  285.72  4991.5  279.61  5005.7  286.26
  5012.3  281.33    5020   283.8  5026.6  281.51  5034.2  286.38  5040.9  281.76
  5055.1  281.94  5062.7  285.64  5069.4  282.82    5077  286.44  5091.1  286.86
  5111.7  281.93  5129.2  281.49  5326.1  282.26  6075.6  295.18  6522.8  299.12
#Mann= 7 ,-1 , 0
  3481.2     .05       0  3554.1      .1       0  3610.4     .05       0
  3648.2     .08       0  3749.7      .1       0  4797.5     .07       0
  4803.5      .1       0
Bank Sta=4969.8,5091.1
XS Rating Curve= 0 ,0
Exp/Cntr=0.3,0.1

Type RM Length L Ch R = 1 ,5551    ,344,344,344
BEGIN DESCRIPTION:
Mapping XS b3bab13c
END DESCRIPTION:
XS GIS Cut Line= 3
      2286673.59     13349916.22      2285487.23     13351073.65
      2285249.98     13351629.17
#Sta/Elev= 30
  3749.9  291.17  3775.7  291.25    3797  289.19  3856.8  287.55  4150.4  283.94
    4200  281.48    4207  282.83  4228.3  282.47  4235.3  280.41  4277.7   279.1
  4291.9     280  4299.1  278.19    4306  280.57  4313.2  278.06  4327.3  281.05
  4532.4  279.14  4560.7   278.5    4582  276.17  4610.3  278.98  4751.5  281.15
    4886  281.24  4970.9  278.97  4996.2  275.75  4998.9  275.25  5002.2  275.75
  5013.3  277.32  5034.4  277.37  5041.6   279.3  5584.8   288.9  6011.4  291.11
#Mann= 4 ,-1 , 0
  3749.9     .08       0  3856.8      .1       0  4996.2     .07       0
  5002.2      .1       0
Bank Sta=4970.9,5041.6
XS Rating Curve= 0 ,0
Exp/Cntr=0.3,0.1

Type RM Length L Ch R = 1 ,5207    ,570,570,570
BEGIN DESCRIPTION:
UNT029 IN SPCR 9.0
END DESCRIPTION:
XS GIS Cut Line= 3
      2285950.19     13349331.73      2285874.96     13349829.43
      2285157.36     13351571.35
#Sta/Elev= 30
  3757.8  293.67  3883.6  292.27  4211.1   287.6  4265.4  285.58  4366.5  283.74
  4431.4   281.7  4507.9  276.75  4528.9  274.29  4531.6  273.79  4534.9  274.29
  4539.6  275.65  4603.7  278.49  4739.6  277.97  4846.2  279.25  4885.7  277.95
  4947.4  278.28  5000.7  275.21  5024.6  277.31  5047.9  276.52  5077.9  278.08
  5177.7  281.37  5253.4  282.72  5361.5  283.04  5534.6  285.34  5629.4   287.6
  5729.3  288.18  5750.9  287.36  5837.1  287.81  5848.2  287.06  6145.1  290.04
#Mann= 4 ,-1 , 0
  3757.8     .05       0  3883.6      .1       0  4528.9     .07       0
  4534.9      .1       0
Bank Sta=4947.4,5077.9
XS Rating Curve= 0 ,0
Exp/Cntr=0.3,0.1

Type RM Length L Ch R = 1 ,4637    ,560,560,560
BEGIN DESCRIPTION:
UNT029 IN SPCR 8.0
END DESCRIPTION:
XS GIS Cut Line= 2
       2285156.2     13349817.41      2284961.88     13351483.02
#Sta/Elev= 30
    4549   288.1  4748.2  281.63  4753.2  281.98    4780  280.62  4790.1  280.88
  4830.3  278.62  4836.6  277.58  4850.5  277.58  4880.7  275.58  4900.8  275.61
  4941.1  273.87  4958.2  271.63    4961  271.13  4964.2  271.63  4981.4  273.04
  5001.5  271.97  5008.5  273.71  5013.5  273.78  5142.4  275.35  5268.8  278.23
    5374  279.17  5445.7  278.65  5655.9  279.28  5897.5  282.62  5947.9  282.48
  6049.8  284.01  6068.7  285.07  6088.8  284.45  6149.2   285.6  6225.9  285.79
#Mann= 3 ,-1 , 0
    4549      .1       0  4958.2     .07       0  4964.2      .1       0
Bank Sta=4941.1,5013.5
XS Rating Curve= 0 ,0
Exp/Cntr=0.3,0.1

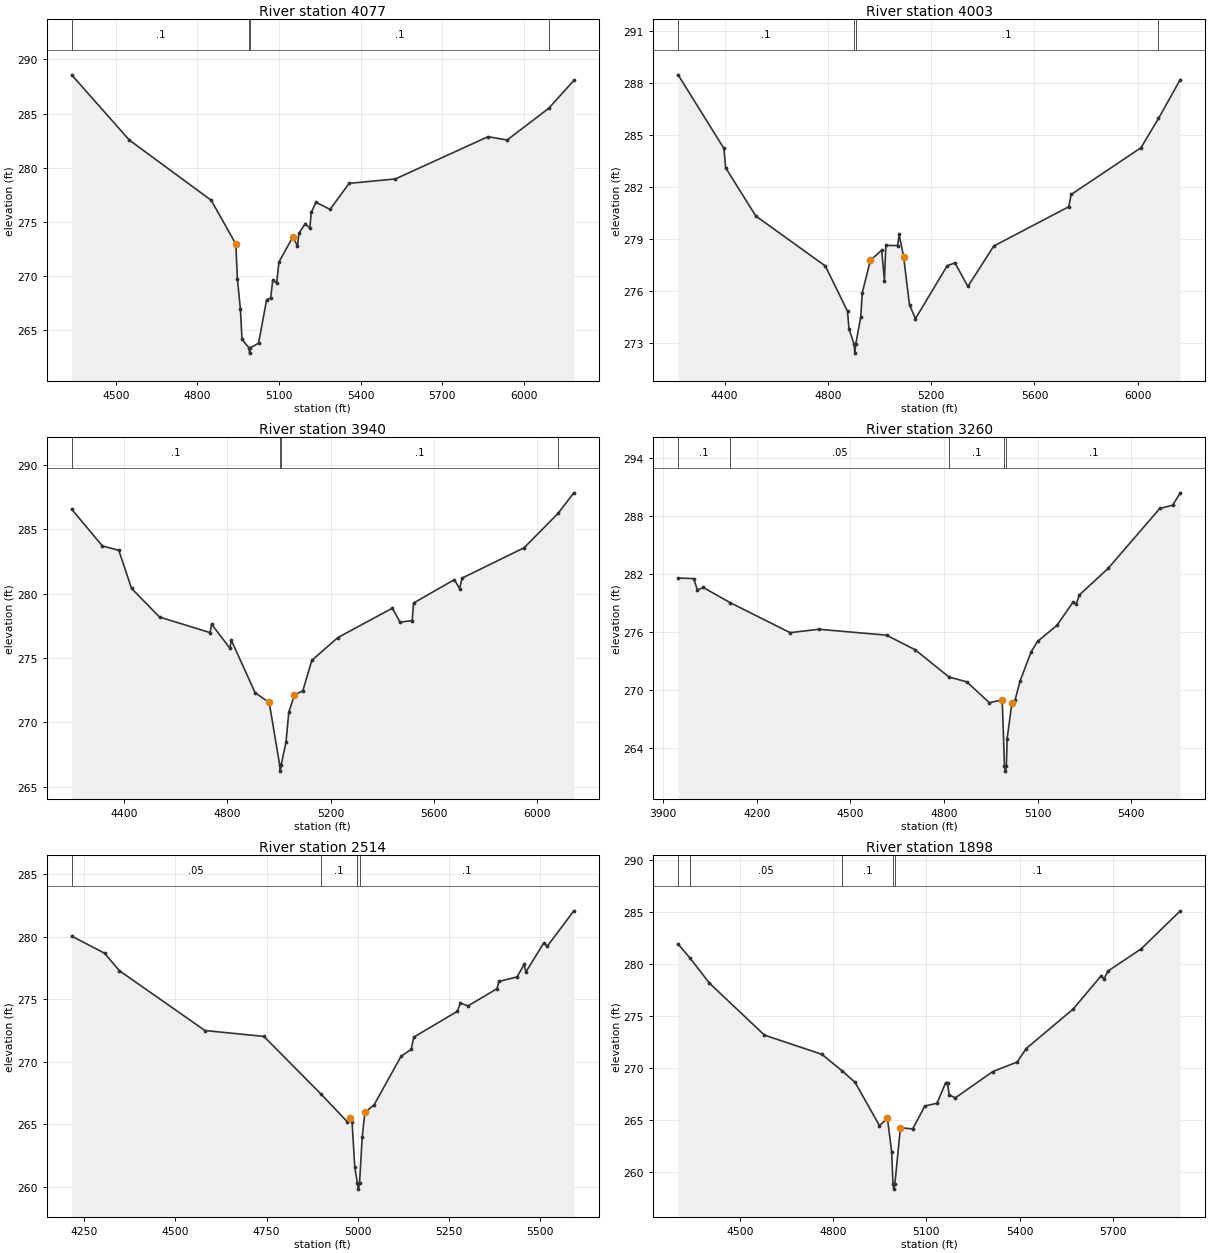
Type RM Length L Ch R = 1 ,4077    ,74,74,74
BEGIN DESCRIPTION:
Mapping XS 8d7f0c6f
END DESCRIPTION:
XS GIS Cut Line= 4
      2284571.11     13349891.26      2284453.94     13350173.35
      2284718.69     13350724.57      2284749.44     13351651.89
#Sta/Elev= 30
    4338  288.58  4549.8  282.56  4850.6     277  4941.1  272.96  4946.9  269.72
    4958  266.93  4963.8  264.17    4989  263.39  4991.7  262.89    4995  263.39
  5024.5  263.81  5054.3  267.82  5068.9  267.97    5077  269.66  5091.1  269.34
  5099.6   271.3  5150.4  273.62  5167.5  272.79  5173.1  273.95  5195.7  274.84
  5212.8  274.43  5218.4  275.88  5235.3  276.82  5287.3  276.16  5357.3  278.56
  5527.4  278.97  5867.6  282.87  5937.6  282.56  6090.7  285.49  6182.8  288.06
#Mann= 4 ,-1 , 0
    4338      .1       0    4989     .07       0    4995      .1       0
  6090.7     .05       0
Bank Sta=4941.1,5150.4
XS Rating Curve= 0 ,0
Exp/Cntr=0.3,0.1

Type RM Length L Ch R = 1 ,4003    ,63,63,63
BEGIN DESCRIPTION:
Mapping XS 7e10b0d2
END DESCRIPTION:
XS GIS Cut Line= 4
      2284501.69     13349817.42      2284362.79     13350142.97
      2284653.59     13350767.97      2284675.65     13351669.21
#Sta/Elev= 30
  4219.9  288.48  4397.2  284.23  4404.1  283.11  4520.7  280.33  4790.1  277.44
  4875.9  274.83  4881.6  273.82  4901.5  272.91  4904.3  272.41  4907.5  272.91
  4927.4  274.51  4932.9  275.88  4964.2  277.76  5008.3  278.36  5018.9  276.59
  5024.4  278.63  5070.2  278.62  5075.7  279.26  5093.1  277.98    5116   275.2
  5138.9   274.4  5262.2  277.46  5292.1  277.62  5342.1  276.26  5442.1  278.59
  5732.2  280.86  5742.2  281.57  6012.3  284.27  6080.2  285.96  6164.7  288.21
#Mann= 4 ,-1 , 0
  4219.9      .1       0  4901.5     .07       0  4907.5      .1       0
  6080.2     .05       0
Bank Sta=4964.2,5093.1
XS Rating Curve= 0 ,0
Exp/Cntr=0.3,0.1

Type RM Length L Ch R = 1 ,3940    ,680,680,680
BEGIN DESCRIPTION:
Mapping XS d5168a8d
END DESCRIPTION:
XS GIS Cut Line= 4
       2284419.2     13349804.47      2284306.37     13350129.95
      2284601.51     13350828.73      2284606.21     13351669.18
#Sta/Elev= 30
  4197.2  286.57  4316.1  283.71  4379.7  283.37    4429  280.41  4537.4  278.18
  4733.1  276.97  4738.5  277.64  4809.7  275.75  4815.1  276.38  4907.4  272.29
  4961.7  271.54  5002.1   266.7  5004.9   266.2  5008.1   266.7  5026.8  268.45
  5037.7   270.8  5059.4  272.12  5091.9  272.45  5126.7  274.81  5226.9  276.58
  5438.4  278.87  5468.4  277.78  5515.3  277.91  5520.3  279.27  5678.4  281.09
  5698.4  280.39  5708.4  281.21  5948.4  283.57  6079.5  286.24  6140.7  287.84
#Mann= 4 ,-1 , 0
  4197.2      .1       0  5002.1     .07       0  5008.1      .1       0
  6079.5     .05       0
Bank Sta=4961.7,5059.4
XS Rating Curve= 0 ,0
Exp/Cntr=0.3,0.1

Type RM Length L Ch R = 1 ,3260    ,746,746,746
BEGIN DESCRIPTION:
Mapping XS 973600e5
END DESCRIPTION:
XS GIS Cut Line= 2
      2284086.77     13349638.43      2283699.04     13351200.94
#Sta/Elev= 30
  3947.6  281.56  3997.5   281.5  4009.4  280.33  4028.4  280.58  4114.5  279.01
  4306.6  275.91  4399.3  276.26  4615.7  275.65  4707.5  274.14  4815.6  271.33
    4873  270.82  4945.4  268.67  4986.6  268.95  4993.9  262.09  4996.7  261.59
  4999.9  262.09  5002.3  264.95  5017.5   268.6  5027.8  268.93  5043.6  270.89
  5079.3  273.93  5099.9     275  5161.8  276.66  5214.2  279.09  5223.6  278.84
  5233.9  279.81  5326.6  282.57  5491.5  288.75  5532.7  289.09  5557.5  290.37
#Mann= 5 ,-1 , 0
  3947.6      .1       0  4114.5     .05       0  4815.6      .1       0
  4993.9     .07       0  4999.9      .1       0
Bank Sta=4986.6,5017.5
XS Rating Curve= 0 ,0
Exp/Cntr=0.3,0.1

Type RM Length L Ch R = 1 ,2514    ,616,616,616
BEGIN DESCRIPTION:
UNT029 IN SPCR 5.0
END DESCRIPTION:
XS GIS Cut Line= 3
      2283337.72     13349446.83      2283237.72     13350246.85
      2283087.73     13350796.82
#Sta/Elev= 30
  4215.5  280.04  4306.2  278.66  4346.5  277.27  4580.8  272.49  4742.1  272.02
  4898.6  267.42  4971.4  265.18  4978.9   265.5    4984  265.18  4991.5  261.55
  4998.6  260.31  5001.3  259.81  5004.6  260.31  5011.7  263.96  5019.2  265.94
  5044.2  266.54  5118.5  270.44  5146.1  270.98    5153  271.96  5272.2  274.02
  5280.9  274.68  5301.6  274.46  5381.1  275.83  5386.3  276.41  5436.4  276.78
  5455.4  277.77  5460.5  277.18  5508.9  279.47  5519.3  279.24  5591.8  282.06
#Mann= 4 ,-1 , 0
  4215.5     .05       0  4898.6      .1       0  4998.6     .07       0
  5004.6      .1       0
Bank Sta=4978.9,5019.2
XS Rating Curve= 0 ,0
Exp/Cntr=0.3,0.1

Type RM Length L Ch R = 1 ,1898    ,724,724,724
BEGIN DESCRIPTION:
UNT029 IN SPCR 4.0
END DESCRIPTION:
XS GIS Cut Line= 3
      2282998.79     13349297.04      2282848.34     13349511.15
      2282478.16     13350812.55
#Sta/Elev= 30
  4301.9  281.92  4340.6  280.55  4402.5  278.16  4579.4  273.16  4764.4  271.31
  4830.2   269.7    4871  268.61  4949.3  264.46    4975  265.16  4988.4  261.96
  4992.8  258.85  4995.5  258.35  4998.8  258.85  5016.6  264.25  5056.1  264.14
  5095.2  266.34  5134.3  266.61  5162.1  268.58  5168.1   268.6  5173.3   267.4
  5193.3  267.13    5314  269.66  5392.1  270.57  5420.8  271.86  5571.9  275.66
  5661.2  278.83  5671.6  278.57  5683.9  279.32  5790.7  281.45  5916.6  285.11
#Mann= 5 ,-1 , 0
  4301.9      .1       0  4340.6     .05       0  4830.2      .1       0
  4992.8     .07       0  4998.8      .1       0
Bank Sta=4975,5016.6
XS Rating Curve= 0 ,0
Exp/Cntr=0.3,0.1

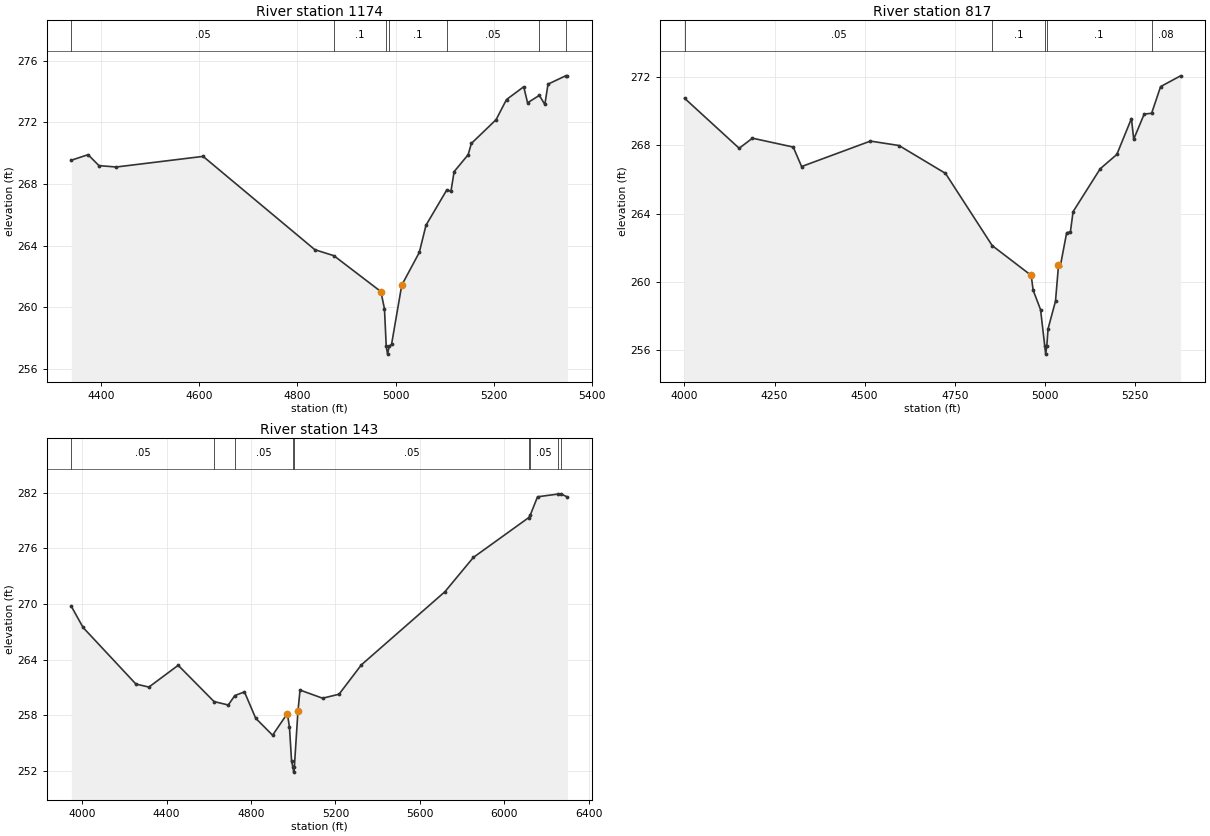
Type RM Length L Ch R = 1 ,1174    ,357,357,357
BEGIN DESCRIPTION:
UNT029 IN SPCR 3.0
END DESCRIPTION:
XS GIS Cut Line= 2
       2282541.6     13349482.23      2281766.19     13350130.34
#Sta/Elev= 30
  4339.5  269.54  4373.6   269.9  4395.7  269.19  4430.9   269.1  4607.9  269.79
  4835.6  263.73  4874.4  263.34  4970.1  261.01  4977.4  259.89    4981  257.45
  4983.7  256.95    4987  257.45  4991.8  257.58  5012.6  261.43  5048.3  263.55
    5062  265.32  5104.5  267.62  5112.8  267.52  5119.3   268.8  5147.9   269.9
  5154.4  270.63  5204.7  272.17    5226  273.48  5261.1  274.31  5268.9  273.27
  5292.9  273.75  5304.1  273.16  5310.6  274.48  5346.4  275.02  5350.1  275.02
#Mann= 7 ,-1 , 0
  4339.5     .05       0  4874.4      .1       0    4981     .07       0
    4987      .1       0  5104.5     .05       0  5292.9     .08       0
  5346.4     .05       0
Bank Sta=4970.1,5012.6
XS Rating Curve= 0 ,0
Exp/Cntr=0.3,0.1

Type RM Length L Ch R = 1 ,817     ,674,674,674
BEGIN DESCRIPTION:
UNT029 IN SPCR 2.0
END DESCRIPTION:
XS GIS Cut Line= 3
      2282379.63     13349019.23      2281876.12     13349244.94
      2281667.99     13350042.75
#Sta/Elev= 30
  4000.2  270.75  4151.8  267.82  4188.6  268.41  4301.8  267.89    4325  266.75
  4515.9  268.24  4595.3  267.98  4724.2  266.35  4853.9  262.12  4961.9  260.38
  4967.4  259.51    4988  258.37  4999.4  256.27  5002.1  255.77  5005.4  256.27
  5008.7  257.25  5029.4  258.87  5037.7  260.96  5042.9  260.94  5060.4  262.88
  5070.7  262.92  5078.2  264.11  5153.4  266.62  5199.6  267.46  5240.1  269.56
  5246.4  268.35  5275.4  269.82  5296.1  269.87    5321  271.43  5376.5  272.06
#Mann= 5 ,-1 , 0
  4000.2     .05       0  4853.9      .1       0  4999.4     .07       0
  5005.4      .1       0  5296.1     .08       0
Bank Sta=4961.9,5037.7
XS Rating Curve= 0 ,0
Exp/Cntr=0.3,0.1

Type RM Length L Ch R = 1 ,143     ,0,0,0
BEGIN DESCRIPTION:
UNT029 IN SPCR 1.0
END DESCRIPTION:
XS GIS Cut Line= 4
      2281364.02     13348528.02      2281156.36     13348989.67
      2281148.54      13349668.1      2281975.96     13350488.95
#Sta/Elev= 30
  3949.1  269.74  4004.6  267.46  4254.9  261.36  4316.5  261.03  4455.3  263.38
  4625.1  259.47  4692.5   259.1  4723.7  260.12  4769.3  260.51  4822.5  257.67
  4902.5  255.84  4972.5  258.18  4982.5   256.7  4992.5  253.01  4999.5  252.36
  5002.3  251.86  5005.5  252.36  5022.5   258.4  5032.5  260.71  5139.4  259.83
  5217.2  260.26  5323.2  263.43  5719.2  271.32  5853.6  275.01  6115.6   279.3
  6122.7  279.55  6157.7  281.55  6253.3  281.84  6267.2  281.87  6299.3  281.53
#Mann= 9 ,-1 , 0
  3949.1     .05       0  4625.1      .1       0  4723.7     .05       0
  4999.5     .03       0  5005.5     .05       0  6115.6     .08       0
  6122.7     .05       0  6253.3     .08       0  6267.2     .05       0
Bank Sta=4972.5,5022.5
XS Rating Curve= 0 ,0
Exp/Cntr=0.3,0.1

Chan Stop Cuts=-1
Use User Specified Reach Order=0
Composite Channel Slope=5