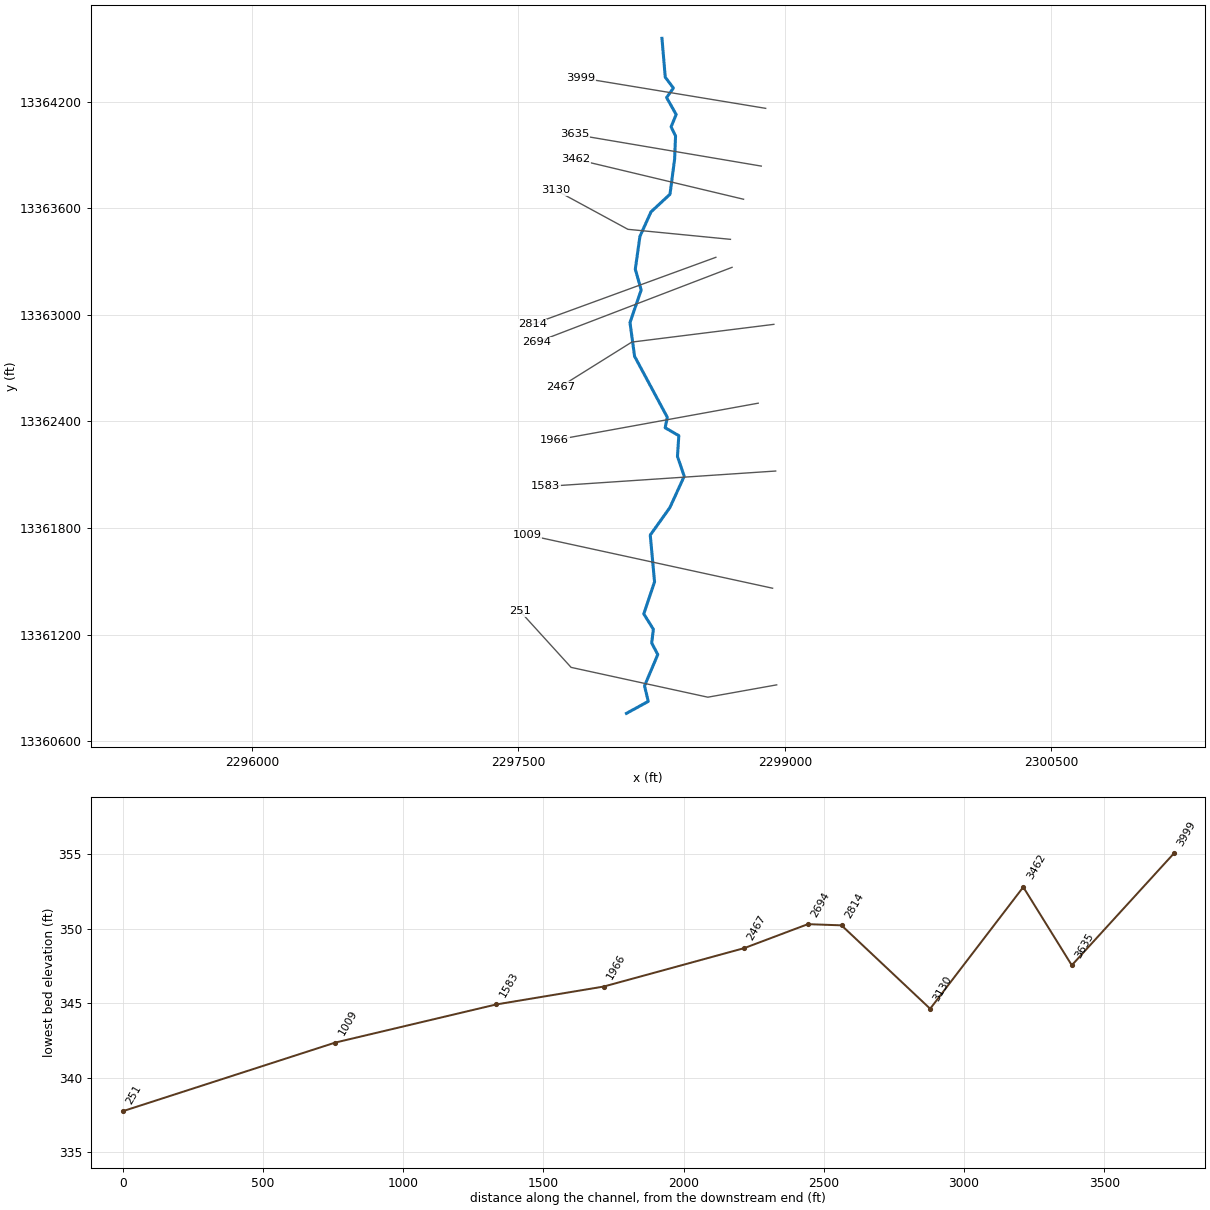
--- UNT030 IN SPCR.prj (project) ---

Proj Title=UNT030 IN SPCR Base Level Engineering
Current Plan=p01
Default Exp/Contr=0.3,0.1
English Units
Geom File=g01
Flow File=f01
Plan File=p01
Y Axis Title=Elevation
X Axis Title(PF)=Main Channel Distance
X Axis Title(XS)=Station
BEGIN DESCRIPTION:
UNT030 IN SPCR
END DESCRIPTION:
DSS Export Rating Curves= 0
DSS Export Rating Curve Sorted= 0
DSS Export Volume Flow Curves= 0
DXF OffsetX= 0
DXF OffsetY= 0
DXF ScaleX= 1
DXF ScaleY= 10

--- UNT030 IN SPCR.p01 (plan) ---

Plan Title=Multiple Run
Short Identifier=Multiple
Geom File=g01
Flow File=f01
Subcritical Flow
K Sum by GR= 0
Std Step Tol= 0.01
Critical Tol= 0.01
Num of Std Step Trials= 20
Max Error Tol= 0.3
Flow Tol Ratio= 0.001
Split Flow NTrial= 30
Split Flow Tol= 0.02
Split Flow Ratio= 0.02
Log Output Level= 0
Friction Slope Method= 1
Unsteady Friction Slope Method= 2
Unsteady Bridges Friction Slope Method= 1
Parabolic Critical Depth
Global Vel Dist=  1 , 1 , 1
Global Log Level= 0
CheckData=True
Encroach Param= -1, 0, 0, 0
BEGIN DESCRIPTION:
Multiple Run
END DESCRIPTION:

--- UNT030 IN SPCR.f01 (steady flow) ---

Flow Title=Multiple
Number of Profiles=7
Profile Names=10-year,25-year,50-year,1pct_min,100-year,1pct_plu,500-year
River Rch & RM= UNT030 IN SPCR,Reach-1,3999
     586     829    1033     940    1271    1719    1934
River Rch & RM= UNT030 IN SPCR,Reach-1,3635
     678     967    1211    1107    1497    2024    2297
River Rch & RM= UNT030 IN SPCR,Reach-1,2694
     733    1048    1314    1204    1628    2201    2507
Boundary for River Rch & Prof#=UNT030 IN SPCR,Reach-1,1
Up Type=0
Dn Type=3
Dn Slope=0.005
Boundary for River Rch & Prof#=UNT030 IN SPCR,Reach-1,2
Up Type=0
Dn Type=3
Dn Slope=0.005
Boundary for River Rch & Prof#=UNT030 IN SPCR,Reach-1,3
Up Type=0
Dn Type=3
Dn Slope=0.005
Boundary for River Rch & Prof#=UNT030 IN SPCR,Reach-1,4
Up Type=0
Dn Type=3
Dn Slope=0.005
Boundary for River Rch & Prof#=UNT030 IN SPCR,Reach-1,5
Up Type=0
Dn Type=3
Dn Slope=0.005
Boundary for River Rch & Prof#=UNT030 IN SPCR,Reach-1,6
Up Type=0
Dn Type=3
Dn Slope=0.005
Boundary for River Rch & Prof#=UNT030 IN SPCR,Reach-1,7
Up Type=0
Dn Type=3
Dn Slope=0.005

--- UNT030 IN SPCR.g01 (geometry) ---

Geom Title=Existing Conditions
Program Version=4.10

River Reach=UNT030 IN SPCR  ,Reach-1
Reach XY= 30
      2298307.72     13364556.86      2298326.22     13364338.08
      2298372.04     13364276.83      2298333.93     13364223.45
      2298387.81     13364127.83      2298359.14     13364059.02
       2298384.2     13364007.21      2298378.99       13363877.
      2298352.95     13363679.08      2298246.18     13363580.13
      2298183.68     13363442.11      2298157.64     13363257.21
      2298190.84     13363140.17      2298127.72     13362957.05
      2298153.58     13362766.85      2298337.92      13362423.4
      2298325.82     13362364.62      2298402.55     13362320.22
      2298394.98     13362203.05      2298433.13     13362091.85
      2298352.06     13361914.96       2298241.8     13361760.51
      2298266.01     13361497.25      2298205.49     13361316.72
      2298259.44      13361230.3      2298249.95     13361152.61
      2298284.25     13361088.24      2298209.65     13360911.68
      2298230.54     13360824.22      2298107.72     13360756.86

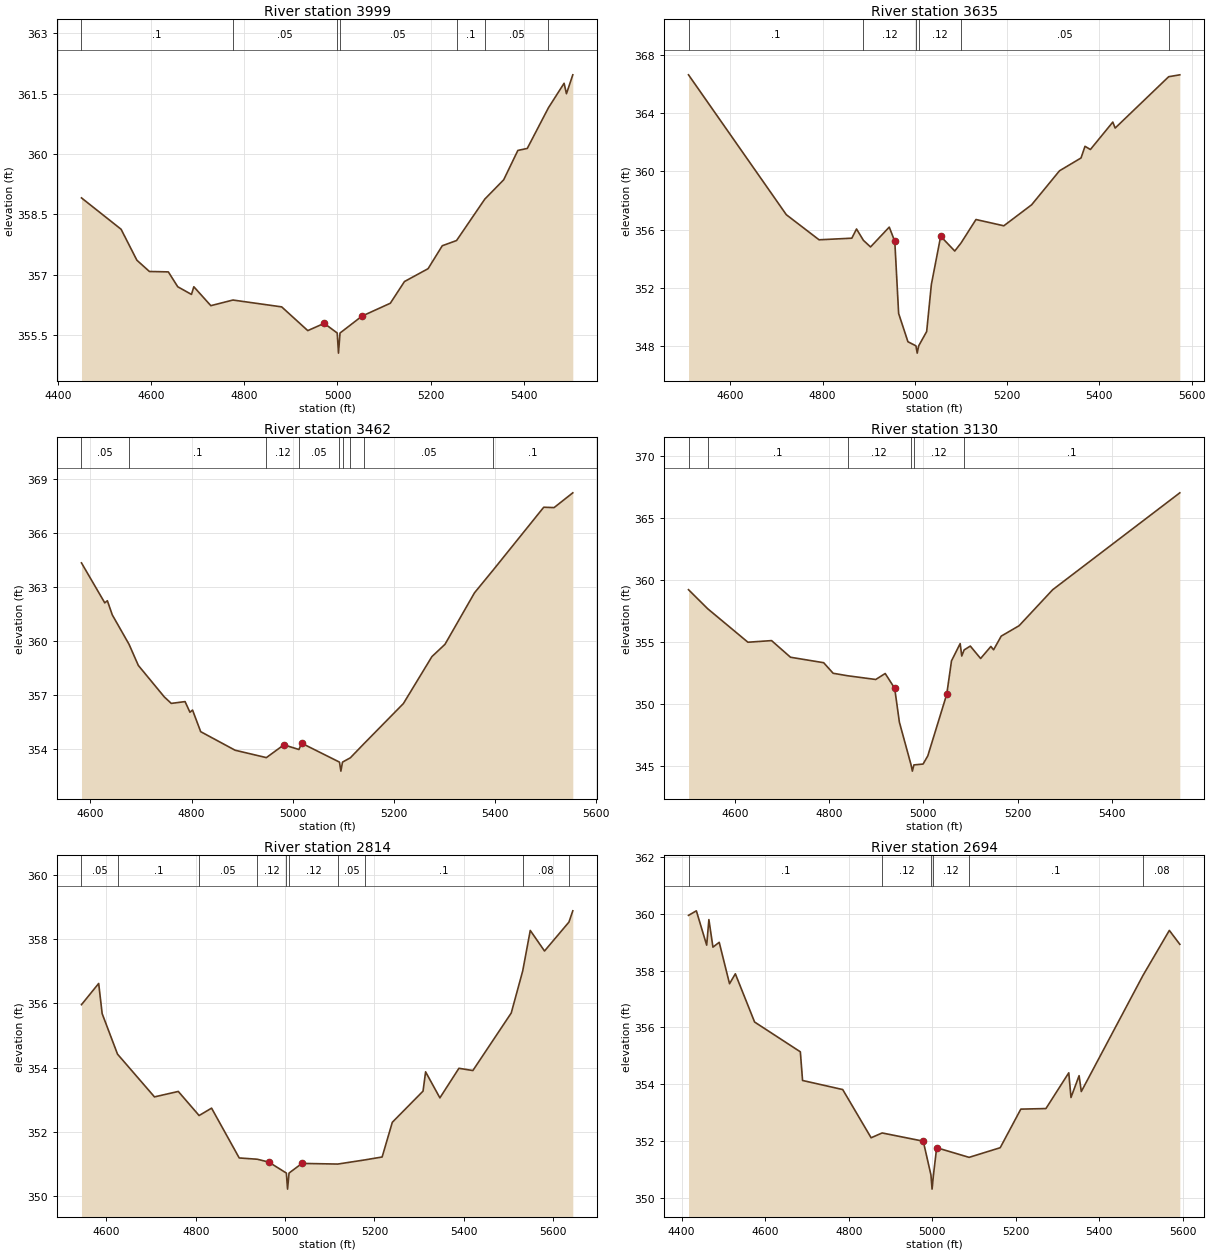
Type RM Length L Ch R = 1 ,3999    ,364,364,364
BEGIN DESCRIPTION:
UNT030 IN SPCR 8.0
END DESCRIPTION:
XS GIS Cut Line= 2
       2298891.6     13364162.77      2297851.36      13364334.4
#Sta/Elev= 30
  4450.7  358.91  4535.7  358.13  4569.6  357.36  4596.5  357.08  4637.1  357.07
  4657.3   356.7  4686.7  356.51  4691.8   356.7  4728.3  356.23  4775.7  356.37
  4880.3   356.2  4936.3  355.61  4971.5  355.79  4999.5  355.55  5002.2  355.05
  5005.5  355.55  5052.6  355.97  5113.4  356.29  5143.8  356.83  5194.5  357.15
  5224.9  357.72  5255.6  357.85  5316.2  358.88  5356.7  359.36  5387.1  360.09
  5407.3  360.14  5452.7  361.15  5486.3  361.76  5491.4   361.5    5505  361.97
#Mann= 7 ,-1 , 0
  4450.7      .1       0  4775.7     .05       0  4999.5     .03       0
  5005.5     .05       0  5255.6      .1       0  5316.2     .05       0
  5452.7      .1       0
Bank Sta=4971.5,5052.6
XS Rating Curve= 0 ,0
Exp/Cntr=0.3,0.1

Type RM Length L Ch R = 1 ,3635    ,173,173,173
BEGIN DESCRIPTION:
Mapping XS 96ed329b
END DESCRIPTION:
XS GIS Cut Line= 2
      2298866.88     13363837.67      2297816.54     13364015.62
#Sta/Elev= 30
  4509.1  366.62  4721.2  357.03  4792.2  355.31  4863.2  355.42  4873.4  356.05
  4888.4  355.27  4903.8  354.82  4944.4  356.18  4956.4   355.2  4964.7  350.26
  4984.9  348.32  5002.2  348.04    5005  347.54  5008.2  348.04  5025.5  349.02
  5035.7  352.25  5055.9  355.55  5086.4  354.54    5100  355.09  5132.4   356.7
  5192.8  356.27  5253.1  357.71  5313.5  360.04  5360.2  360.92  5368.8  361.72
  5380.5   361.5  5429.1  363.38  5434.2  362.97  5550.2  366.49  5574.4  366.62
#Mann= 6 ,-1 , 0
  4509.1      .1       0  4888.4     .12       0  5002.2     .07       0
  5008.2     .12       0    5100     .05       0  5550.2      .1       0
Bank Sta=4956.4,5055.9
XS Rating Curve= 0 ,0
Exp/Cntr=0.3,0.1

Type RM Length L Ch R = 1 ,3462    ,332,332,332
BEGIN DESCRIPTION:
Mapping XS 6ae8d572
END DESCRIPTION:
XS GIS Cut Line= 2
      2298767.05     13363651.04      2297821.77     13363876.52
#Sta/Elev= 30
  4582.3  364.35  4628.4  362.13  4633.5  362.25  4643.3  361.46  4676.4  359.83
  4694.7  358.66  4746.1  356.91  4759.9  356.55  4787.2  356.65  4796.8  356.06
    4802  356.18  4818.1  354.98  4886.2  353.95    4948  353.54  4982.6  354.25
  5012.4  353.99  5017.7  354.34  5092.6  353.29  5095.4  352.79  5098.6  353.29
  5114.1  353.53  5141.3  354.32    5219  356.54  5275.5  359.15  5301.3  359.83
  5359.7  362.69  5396.5  363.95  5496.6  367.44  5517.1  367.42  5554.1  368.24
#Mann= 9 ,-1 , 0
  4582.3     .05       0  4676.4      .1       0    4948     .12       0
  5012.4     .05       0  5092.6     .07       0  5098.6     .05       0
  5114.1      .1       0  5141.3     .05       0  5396.5      .1       0
Bank Sta=4982.6,5017.7
XS Rating Curve= 0 ,0
Exp/Cntr=0.3,0.1

Type RM Length L Ch R = 1 ,3130    ,316,316,316
BEGIN DESCRIPTION:
Mapping XS 429982be
END DESCRIPTION:
XS GIS Cut Line= 3
      2298693.23     13363425.35        2298116.     13363481.77
       2297709.2     13363702.49
#Sta/Elev= 30
  4501.4  359.23    4542   357.7  4627.5     355  4677.7  355.13  4717.9  353.79
  4788.3  353.35  4808.4   352.5    4839   352.3  4898.8     352  4918.9  352.48
    4939  351.29    4949  348.56  4973.8  345.12  4976.5  344.62  4979.8  345.12
  4999.3  345.19  5009.3  345.85  5049.5  350.81  5059.6   353.5    5078  354.89
  5081.4  353.89  5086.4  354.38  5099.5  354.69  5121.4  353.69  5143.2  354.66
  5148.9  354.39  5165.1  355.49  5203.1  356.33  5274.4  359.23  5544.2  367.03
#Mann= 6 ,-1 , 0
  4501.4     .05       0    4542      .1       0    4839     .12       0
  4973.8     .07       0  4979.8     .12       0  5086.4      .1       0
Bank Sta=4939,5049.5
XS Rating Curve= 0 ,0
Exp/Cntr=0.3,0.1

Type RM Length L Ch R = 1 ,2814    ,120,120,120
BEGIN DESCRIPTION:
Mapping XS c2026fe2
END DESCRIPTION:
XS GIS Cut Line= 2
      2298611.22     13363324.22      2297578.27     13362946.63
#Sta/Elev= 30
  4544.1  355.96  4582.6  356.62  4590.4  355.68  4624.8  354.42  4707.5  353.09
  4760.8  353.26  4807.4  352.51  4835.3  352.74  4897.2  351.19  4937.7  351.15
  4963.6  351.06  5002.7  350.72  5005.4  350.22  5008.7  350.72  5037.6  351.02
  5117.9     351  5178.7  351.13  5217.1  351.22  5239.9   352.3  5308.7  353.27
  5314.4  353.87  5346.4  353.06    5389  353.98  5420.2  353.91  5506.1   355.7
  5531.8  357.01  5548.7  358.27  5580.6  357.63  5635.3  358.53  5643.9  358.88
#Mann= 10 ,-1 , 0
  4544.1     .05       0  4624.8      .1       0  4807.4     .05       0
  4937.7     .12       0  5002.7     .07       0  5008.7     .12       0
  5117.9     .05       0  5178.7      .1       0  5531.8     .08       0
  5635.3      .1       0
Bank Sta=4963.6,5037.6
XS Rating Curve= 0 ,0
Exp/Cntr=0.3,0.1

Type RM Length L Ch R = 1 ,2694    ,227,227,227
BEGIN DESCRIPTION:
Mapping XS e7a3ded9
END DESCRIPTION:
XS GIS Cut Line= 2
      2298702.35     13363267.79      2297604.29     13362846.79
#Sta/Elev= 30
  4416.5  359.95  4435.3  360.11    4460   358.9  4465.3   359.8    4475  358.83
    4490     359  4514.7  357.54  4528.6  357.89  4574.7  356.19  4684.2  355.14
  4689.5  354.13  4785.6  353.81  4853.6  352.11    4880  352.28  4978.4  351.99
  4996.8   350.8  4999.5   350.3  5002.8   350.8  5010.5  351.76  5088.1  351.42
  5162.6  351.76  5211.9  353.12    5272  353.14  5326.7   354.4    5332  353.53
  5351.4   354.3  5356.7  353.74  5504.2  357.83  5567.4  359.42  5592.5  358.93
#Mann= 6 ,-1 , 0
  4416.5      .1       0    4880     .12       0  4996.8     .07       0
  5002.8     .12       0  5088.1      .1       0  5504.2     .08       0
Bank Sta=4978.4,5010.5
XS Rating Curve= 0 ,0
Exp/Cntr=0.3,0.1

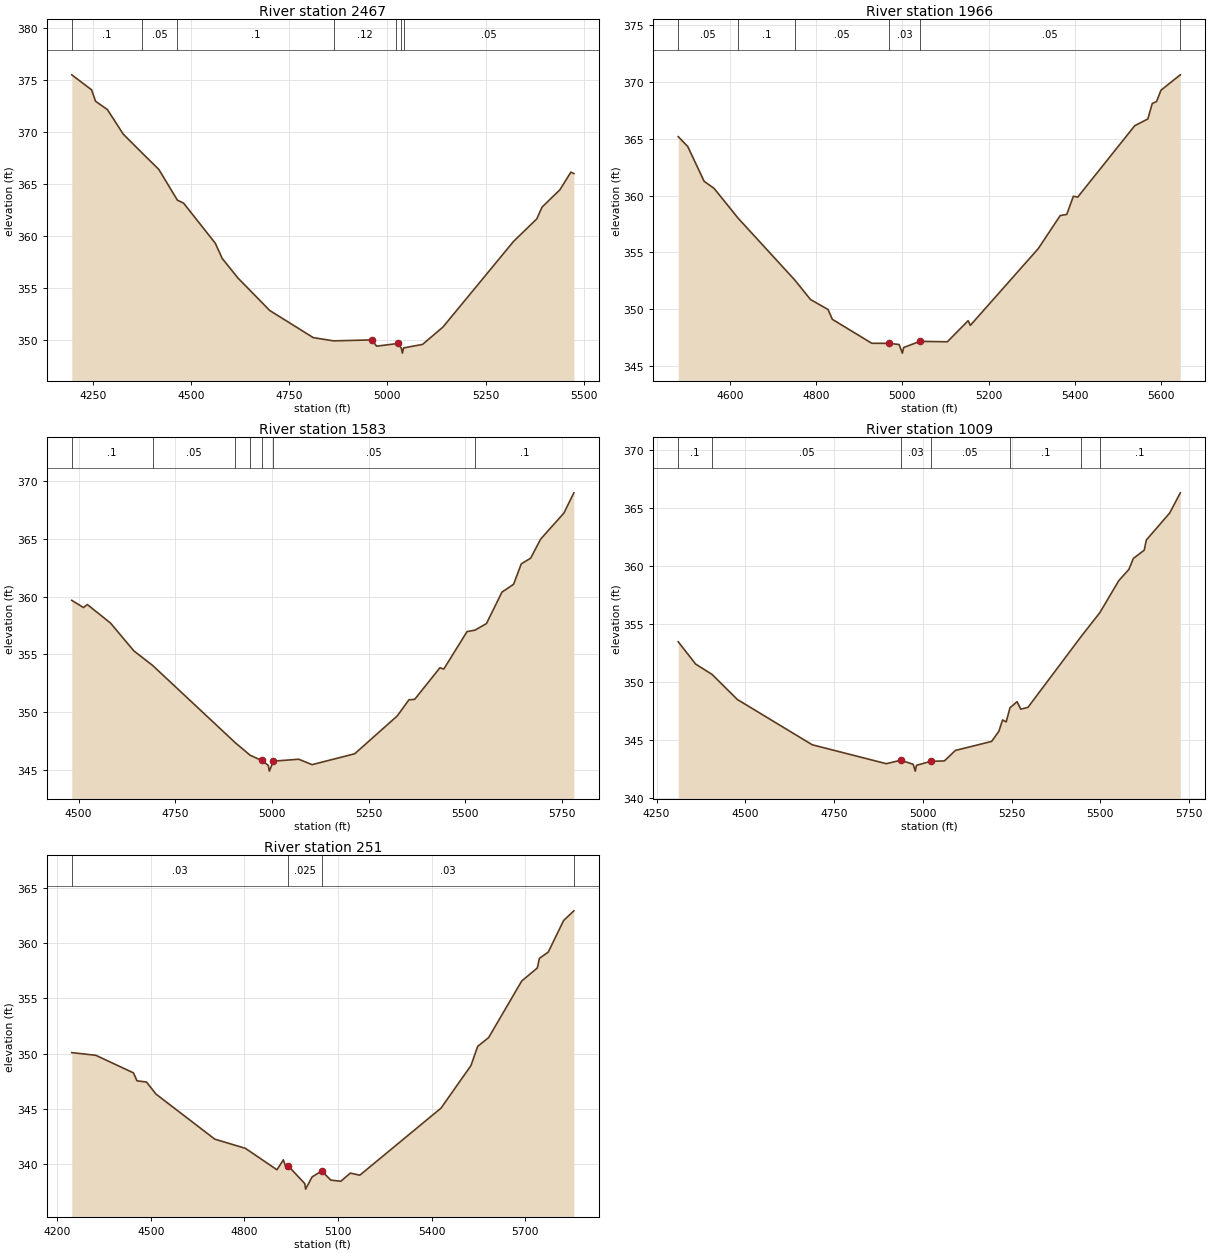
Type RM Length L Ch R = 1 ,2467    ,501,501,501
BEGIN DESCRIPTION:
UNT030 IN SPCR 5.0
END DESCRIPTION:
XS GIS Cut Line= 3
      2298937.72     13362946.85      2298137.72     13362846.85
      2297737.74     13362596.87
#Sta/Elev= 30
  4196.7  375.45  4247.1  374.01  4257.2  372.91  4287.4  372.11  4327.7  369.75
  4376.2  367.92  4418.4  366.35  4465.5   363.4  4481.4  363.11    4562  359.26
  4579.7  357.79    4620   355.9  4700.6  352.79  4811.4  350.18    4863  349.87
  4960.1  349.96  4972.7  349.36  5020.9  349.59  5025.9  349.67  5035.3  349.19
  5038.1  348.69  5041.3  349.19  5089.6  349.53  5141.5   351.2  5321.3  359.44
  5380.3   361.6  5393.8  362.74  5439.2   364.4    5467  366.09  5474.6  365.96
#Mann= 7 ,-1 , 0
  4196.7      .1       0  4376.2     .05       0  4465.5      .1       0
    4863     .12       0  5020.9     .05       0  5035.3     .07       0
  5041.3     .05       0
Bank Sta=4960.1,5025.9
XS Rating Curve= 0 ,0
Exp/Cntr=0.3,0.1

Type RM Length L Ch R = 1 ,1966    ,383,383,383
BEGIN DESCRIPTION:
UNT030 IN SPCR 4.0
END DESCRIPTION:
XS GIS Cut Line= 2
      2298849.47     13362503.04      2297703.66     13362294.71
#Sta/Elev= 30
  4480.2   365.2  4502.3  364.33  4540.3  361.26  4563.3  360.64  4619.1  358.01
  4750.7  352.55  4786.9  350.84  4827.6  349.96  4837.7  349.09  4929.1  346.98
  4969.8  346.97  4992.6  346.87  5000.1  346.11  5003.3  346.61  5040.9  347.15
  5104.4  347.11  5152.7  348.97  5157.8  348.56  5315.4  355.33  5366.2  358.24
  5381.4  358.34  5396.7  359.94  5406.9  359.87    5539  366.16  5569.5  366.76
  5579.7  368.12  5589.8   368.3  5599.9  369.29  5644.6  370.65  5644.8  370.65
#Mann= 6 ,-1 , 0
  4480.2     .05       0  4619.1      .1       0  4750.7     .05       0
  4969.8     .03       0  5040.9     .05       0  5644.6      .1       0
Bank Sta=4969.8,5040.9
XS Rating Curve= 0 ,0
Exp/Cntr=0.3,0.1

Type RM Length L Ch R = 1 ,1583    ,574,574,574
BEGIN DESCRIPTION:
UNT030 IN SPCR 3.0
END DESCRIPTION:
XS GIS Cut Line= 2
      2298947.92      13362121.1      2297652.12     13362034.33
#Sta/Elev= 30
  4482.3  359.68  4512.6  359.06  4522.6  359.32  4582.7  357.71  4642.9  355.31
  4691.5  354.05  4905.5  347.36  4943.5  346.29  4973.6  345.83  4990.6  345.41
  4993.4  344.91  5003.7  345.77  5069.3  345.94  5103.9  345.47  5214.1  346.41
  5324.4  349.69  5354.4  351.08  5369.3  351.12  5434.6  353.85  5444.6  353.74
  5504.8  356.98    5525   357.1  5554.9  357.67    5595  360.39  5625.1  361.07
  5645.1  362.84  5669.3  363.33  5695.2  364.98  5755.3  367.23    5781  368.98
#Mann= 7 ,-1 , 0
  4482.3      .1       0  4691.5     .05       0  4905.5      .1       0
  4943.5     .05       0  4973.6     .03       0  5003.7     .05       0
    5525      .1       0
Bank Sta=4973.6,5003.7
XS Rating Curve= 0 ,0
Exp/Cntr=0.3,0.1

Type RM Length L Ch R = 1 ,1009    ,758,758,758
BEGIN DESCRIPTION:
UNT030 IN SPCR 2.0
END DESCRIPTION:
XS GIS Cut Line= 2
       2298930.5     13361461.38      2297548.43     13361762.08
#Sta/Elev= 30
  4310.9  353.49    4360  351.57  4406.2  350.68  4477.5  348.52  4688.4  344.62
  4897.1  342.99    4938  343.29  4972.7  342.94  4978.7  342.35    4982  342.85
  5021.8  343.19  5060.7  343.23  5091.5  344.13  5193.9  344.91  5214.3  345.79
  5224.6  346.76  5234.8  346.59  5245.5  347.81  5265.5  348.33  5275.7  347.69
    5296  347.84  5446.8  353.98  5498.6     356  5552.1  358.76  5580.4  359.72
    5593  360.67  5623.7  361.38  5629.5  362.25  5695.3  364.58  5725.3  366.32
#Mann= 7 ,-1 , 0
  4310.9      .1       0  4406.2     .05       0    4938     .03       0
  5021.8     .05       0  5245.5      .1       0  5446.8     .05       0
  5498.6      .1       0
Bank Sta=4938,5021.8
XS Rating Curve= 0 ,0
Exp/Cntr=0.3,0.1

Type RM Length L Ch R = 1 ,251     ,0,0,0
BEGIN DESCRIPTION:
UNT030 IN SPCR 1.0
END DESCRIPTION:
XS GIS Cut Line= 4
      2298953.63     13360917.39      2298565.93     13360847.95
      2297796.26     13361015.78       2297507.9     13361332.97
#Sta/Elev= 30
  4246.2  350.09  4323.3  349.85    4444  348.26  4455.4  347.54  4485.9  347.43
  4516.3  346.34    4705  342.26  4803.2  341.43  4904.3  339.49  4924.8  340.39
    4935  339.57  4940.1  339.85  4993.5  338.24  4996.2  337.74  5016.9  338.84
  5047.6  339.38    5077  338.56    5109  338.45  5139.7  339.19    5170     339
  5430.5  345.07  5526.5  348.92  5548.1  350.66  5583.2  351.45  5689.3  356.57
  5739.3  357.75  5746.1  358.62  5774.5  359.19  5823.8  362.05  5856.5  362.92
#Mann= 4 ,-1 , 0
  4246.2     .03       0  4940.1    .025       0  5047.6     .03       0
  5856.5      .1       0
Bank Sta=4940.1,5047.6
XS Rating Curve= 0 ,0
Exp/Cntr=0.3,0.1

Chan Stop Cuts=-1
Use User Specified Reach Order=0
Composite Channel Slope=5