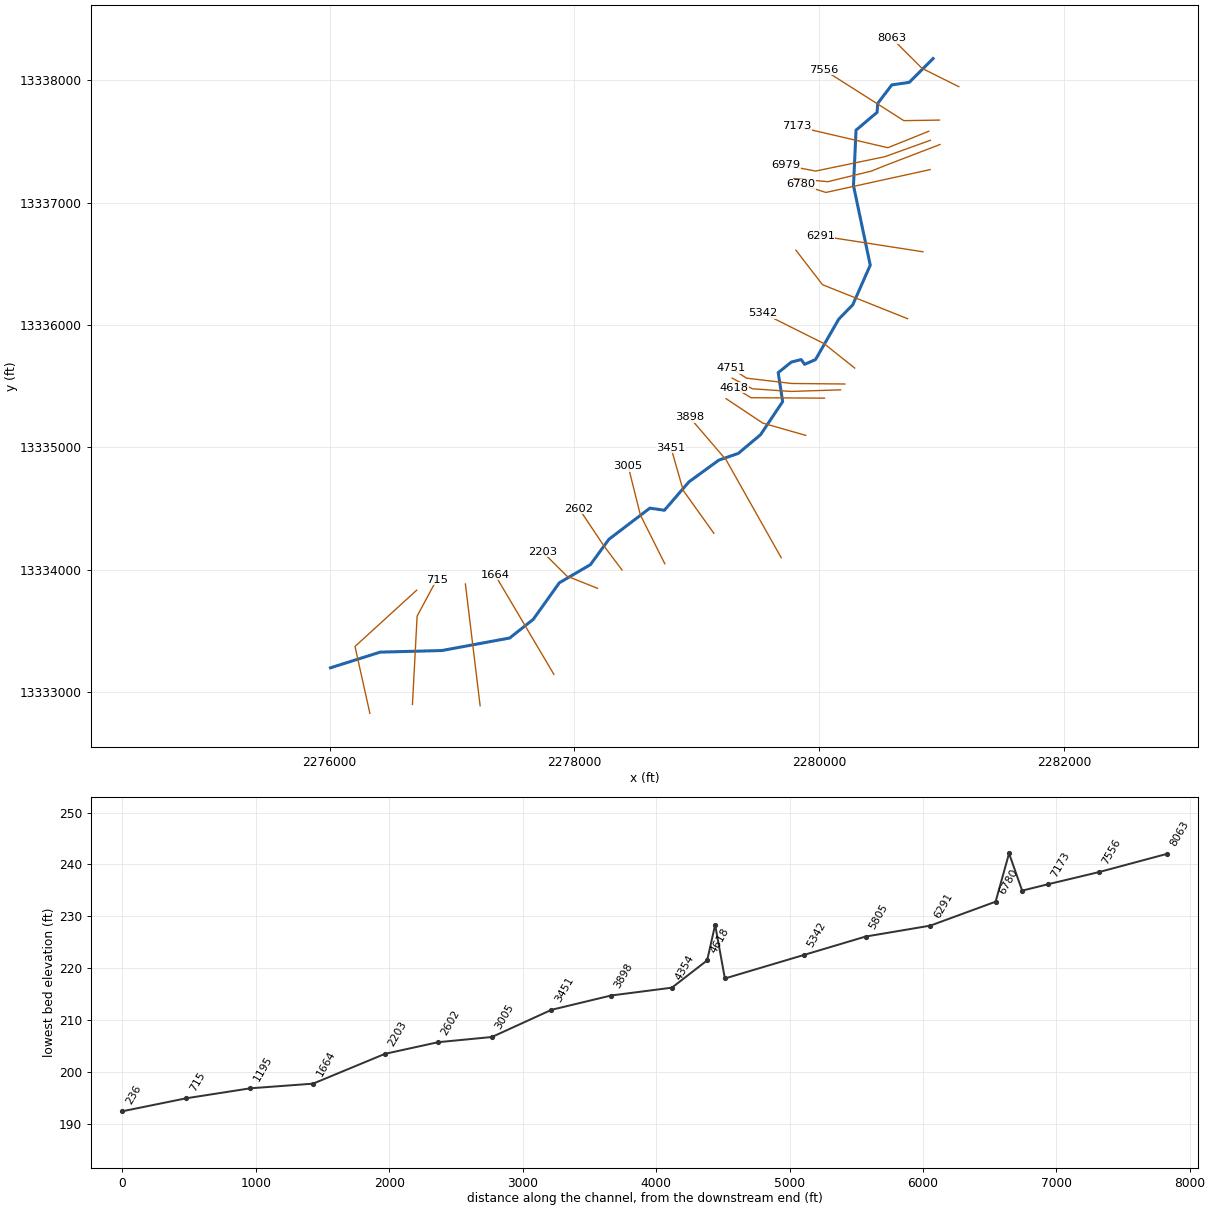
--- UNT032 IN SPCR.prj (project) ---

Proj Title=UNT032 IN SPCR Base Level Engineering
Current Plan=p01
Default Exp/Contr=0.3,0.1
English Units
Geom File=g01
Flow File=f01
Plan File=p01
BEGIN DESCRIPTION:
UNT032 IN SPCR
END DESCRIPTION:

--- UNT032 IN SPCR.p01 (plan) ---

Plan Title=Multiple Run
Short Identifier=Multiple
Geom File=g01
Flow File=f01
Subcritical Flow
K Sum by GR= 0
Std Step Tol= 0.01
Critical Tol= 0.01
Num of Std Step Trials= 20
Max Error Tol= 0.3
Flow Tol Ratio= 0.001
Split Flow NTrial= 30
Split Flow Tol= 0.02
Split Flow Ratio= 0.02
Log Output Level= 0
Friction Slope Method= 1
Unsteady Friction Slope Method= 2
Unsteady Bridges Friction Slope Method= 1
Parabolic Critical Depth
Global Vel Dist=  1 , 1 , 1
Global Log Level= 0
CheckData=True
Encroach Param= -1, 0, 0, 0
BEGIN DESCRIPTION:
Multiple Run
END DESCRIPTION:

--- UNT032 IN SPCR.f01 (steady flow) ---

Flow Title=Multiple
Number of Profiles=7
Profile Names=10-year,25-year,50-year,1pct_min,100-year,1pct_plu,500-year
River Rch & RM= UNT032 IN SPCR,Reach-1,8063
     202     277     338     304     411     556     617
River Rch & RM= UNT032 IN SPCR,Reach-1,7173
     318     445     551     502     679     918    1046
Boundary for River Rch & Prof#=UNT032 IN SPCR,Reach-1,1
Up Type=0
Dn Type=3
Dn Slope=0.005
Boundary for River Rch & Prof#=UNT032 IN SPCR,Reach-1,2
Up Type=0
Dn Type=3
Dn Slope=0.005
Boundary for River Rch & Prof#=UNT032 IN SPCR,Reach-1,3
Up Type=0
Dn Type=3
Dn Slope=0.005
Boundary for River Rch & Prof#=UNT032 IN SPCR,Reach-1,4
Up Type=0
Dn Type=3
Dn Slope=0.005
Boundary for River Rch & Prof#=UNT032 IN SPCR,Reach-1,5
Up Type=0
Dn Type=3
Dn Slope=0.005
Boundary for River Rch & Prof#=UNT032 IN SPCR,Reach-1,6
Up Type=0
Dn Type=3
Dn Slope=0.005
Boundary for River Rch & Prof#=UNT032 IN SPCR,Reach-1,7
Up Type=0
Dn Type=3
Dn Slope=0.005

--- UNT032 IN SPCR.g01 (geometry) ---

Geom Title=Existing Conditions

River Reach=UNT032 IN SPCR,Reach-1
Reach XY= 30
      2280927.72     13338176.85      2280733.03     13337982.37
      2280590.53     13337961.36      2280475.95     13337810.32
      2280470.74     13337737.40      2280298.86     13337591.57
      2280278.03     13337138.44      2280414.86     13336488.03
      2280271.96     13336164.25      2280157.72     13336046.85
      2279967.92     13335716.35      2279879.38     13335677.29
      2279850.73     13335716.35      2279770.00     13335695.52
      2279663.23     13335609.58      2279699.69     13335372.60
      2279519.38     13335102.24      2279336.80     13334949.08
      2279178.64     13334894.50      2278934.10     13334716.40
      2278734.19     13334484.75      2278615.27     13334501.86
      2278281.25     13334247.44      2278130.75     13334040.46
      2277876.00     13333891.50      2277663.47     13333592.89
      2277470.95     13333440.43      2276917.49     13333338.02
      2276413.32     13333325.00      2276007.72     13333196.86

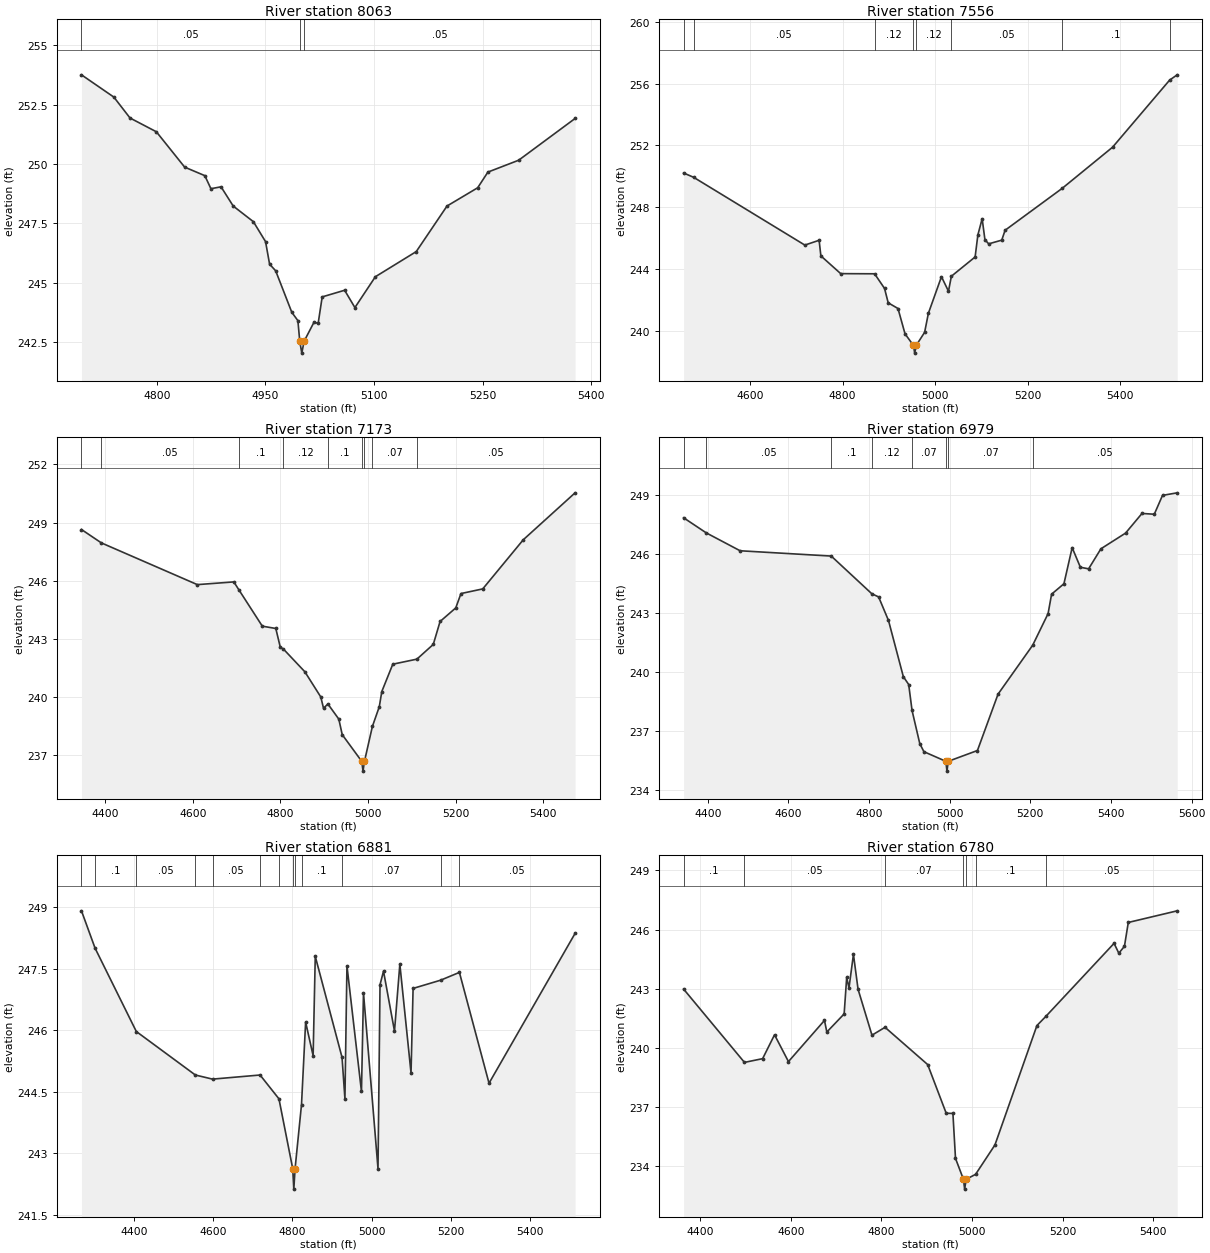
Type RM Length L Ch R = 1,8063,507,507,507
BEGIN DESCRIPTION:
UNT032 IN SPCR 18.0
END DESCRIPTION:
XS GIS Cut Line= 3
      2281137.76     13337946.84      2280837.72     13338096.85
      2280592.53     13338342.04
#Sta/Elev= 30
  4695.7  253.76  4740.5  252.82  4762.8  251.94  4799.2  251.36  4838.3  249.87
  4866.2  249.51  4874.6  248.96  4888.6  249.04  4905.4  248.23  4933.3  247.57
  4950.1  246.73  4955.7  245.78  4964.1  245.50  4986.4  243.75  4994.8  243.40
  4997.4  242.53  5000.2  242.03  5003.4  242.53  5017.2  243.34  5022.8  243.28
  5028.4  244.40  5059.4  244.68  5073.6  243.95  5101.9  245.25  5158.4  246.31
  5200.9  248.23  5243.3  249.00  5257.4  249.66  5299.9  250.16  5377.9  251.92
#Mann=3,-1,0
  4695.7    0.05       0  4997.4    0.03       0  5003.4    0.05       0
Bank Sta=4997.4,5003.4
Exp/Cntr=0.3,0.1

Type RM Length L Ch R = 1,7556,383,383,383
BEGIN DESCRIPTION:
UNT032 IN SPCR 17.0
END DESCRIPTION:
XS GIS Cut Line= 3
      2280979.85     13337673.76      2280689.05     13337669.42
      2280033.63     13338086.11
#Sta/Elev= 30
  4456.2  250.21  4478.0  249.93  4718.4  245.54  4749.3  245.85  4753.1  244.84
  4796.0  243.69  4869.3  243.68  4890.8  242.73  4898.7  241.80  4919.9  241.43
  4935.1  239.79  4953.3  239.04  4956.0  238.54  4959.3  239.04  4977.5  239.89
  4985.6  241.12  5013.9  243.49  5029.1  242.55  5035.3  243.52  5086.7  244.77
  5092.6  246.19  5101.9  247.25  5107.9  245.89  5116.0  245.62  5144.3  245.86
  5151.5  246.50  5275.2  249.22  5383.9  251.88  5507.4  256.23  5523.7  256.57
#Mann=8,-1,0
  4456.2     0.1       0  4478.0    0.05       0  4869.3    0.12       0
  4953.3    0.07       0  4959.3    0.12       0  5035.3    0.05       0
  5275.2     0.1       0  5507.4    0.05       0
Bank Sta=4953.3,4959.3
Exp/Cntr=0.3,0.1

Type RM Length L Ch R = 1,7173,194,194,194
BEGIN DESCRIPTION:
UNT032 IN SPCR 16.0
END DESCRIPTION:
XS GIS Cut Line= 3
      2280893.02     13337582.61      2280558.84     13337448.07
      2279812.51     13337621.63
#Sta/Elev= 30
  4346.1  248.64  4391.5  247.95  4610.5  245.80  4693.8  245.94  4705.4  245.53
  4758.8  243.66  4789.6  243.54  4799.9  242.57  4807.0  242.48  4855.9  241.31
  4892.3  240.01  4898.5  239.43  4908.5  239.65  4933.4  238.87  4941.2  238.07
  4985.9  236.69  4988.6  236.19  4991.9  236.69  5010.0  238.49  5025.8  239.51
  5031.5  240.29  5056.6  241.70  5111.6  241.96  5149.0  242.72  5164.5  243.90
  5200.3  244.60  5212.2  245.34  5261.9  245.58  5354.3  248.11  5472.6  250.53
#Mann=9,-1,0
  4346.1     0.1       0  4391.5    0.05       0  4705.4     0.1       0
  4807.0    0.12       0  4908.5     0.1       0  4985.9    0.07       0
  4991.9     0.1       0  5010.0    0.07       0  5111.6    0.05       0
Bank Sta=4985.9,4991.9
Exp/Cntr=0.3,0.1

Type RM Length L Ch R = 1,6979,98,98,98
BEGIN DESCRIPTION:
Mapping XS c653ee16
END DESCRIPTION:
XS GIS Cut Line= 4
      2280906.09     13337508.84      2280532.80     13337374.28
      2279968.57     13337257.10      2279721.99     13337304.68
#Sta/Elev= 30
  4340.0  247.86  4396.3  247.09  4480.2  246.18  4706.2  245.91  4806.9  243.99
  4823.7  243.83  4848.2  242.63  4885.0  239.77  4898.3  239.37  4906.6  238.05
  4925.8  236.36  4936.0  235.95  4990.4  235.46  4993.2  234.96  4996.4  235.46
  5068.8  236.01  5119.9  238.88  5205.8  241.37  5244.0  242.98  5252.7  243.97
  5283.3  244.50  5303.7  246.34  5324.1  245.34  5344.5  245.26  5375.0  246.28
  5436.2  247.08  5476.9  248.08  5507.4  248.04  5527.8  249.00  5564.2  249.13
#Mann=8,-1,0
  4340.0     0.1       0  4396.3    0.05       0  4706.2     0.1       0
  4806.9    0.12       0  4906.6    0.07       0  4990.4    0.07       0
  4996.4    0.07       0  5205.8    0.05       0
Bank Sta=4990.4,4996.4
Exp/Cntr=0.3,0.1

Type RM Length L Ch R = 1,6881,101,101,101
BEGIN DESCRIPTION:
Mapping XS 47863cc7
END DESCRIPTION:
XS GIS Cut Line= 5
      2280984.22     13337474.12      2280554.50     13337309.18
      2280424.29     13337257.10      2280068.39     13337170.29
      2279791.67     13337196.23
#Sta/Elev= 30
  4267.9  248.91  4302.2  248.00  4406.2  245.97  4555.1  244.91  4598.4  244.81
  4718.3  244.91  4765.9  244.33  4800.6  242.63  4803.4  242.13  4806.6  242.63
  4822.8  244.19  4833.2  246.20  4852.1  245.38  4857.5  247.80  4925.0  245.34
  4932.3  244.33  4937.4  247.57  4974.0  244.51  4979.1  246.91  5015.7  242.63
  5020.8  247.11  5029.6  247.44  5057.3  245.98  5070.8  247.61  5099.0  244.96
  5104.2  247.02  5173.6  247.22  5221.0  247.41  5295.7  244.71  5512.7  248.36
#Mann=13,-1,0
  4267.9    0.05       0  4302.2     0.1       0  4406.2    0.05       0
  4555.1     0.1       0  4598.4    0.05       0  4718.3     0.1       0
  4765.9    0.05       0  4800.6    0.07       0  4806.6    0.05       0
  4822.8     0.1       0  4925.0    0.07       0  5173.6     0.1       0
  5221.0    0.05       0
Bank Sta=4800.6,4806.6
Exp/Cntr=0.3,0.1

Type RM Length L Ch R = 1,6780,489,489,489
BEGIN DESCRIPTION:
UNT032 IN SPCR 15.0
END DESCRIPTION:
XS GIS Cut Line= 3
      2280903.79     13337269.07      2280053.10     13337082.44
      2279844.76     13337147.54
#Sta/Elev= 30
  4363.5  242.98  4497.8  239.26  4537.9  239.45  4564.2  240.66  4594.9  239.30
  4674.4  241.39  4679.6  240.80  4717.8  241.72  4723.4  243.57  4728.5  243.04
  4738.3  244.74  4748.5  242.97  4779.2  240.64  4808.0  241.04  4902.1  239.15
  4943.0  236.68  4957.8  236.67  4963.5  234.39  4981.0  233.33  4983.7  232.83
  4987.0  233.33  5007.8  233.58  5050.5  235.07  5143.2  241.13  5163.1  241.60
  5313.4  245.30  5323.9  244.80  5336.3  245.15  5344.8  246.36  5452.7  246.95
#Mann=7,-1,0
  4363.5     0.1       0  4497.8    0.05       0  4808.0    0.07       0
  4981.0    0.07       0  4987.0    0.07       0  5007.8     0.1       0
  5163.1    0.05       0
Bank Sta=4981,4987
Exp/Cntr=0.3,0.1

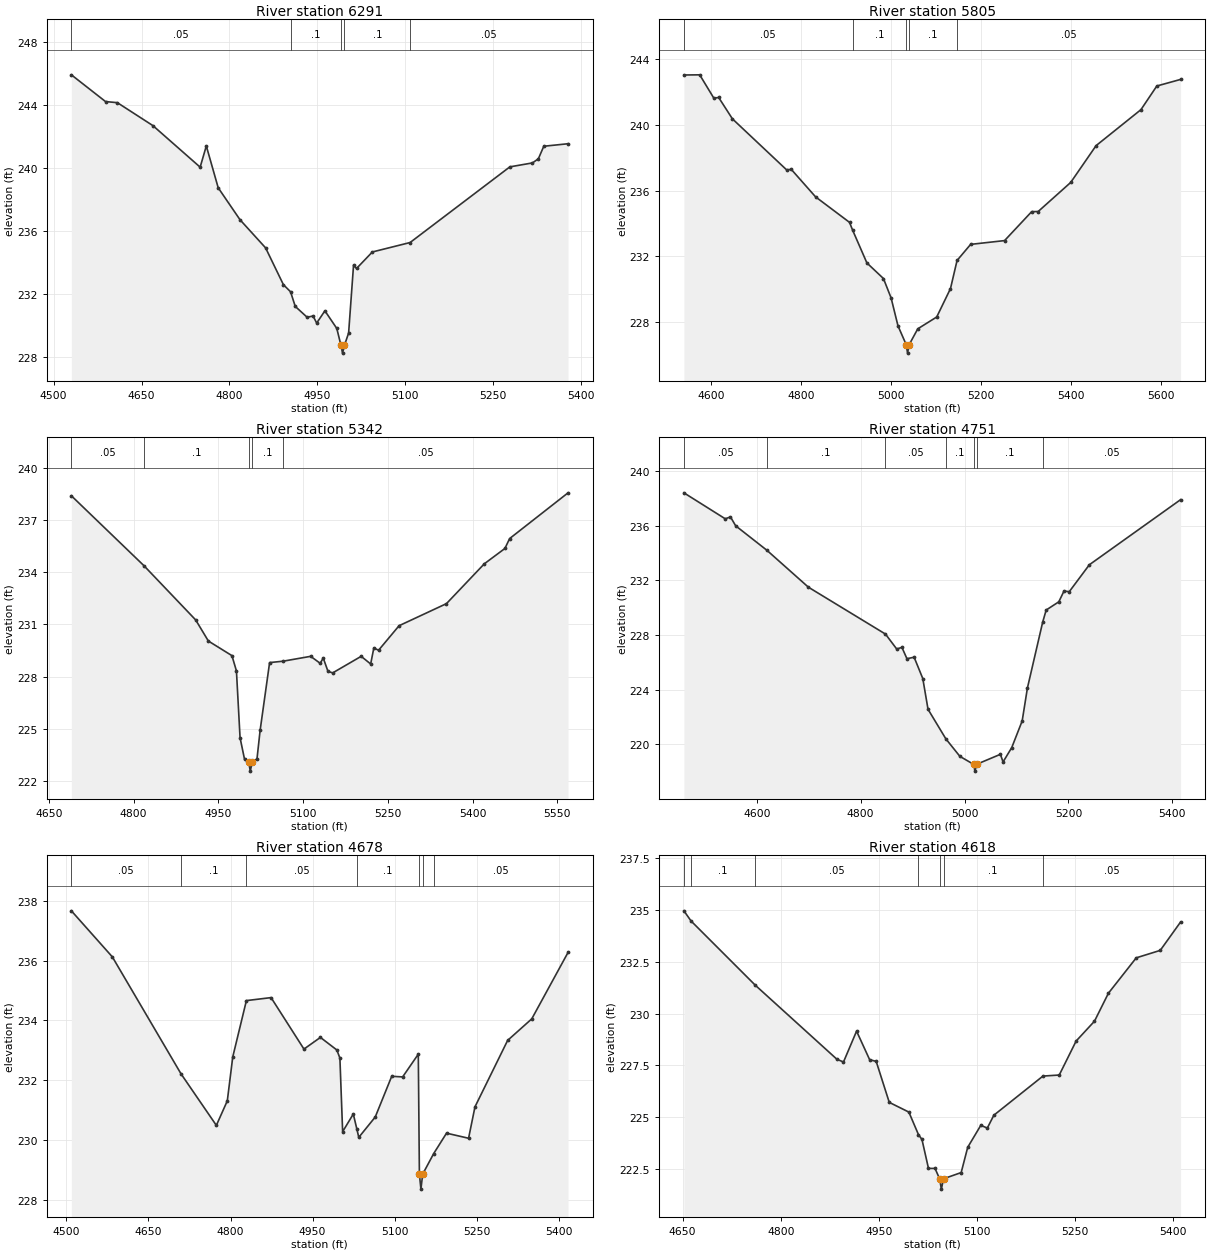
Type RM Length L Ch R = 1,6291,486,486,486
BEGIN DESCRIPTION:
UNT032 IN SPCR 14.0
END DESCRIPTION:
XS GIS Cut Line= 2
      2280845.31     13336597.37      2280007.67     13336727.57
#Sta/Elev= 30
  4530.2  245.91  4588.5  244.21  4608.7  244.14  4669.4  242.68  4750.0  240.04
  4760.5  241.39  4780.8  238.73  4818.0  236.70  4861.7  234.91  4892.1  232.57
  4904.3  232.12  4912.3  231.19  4932.6  230.50  4942.7  230.58  4948.9  230.13
  4962.9  230.91  4983.2  229.79  4990.3  228.72  4993.0  228.22  4996.3  228.72
  5003.4  229.50  5011.8  233.81  5016.9  233.60  5043.9  234.65  5108.3  235.25
  5278.6  240.06  5317.1  240.31  5327.2  240.57  5336.5  241.37  5377.9  241.53
#Mann=5,-1,0
  4530.2    0.05       0  4904.3     0.1       0  4990.3    0.07       0
  4996.3     0.1       0  5108.3    0.05       0
Bank Sta=4990.3,4996.3
Exp/Cntr=0.3,0.1

Type RM Length L Ch R = 1,5805,463,463,463
BEGIN DESCRIPTION:
UNT032 IN SPCR 13.0
END DESCRIPTION:
XS GIS Cut Line= 3
      2280719.47     13336050.49      2280024.99     13336328.28
      2279807.98     13336610.39
#Sta/Elev= 30
  4539.3  243.04  4574.4  243.05  4605.8  241.63  4616.6  241.67  4647.1  240.37
  4767.4  237.27  4778.1  237.29  4832.0  235.62  4907.4  234.07  4914.2  233.60
  4946.0  231.60  4982.8  230.65  4999.8  229.47  5015.1  227.77  5033.6  226.61
  5036.4  226.11  5039.6  226.61  5059.1  227.59  5101.2  228.31  5131.8  230.04
  5146.4  231.75  5176.6  232.73  5252.0  232.96  5312.2  234.72  5326.7  234.73
  5399.0  236.50  5455.4  238.74  5555.1  240.93  5590.4  242.37  5643.2  242.77
#Mann=5,-1,0
  4539.3    0.05       0  4914.2     0.1       0  5033.6    0.07       0
  5039.6     0.1       0  5146.4    0.05       0
Bank Sta=5033.6,5039.6
Exp/Cntr=0.3,0.1

Type RM Length L Ch R = 1,5342,591,591,591
BEGIN DESCRIPTION:
UNT032 IN SPCR 12.0
END DESCRIPTION:
XS GIS Cut Line= 3
      2280287.73     13335646.85      2280037.72     13335846.85
      2279537.71     13336096.86
#Sta/Elev= 30
  4689.7  238.39  4818.2  234.37  4909.8  231.25  4932.2  230.04  4973.9  229.20
  4981.9  228.32  4988.3  224.48  4996.3  223.23  5003.7  223.06  5006.4  222.56
  5009.7  223.06  5018.3  223.27  5023.8  224.90  5040.6  228.80  5064.4  228.88
  5113.3  229.16  5130.1  228.76  5135.6  229.06  5144.0  228.29  5152.4  228.21
  5202.7  229.16  5219.5  228.72  5225.1  229.64  5233.5  229.51  5269.8  230.92
  5353.7  232.19  5420.7  234.48  5457.1  235.36  5465.5  235.93  5568.9  238.56
#Mann=5,-1,0
  4689.7    0.05       0  4818.2     0.1       0  5003.7    0.07       0
  5009.7     0.1       0  5064.4    0.05       0
Bank Sta=5003.7,5009.7
Exp/Cntr=0.3,0.1

Type RM Length L Ch R = 1,4751,73,73,73
BEGIN DESCRIPTION:
Mapping XS e3bca8fd
END DESCRIPTION:
XS GIS Cut Line= 4
      2280207.31     13335516.64      2279773.25     13335520.98
      2279404.33     13335564.39      2279278.48     13335646.84
#Sta/Elev= 30
  4459.9  238.39  4539.5  236.49  4549.5  236.63  4559.5  235.98  4619.6  234.19
  4699.5  231.49  4847.9  228.06  4869.5  226.97  4879.5  227.09  4889.2  226.26
  4903.0  226.37  4919.7  224.81  4929.8  222.56  4964.1  220.40  4991.1  219.12
  5017.4  218.54  5020.1  218.04  5023.4  218.54  5069.1  219.27  5074.2  218.71
  5090.9  219.76  5111.0  221.71  5121.1  224.12  5150.5  228.94  5157.2  229.82
  5181.5  230.42  5191.5  231.21  5201.6  231.16  5240.3  233.13  5415.9  237.89
#Mann=7,-1,0
  4459.9    0.05       0  4619.6     0.1       0  4847.9    0.05       0
  4964.1     0.1       0  5017.4    0.07       0  5023.4     0.1       0
  5150.5    0.05       0
Bank Sta=5017.4,5023.4
Exp/Cntr=0.3,0.1

Type RM Length L Ch R = 1,4678,60,60,60
BEGIN DESCRIPTION:
Mapping XS 594fbe05
END DESCRIPTION:
XS GIS Cut Line= 4
      2280172.56     13335468.90      2279768.91     13335455.88
      2279452.07     13335477.58      2279287.16     13335564.38
#Sta/Elev= 30
  4509.1  237.66  4584.0  236.12  4709.6  232.21  4774.1  230.49  4794.1  231.31
  4804.1  232.78  4829.0  234.66  4874.1  234.76  4934.2  233.04  4964.3  233.43
  4994.3  233.01  4999.9  232.74  5004.9  230.28  5024.4  230.87  5031.0  230.36
  5034.4  230.09  5064.5  230.77  5094.6  232.13  5114.6  232.11  5143.2  232.87
  5145.2  228.86  5148.0  228.36  5151.2  228.86  5171.4  229.55  5194.8  230.23
  5235.1  230.06  5246.8  231.11  5306.5  233.33  5350.6  234.05  5416.9  236.27
#Mann=7,-1,0
  4509.1    0.05       0  4709.6     0.1       0  4829.0    0.05       0
  5031.0     0.1       0  5145.2    0.03       0  5151.2     0.1       0
  5171.4    0.05       0
Bank Sta=5145.2,5151.2
Exp/Cntr=0.3,0.1

Type RM Length L Ch R = 1,4618,264,264,264
BEGIN DESCRIPTION:
UNT032 IN SPCR 11.0
END DESCRIPTION:
XS GIS Cut Line= 3
      2280041.78     13335401.02      2279441.12     13335404.49
      2279305.68     13335487.83
#Sta/Elev= 30
  4651.9  234.96  4662.8  234.47  4761.0  231.37  4886.0  227.79  4896.0  227.66
  4916.0  229.15  4936.0  227.77  4946.0  227.69  4966.0  225.71  4996.0  225.24
  5010.7  224.15  5016.0  223.92  5026.0  222.52  5036.0  222.52  5043.0  222.02
  5045.7  221.52  5049.0  222.02  5076.0  222.32  5086.0  223.54  5106.0  224.60
  5116.0  224.47  5126.0  225.09  5201.1  226.98  5226.0  227.03  5251.8  228.67
  5279.9  229.63  5301.2  230.98  5343.8  232.69  5380.5  233.05  5411.6  234.42
#Mann=7,-1,0
  4651.9    0.05       0  4662.8     0.1       0  4761.0    0.05       0
  5010.7     0.1       0  5043.0    0.03       0  5049.0     0.1       0
  5201.1    0.05       0
Bank Sta=5043,5049
Exp/Cntr=0.3,0.1

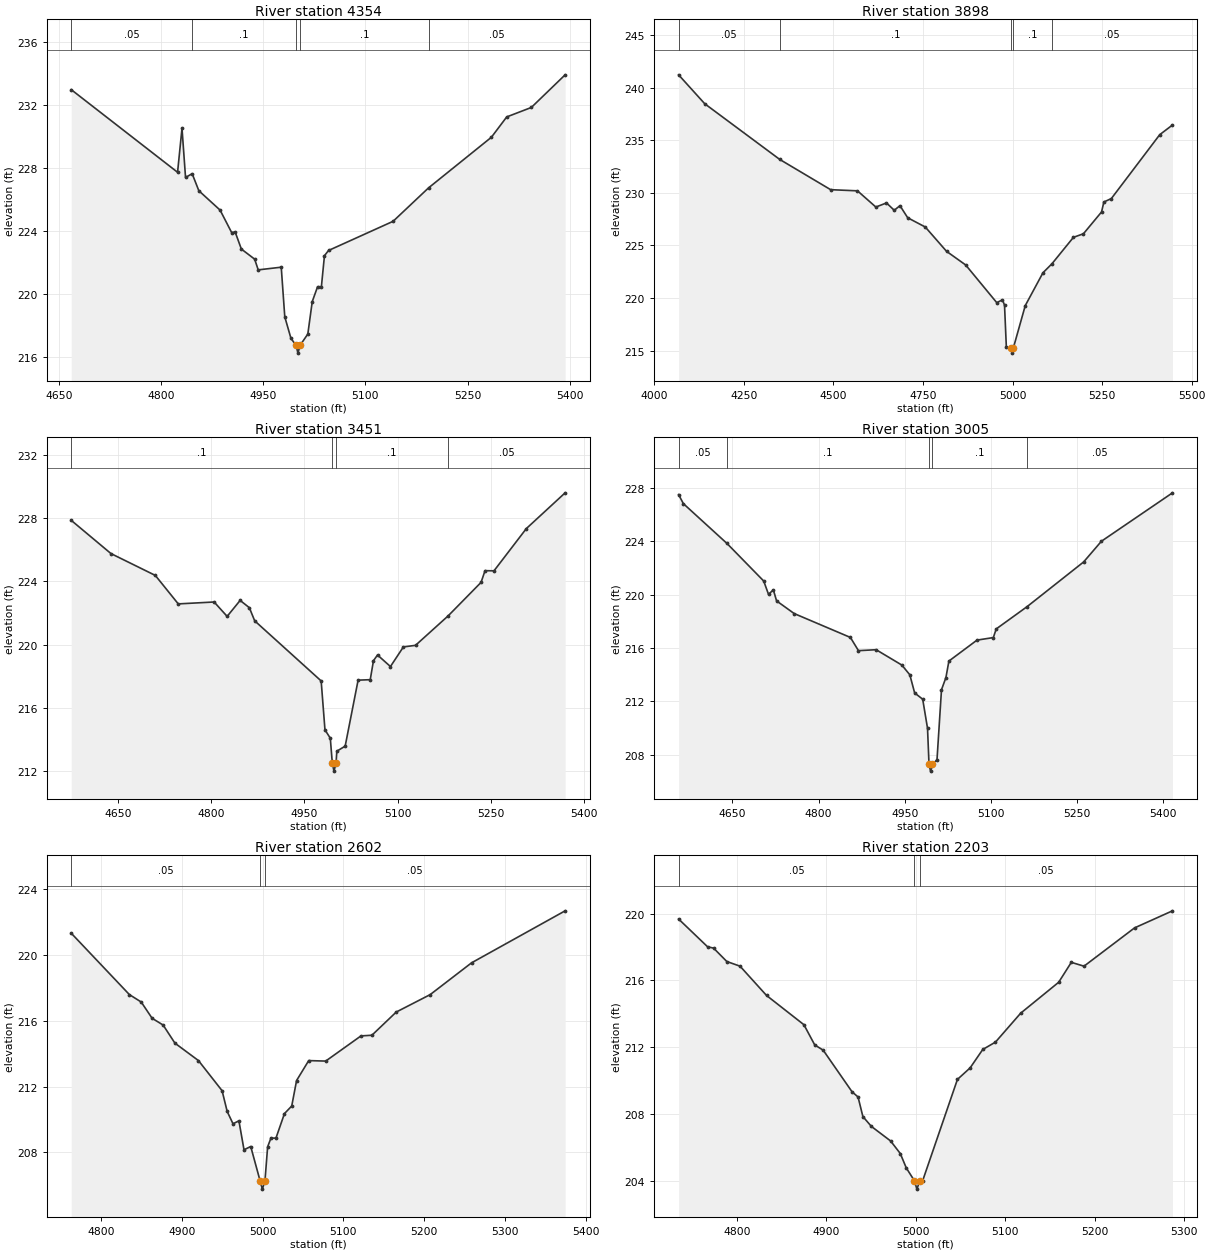
Type RM Length L Ch R = 1,4354,456,456,456
BEGIN DESCRIPTION:
UNT032 IN SPCR 10.0
END DESCRIPTION:
XS GIS Cut Line= 3
      2279887.74     13335096.85      2279537.72     13335196.85
      2279237.70     13335396.87
#Sta/Elev= 30
  4668.4  232.98  4824.4  227.74  4830.9  230.53  4836.1  227.41  4845.8  227.65
  4855.6  226.57  4886.8  225.34  4903.7  223.92  4908.9  223.95  4918.0  222.87
  4937.5  222.23  4942.7  221.55  4976.5  221.72  4981.7  218.57  4990.8  217.20
  4998.2  216.77  5001.0  216.27  5004.2  216.77  5015.5  217.48  5022.0  219.54
  5029.8  220.48  5035.4  220.48  5039.9  222.45  5045.9  222.78  5140.6  224.63
  5192.6  226.75  5284.8  229.96  5307.3  231.25  5343.4  231.85  5393.0  233.92
#Mann=5,-1,0
  4668.4    0.05       0  4845.8     0.1       0  4998.2    0.07       0
  5004.2     0.1       0  5192.6    0.05       0
Bank Sta=4998.2,5004.2
Exp/Cntr=0.3,0.1

Type RM Length L Ch R = 1,3898,447,447,447
BEGIN DESCRIPTION:
UNT032 IN SPCR 9.0
END DESCRIPTION:
XS GIS Cut Line= 3
      2279687.72     13334096.86      2279237.72     13334896.85
      2278937.75     13335246.82
#Sta/Elev= 30
  4067.7  241.22  4140.7  238.47  4349.9  233.18  4492.2  230.30  4567.1  230.19
  4618.4  228.65  4648.1  229.04  4669.7  228.34  4685.7  228.78  4707.3  227.63
  4756.4  226.75  4815.7  224.44  4869.2  223.14  4955.9  219.56  4971.9  219.83
  4977.6  219.32  4982.7  215.32  4996.3  215.26  4999.0  214.76  5002.3  215.26
  5035.5  219.28  5084.9  222.40  5110.1  223.26  5170.0  225.77  5197.9  226.11
  5248.4  228.18  5255.0  229.13  5275.9  229.46  5410.9  235.53  5446.5  236.45
#Mann=5,-1,0
  4067.7    0.05       0  4349.9     0.1       0  4996.3    0.07       0
  5002.3     0.1       0  5110.1    0.05       0
Bank Sta=4996.3,5002.3
Exp/Cntr=0.3,0.1

Type RM Length L Ch R = 1,3451,446,446,446
BEGIN DESCRIPTION:
UNT032 IN SPCR 8.0
END DESCRIPTION:
XS GIS Cut Line= 3
      2279137.74     13334296.83      2278887.72     13334646.85
      2278787.71     13334996.90
#Sta/Elev= 30
  4575.1  227.85  4639.0  225.75  4710.3  224.37  4747.2  222.57  4804.9  222.69
  4825.8  221.78  4846.7  222.79  4861.5  222.33  4870.1  221.50  4977.0  217.70
  4983.1  214.61  4991.7  214.08  4994.9  212.50  4997.6  212.00  5000.9  212.50
  5002.2  213.26  5015.6  213.58  5036.4  217.75  5055.9  217.78  5061.1  218.98
  5067.6  219.34  5088.4  218.61  5109.2  219.85  5128.7  219.95  5181.1  221.81
  5234.1  223.93  5240.5  224.67  5254.9  224.66  5306.9  227.33  5369.3  229.59
#Mann=4,-1,0
  4575.1     0.1       0  4994.9    0.07       0  5000.9     0.1       0
  5181.1    0.05       0
Bank Sta=4994.9,5000.9
Exp/Cntr=0.3,0.1

Type RM Length L Ch R = 1,3005,403,403,403
BEGIN DESCRIPTION:
UNT032 IN SPCR 7.0
END DESCRIPTION:
XS GIS Cut Line= 3
      2278737.70     13334046.89      2278537.72     13334446.85
      2278437.72     13334846.87
#Sta/Elev= 30
  4556.3  227.50  4564.6  226.82  4640.4  223.84  4704.4  221.02  4712.8  220.02
  4721.2  220.36  4726.8  219.53  4757.5  218.58  4855.3  216.79  4869.3  215.80
  4900.1  215.87  4944.8  214.72  4958.7  213.99  4967.1  212.63  4981.1  212.16
  4989.5  209.98  4992.1  207.27  4994.8  206.77  4998.1  207.27  5006.0  207.63
  5013.8  212.87  5021.5  213.78  5026.7  215.02  5075.6  216.59  5104.0  216.78
  5109.1  217.43  5162.8  219.10  5261.2  222.45  5292.1  224.00  5415.8  227.63
#Mann=5,-1,0
  4556.3    0.05       0  4640.4     0.1       0  4992.1    0.07       0
  4998.1     0.1       0  5162.8    0.05       0
Bank Sta=4992.1,4998.1
Exp/Cntr=0.3,0.1

Type RM Length L Ch R = 1,2602,399,399,399
BEGIN DESCRIPTION:
UNT032 IN SPCR 6.0
END DESCRIPTION:
XS GIS Cut Line= 3
      2278387.75     13333996.82      2278237.72     13334196.85
      2278037.72     13334496.85
#Sta/Elev= 30
  4763.5  221.32  4835.4  217.59  4850.0  217.14  4863.5  216.15  4877.1  215.74
  4891.7  214.64  4920.8  213.58  4950.0  211.75  4956.3  210.49  4963.5  209.74
  4970.8  209.92  4977.1  208.16  4985.4  208.36  4997.0  206.27  4999.8  205.77
  5003.0  206.27  5006.3  208.34  5010.4  208.87  5016.6  208.87  5027.1  210.36
  5036.1  210.82  5042.1  212.37  5057.1  213.58  5078.1  213.55  5121.7  215.08
  5135.2  215.12  5165.3  216.53  5207.3  217.59  5258.4  219.52  5374.1  222.68
#Mann=3,-1,0
  4763.5    0.05       0  4997.0    0.03       0  5003.0    0.05       0
Bank Sta=4997,5003
Exp/Cntr=0.3,0.1

Type RM Length L Ch R = 1,2203,539,539,539
BEGIN DESCRIPTION:
UNT032 IN SPCR 5.0
END DESCRIPTION:
XS GIS Cut Line= 3
      2278187.76     13333846.84      2277937.72     13333946.85
      2277737.75     13334146.82
#Sta/Elev= 30
  4734.7  219.67  4767.1  218.01  4773.8  217.93  4788.6  217.13  4803.4  216.85
  4833.0  215.10  4874.8  213.35  4886.9  212.14  4896.3  211.83  4928.6  209.34
  4935.3  209.03  4940.7  207.86  4950.2  207.27  4971.7  206.40  4982.5  205.65
  4989.2  204.79  4998.3  204.02  5001.1  203.52  5004.3  204.02  5007.5  204.02
  5046.4  210.08  5060.6  210.77  5074.7  211.87  5088.9  212.31  5117.1  214.04
  5159.6  215.89  5173.7  217.08  5187.9  216.85  5244.4  219.14  5286.8  220.16
#Mann=3,-1,0
  4734.7    0.05       0  4998.3    0.03       0  5004.3    0.05       0
Bank Sta=4998.3,5004.3
Exp/Cntr=0.3,0.1

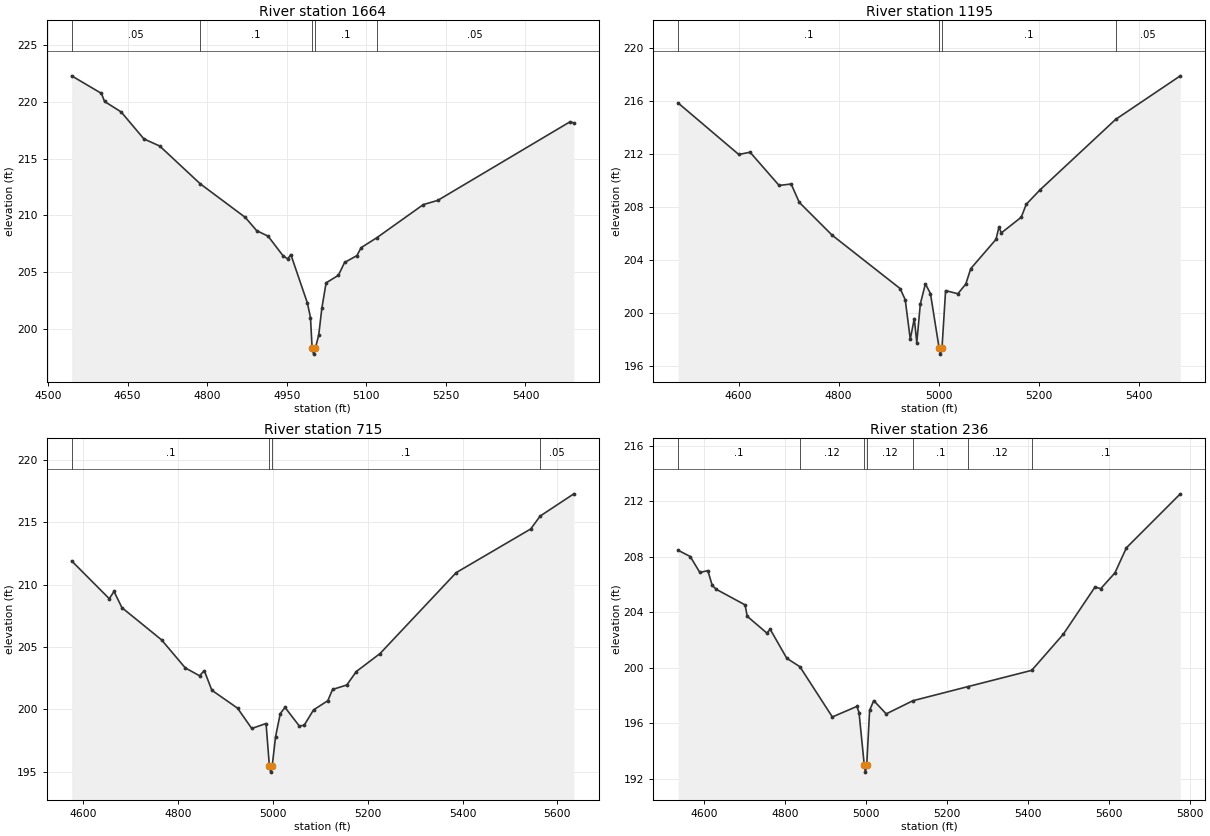
Type RM Length L Ch R = 1,1664,469,469,469
BEGIN DESCRIPTION:
UNT032 IN SPCR 4.0
END DESCRIPTION:
XS GIS Cut Line= 2
      2277831.54     13333143.84      2277350.06     13333959.08
#Sta/Elev= 30
  4544.4  222.31  4600.6  220.76  4606.4  220.05  4637.7  219.13  4680.6  216.75
  4710.5  216.12  4786.9  212.79  4871.8  209.83  4893.3  208.66  4914.7  208.18
  4942.8  206.46  4951.8  206.17  4957.6  206.56  4988.9  202.28  4994.7  201.00
  4997.8  198.28  5000.6  197.78  5003.8  198.28  5010.3  199.49  5016.1  201.82
  5024.1  204.06  5047.3  204.73  5059.0  205.86  5082.1  206.46  5090.3  207.17
  5119.4  208.03  5207.4  210.96  5234.6  211.33  5484.4  218.27  5491.2  218.15
#Mann=5,-1,0
  4544.4    0.05       0  4786.9     0.1       0  4997.8    0.07       0
  5003.8     0.1       0  5119.4    0.05       0
Bank Sta=4997.8,5003.8
Exp/Cntr=0.3,0.1

Type RM Length L Ch R = 1,1195,480,480,480
BEGIN DESCRIPTION:
UNT032 IN SPCR 3.0
END DESCRIPTION:
XS GIS Cut Line= 2
      2277229.67     13332886.64      2277109.32     13333882.20
#Sta/Elev= 30
  4479.4  215.86  4600.5  211.97  4623.1  212.14  4681.1  209.63  4705.1  209.74
  4721.4  208.35  4787.1  205.87  4922.8  201.84  4932.9  201.00  4943.0  198.02
  4951.0  199.58  4956.0  197.76  4963.1  200.69  4973.2  202.20  4983.3  201.46
  5000.4  197.39  5003.1  196.89  5006.4  197.39  5013.5  201.69  5038.0  201.45
  5053.8  202.18  5063.8  203.35  5114.2  205.56  5119.9  206.47  5124.9  206.05
  5164.6  207.23  5174.6  208.21  5201.9  209.29  5353.1  214.62  5482.2  217.91
#Mann=4,-1,0
  4479.4     0.1       0  5000.4    0.07       0  5006.4     0.1       0
  5353.1    0.05       0
Bank Sta=5000.4,5006.4
Exp/Cntr=0.3,0.1

Type RM Length L Ch R = 1,715,479,479,479
BEGIN DESCRIPTION:
UNT032 IN SPCR 2.0
END DESCRIPTION:
XS GIS Cut Line= 3
      2276677.02     13332897.64      2276715.32     13333619.87
      2276873.99     13333915.32
#Sta/Elev= 30
  4576.1  211.91  4655.4  208.88  4665.4  209.46  4682.1  208.16  4765.6  205.58
  4815.6  203.33  4845.7  202.70  4855.7  203.11  4871.6  201.54  4925.8  200.10
  4955.8  198.47  4985.9  198.87  4992.9  195.47  4995.7  194.97  4998.9  195.47
  5005.9  197.80  5015.9  199.67  5025.9  200.16  5056.0  198.67  5066.2  198.73
  5086.0  199.96  5116.1  200.70  5126.1  201.60  5156.1  201.96  5176.2  203.04
  5226.2  204.48  5386.7  210.97  5543.7  214.47  5563.8  215.51  5634.7  217.29
#Mann=4,-1,0
  4576.1     0.1       0  4992.9    0.07       0  4998.9     0.1       0
  5563.8    0.05       0
Bank Sta=4992.9,4998.9
Exp/Cntr=0.3,0.1

Type RM Length L Ch R = 1,236,0,0,0
BEGIN DESCRIPTION:
UNT032 IN SPCR 1.0
END DESCRIPTION:
XS GIS Cut Line= 3
      2276329.65     13332824.44      2276208.12     13333371.31
      2276711.57     13333831.36
#Sta/Elev= 30
  4535.0  208.47  4565.0  208.02  4588.7  206.87  4608.6  207.00  4619.4  205.93
  4629.7  205.65  4700.7  204.53  4705.9  203.71  4754.5  202.50  4762.8  202.77
  4803.8  200.68  4836.3  200.07  4916.5  196.45  4977.3  197.21  4982.5  196.77
  4995.5  192.97  4998.2  192.47  5001.5  192.97  5008.7  196.93  5018.9  197.63
  5049.7  196.67  5115.8  197.62  5252.2  198.64  5409.6  199.81  5487.9  202.42
  5566.2  205.82  5580.4  205.70  5615.5  206.84  5643.9  208.65  5777.2  212.54
#Mann=7,-1,0
  4535.0     0.1       0  4836.3    0.12       0  4995.5    0.07       0
  5001.5    0.12       0  5115.8     0.1       0  5252.2    0.12       0
  5409.6     0.1       0
Bank Sta=4995.5,5001.5
Exp/Cntr=0.3,0.1

Chan Stop Cuts=-1