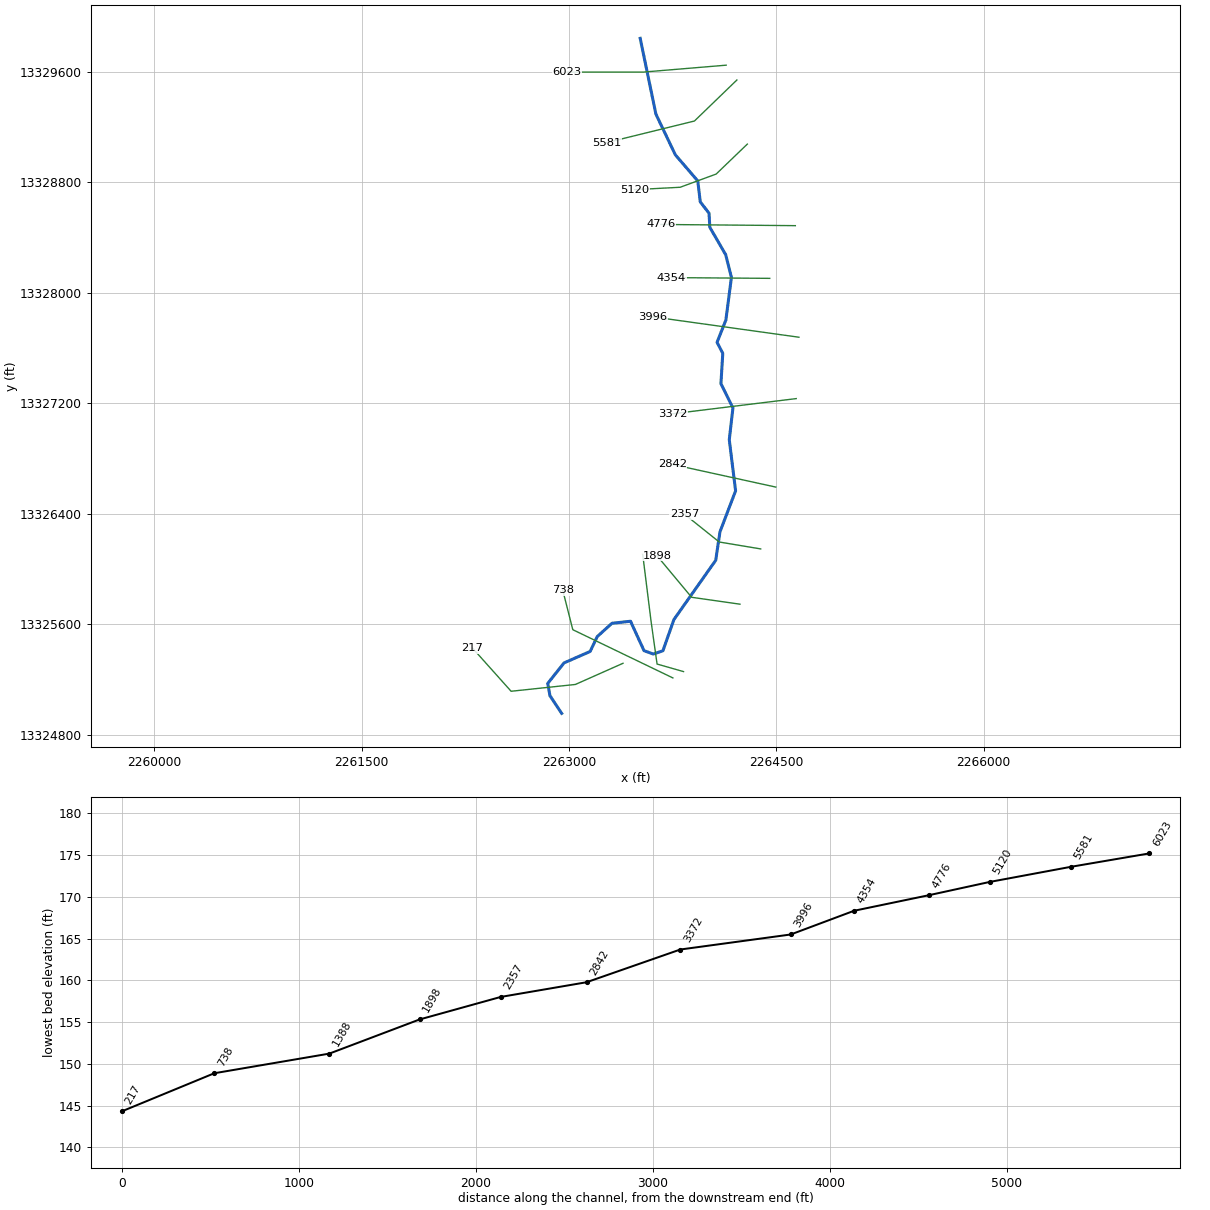
--- UNT033 IN SPCR.prj (project) ---

Proj Title=UNT033 IN SPCR Base Level Engineering
Current Plan=p01
Default Exp/Contr=0.3,0.1
English Units
Geom File=g01
Flow File=f01
Plan File=p01
BEGIN DESCRIPTION:
UNT033 IN SPCR
END DESCRIPTION:

--- UNT033 IN SPCR.p01 (plan) ---

Plan Title=Multiple Run
Short Identifier=Multiple
Geom File=g01
Flow File=f01
Subcritical Flow
K Sum by GR= 0
Std Step Tol= 0.01
Critical Tol= 0.01
Num of Std Step Trials= 20
Max Error Tol= 0.3
Flow Tol Ratio= 0.001
Split Flow NTrial= 30
Split Flow Tol= 0.02
Split Flow Ratio= 0.02
Log Output Level= 0
Friction Slope Method= 1
Unsteady Friction Slope Method= 2
Unsteady Bridges Friction Slope Method= 1
Parabolic Critical Depth
Global Vel Dist=  1 , 1 , 1
Global Log Level= 0
CheckData=True
Encroach Param= -1, 0, 0, 0
BEGIN DESCRIPTION:
Multiple Run
END DESCRIPTION:

--- UNT033 IN SPCR.f01 (steady flow) ---

Flow Title=Multiple
Number of Profiles=7
Profile Names=10-year,25-year,50-year,1pct_min,100-year,1pct_plu,500-year
River Rch & RM= UNT033 IN SPCR,Reach-1,6023
     291     403     496     448     606     820     920
River Rch & RM= UNT033 IN SPCR,Reach-1,4354
     332     463     573     520     704     952    1079
Boundary for River Rch & Prof#=UNT033 IN SPCR,Reach-1,1
Up Type=0
Dn Type=3
Dn Slope=0.005
Boundary for River Rch & Prof#=UNT033 IN SPCR,Reach-1,2
Up Type=0
Dn Type=3
Dn Slope=0.005
Boundary for River Rch & Prof#=UNT033 IN SPCR,Reach-1,3
Up Type=0
Dn Type=3
Dn Slope=0.005
Boundary for River Rch & Prof#=UNT033 IN SPCR,Reach-1,4
Up Type=0
Dn Type=3
Dn Slope=0.005
Boundary for River Rch & Prof#=UNT033 IN SPCR,Reach-1,5
Up Type=0
Dn Type=3
Dn Slope=0.005
Boundary for River Rch & Prof#=UNT033 IN SPCR,Reach-1,6
Up Type=0
Dn Type=3
Dn Slope=0.005
Boundary for River Rch & Prof#=UNT033 IN SPCR,Reach-1,7
Up Type=0
Dn Type=3
Dn Slope=0.005

--- UNT033 IN SPCR.g01 (geometry) ---

Geom Title=Existing Conditions

River Reach=UNT033 IN SPCR,Reach-1
Reach XY= 30
      2263515.82     13329841.08      2263629.52     13329292.70
      2263770.24     13328997.96      2263932.39     13328809.43
      2263950.53     13328658.02      2264014.07     13328575.25
      2264019.47     13328474.07      2264134.47     13328275.51
      2264175.94     13328111.34      2264135.74     13327802.67
      2264071.93     13327641.74      2264113.43     13327561.76
      2264099.96     13327342.79      2264186.81     13327166.83
      2264160.42     13326937.02      2264206.13     13326567.18
      2264092.90     13326270.04      2264062.27     13326064.40
      2263759.97     13325635.92      2263680.32     13325410.06
      2263610.75     13325385.98      2263543.33     13325410.75
      2263445.90     13325623.47      2263311.63     13325608.66
      2263205.41     13325512.84      2263153.63     13325404.71
      2262964.90     13325322.04      2262846.75     13325173.54
      2262863.03     13325084.43      2262947.72     13324956.85

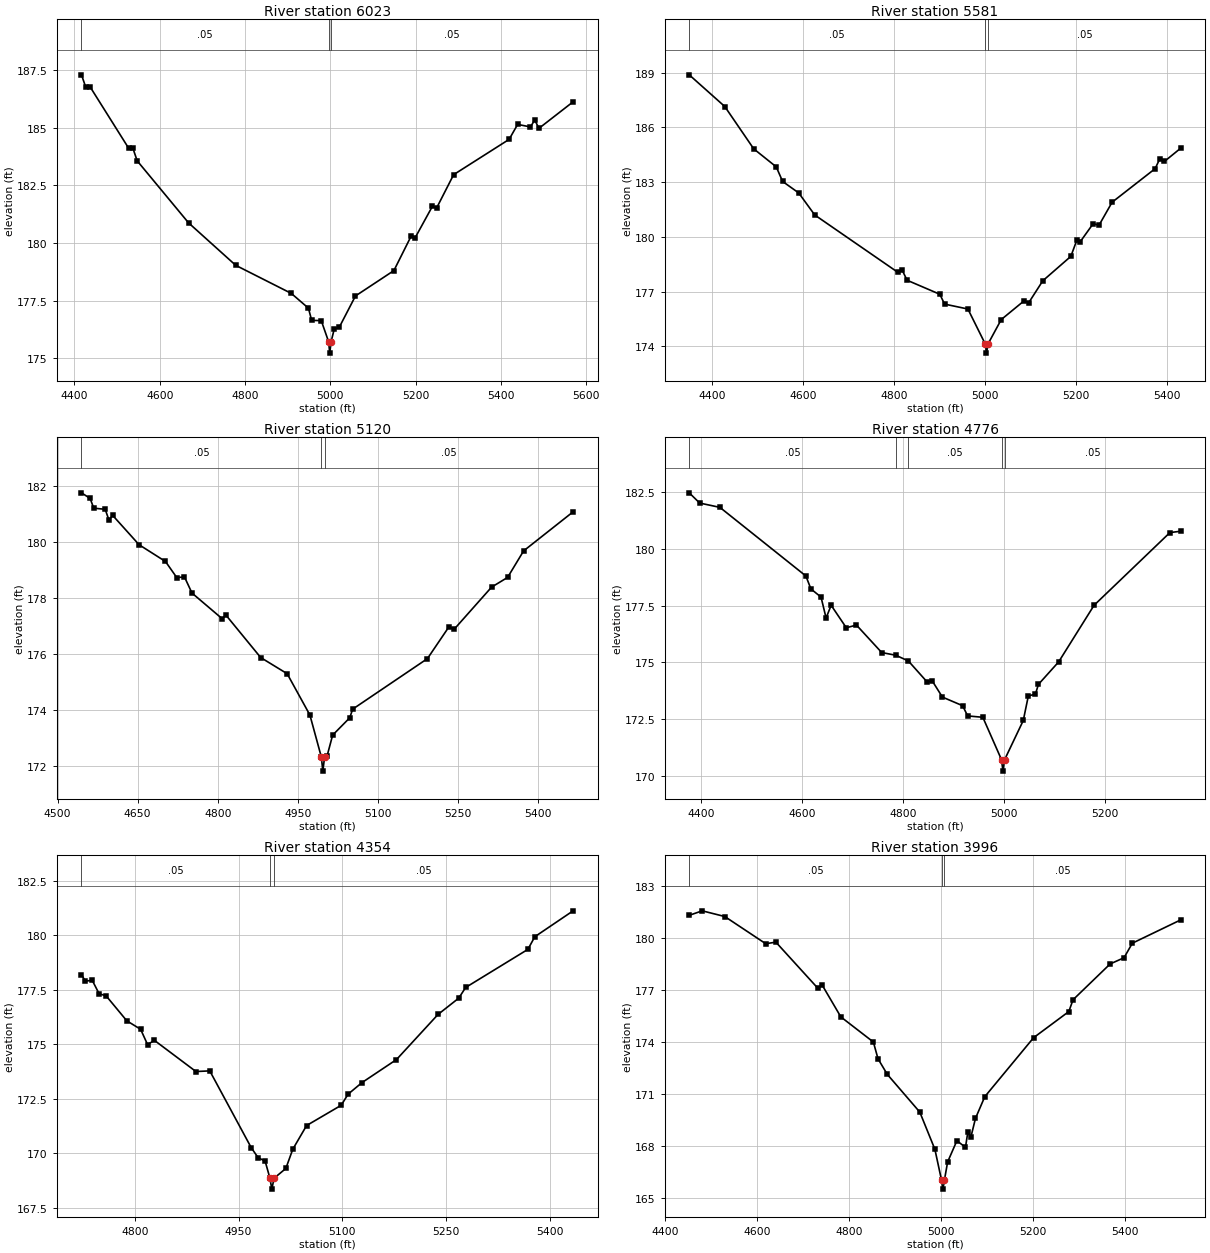
Type RM Length L Ch R = 1,6023,442,442,442
BEGIN DESCRIPTION:
UNT033 IN SPCR 12.0
END DESCRIPTION:
XS GIS Cut Line= 3
      2264137.73     13329646.86      2263537.72     13329596.85
      2262987.71     13329596.85
#Sta/Elev= 30
  4416.7  187.29  4426.7  186.75  4436.8  186.77  4527.1  184.11  4537.1  184.11
  4547.2  183.56  4667.6  180.87  4778.0  179.03  4908.4  177.81  4948.5  177.17
  4956.1  176.64  4978.6  176.63  4995.7  175.72  4998.5  175.22  5001.7  175.72
  5008.8  176.25  5021.3  176.36  5058.8  177.70  5148.8  178.80  5188.8  180.28
  5198.8  180.23  5238.8  181.58  5248.8  181.51  5288.8  182.96  5418.8  184.49
  5438.8  185.14  5468.8  185.03  5478.8  185.33  5488.8  184.97  5568.8  186.12
#Mann=3,-1,0
  4416.7    0.05       0  4995.7   0.035       0  5001.7    0.05       0
Bank Sta=4995.7,5001.7
Exp/Cntr=0.3,0.1

Type RM Length L Ch R = 1,5581,461,461,461
BEGIN DESCRIPTION:
UNT033 IN SPCR 11.0
END DESCRIPTION:
XS GIS Cut Line= 3
      2264215.54     13329539.70      2263908.21     13329242.79
      2263272.76     13329086.53
#Sta/Elev= 30
  4349.2  188.89  4427.5  187.15  4491.1  184.83  4540.7  183.84  4554.7  183.04
  4590.1  182.41  4625.4  181.20  4807.9  178.06  4817.7  178.18  4828.5  177.62
  4900.6  176.85  4911.1  176.31  4962.4  176.04  5000.6  174.12  5003.3  173.62
  5006.6  174.12  5035.7  175.46  5086.0  176.49  5096.3  176.39  5127.2  177.59
  5188.9  178.93  5201.8  179.80  5209.5  179.73  5238.2  180.73  5250.7  180.63
  5279.7  181.90  5374.3  183.74  5384.6  184.28  5394.9  184.14  5430.9  184.87
#Mann=3,-1,0
  4349.2    0.05       0  5000.6   0.035       0  5006.6    0.05       0
Bank Sta=5000.6,5006.6
Exp/Cntr=0.3,0.1

Type RM Length L Ch R = 1,5120,344,344,344
BEGIN DESCRIPTION:
UNT033 IN SPCR 10.0
END DESCRIPTION:
XS GIS Cut Line= 4
      2264291.14     13329076.01      2264065.47     13328859.02
      2263805.05     13328763.53      2263475.15     13328746.17
#Sta/Elev= 30
  4544.8  181.77  4560.9  181.57  4567.8  181.22  4589.2  181.18  4596.1  180.80
  4603.3  180.96  4652.7  179.91  4702.1  179.31  4723.4  178.73  4737.6  178.76
  4751.7  178.18  4808.3  177.26  4815.3  177.39  4880.4  175.87  4930.0  175.29
  4972.6  173.81  4994.1  172.30  4996.8  171.80  5000.1  172.30  5004.6  172.33
  5015.2  173.09  5047.2  173.71  5052.7  174.02  5192.7  175.83  5232.7  176.96
  5242.7  176.88  5312.8  178.39  5342.9  178.74  5372.9  179.69  5465.6  181.09
#Mann=3,-1,0
  4544.8    0.05       0  4994.1   0.035       0  5000.1    0.05       0
Bank Sta=4994.1,5000.1
Exp/Cntr=0.3,0.1

Type RM Length L Ch R = 1,4776,422,422,422
BEGIN DESCRIPTION:
UNT033 IN SPCR 9.0
END DESCRIPTION:
XS GIS Cut Line= 2
      2264638.41     13328485.75      2263666.15     13328494.43
#Sta/Elev= 30
  4377.0  182.46  4397.7  182.01  4437.7  181.82  4607.7  178.80  4617.7  178.23
  4637.7  177.87  4647.7  176.95  4657.7  177.51  4687.7  176.52  4707.7  176.64
  4757.7  175.43  4785.6  175.31  4810.4  175.06  4847.7  174.13  4857.7  174.18
  4877.7  173.47  4917.7  173.09  4927.7  172.64  4957.7  172.58  4994.7  170.71
  4997.5  170.21  5000.7  170.71  5037.7  172.44  5047.7  173.52  5061.7  173.60
  5067.7  174.03  5107.7  175.02  5177.7  177.51  5327.7  180.71  5349.3  180.77
#Mann=5,-1,0
  4377.0    0.05       0  4785.6     0.1       0  4810.4    0.05       0
  4994.7    0.03       0  5000.7    0.05       0
Bank Sta=4994.7,5000.7
Exp/Cntr=0.3,0.1

Type RM Length L Ch R = 1,4354,358,358,358
BEGIN DESCRIPTION:
UNT033 IN SPCR 8.0
END DESCRIPTION:
XS GIS Cut Line= 2
      2264453.19     13328104.38      2263742.31     13328109.85
#Sta/Elev= 30
  4722.8  178.20  4728.3  177.90  4738.3  177.94  4748.3  177.32  4758.3  177.23
  4788.3  176.08  4808.3  175.69  4818.3  174.99  4828.3  175.18  4888.3  173.75
  4908.3  173.78  4968.3  170.25  4978.3  169.79  4988.3  169.64  4995.3  168.85
  4998.0  168.35  5001.3  168.85  5018.3  169.30  5028.3  170.18  5048.3  171.27
  5098.3  172.20  5108.3  172.71  5128.3  173.24  5178.3  174.30  5238.3  176.37
  5268.3  177.12  5278.3  177.61  5368.3  179.36  5378.3  179.94  5433.7  181.13
#Mann=3,-1,0
  4722.8    0.05       0  4995.3    0.03       0  5001.3    0.05       0
Bank Sta=4995.3,5001.3
Exp/Cntr=0.3,0.1

Type RM Length L Ch R = 1,3996,624,624,624
BEGIN DESCRIPTION:
UNT033 IN SPCR 7.0
END DESCRIPTION:
XS GIS Cut Line= 2
      2264664.39     13327678.47      2263605.42     13327826.03
#Sta/Elev= 30
  4452.9  181.33  4481.2  181.59  4530.3  181.26  4619.3  179.69  4641.4  179.78
  4732.2  177.13  4742.3  177.29  4782.7  175.46  4853.4  174.01  4863.5  173.04
  4883.7  172.14  4954.4  169.96  4987.2  167.81  5001.8  166.01  5004.6  165.51
  5007.8  166.01  5014.9  167.08  5035.1  168.31  5053.7  167.92  5058.8  168.80
  5065.4  168.51  5075.5  169.60  5095.7  170.85  5201.9  174.26  5278.5  175.77
  5287.6  176.45  5368.3  178.52  5398.6  178.88  5416.6  179.72  5522.1  181.07
#Mann=3,-1,0
  4452.9    0.05       0  5001.8    0.03       0  5007.8    0.05       0
Bank Sta=5001.8,5007.8
Exp/Cntr=0.3,0.1

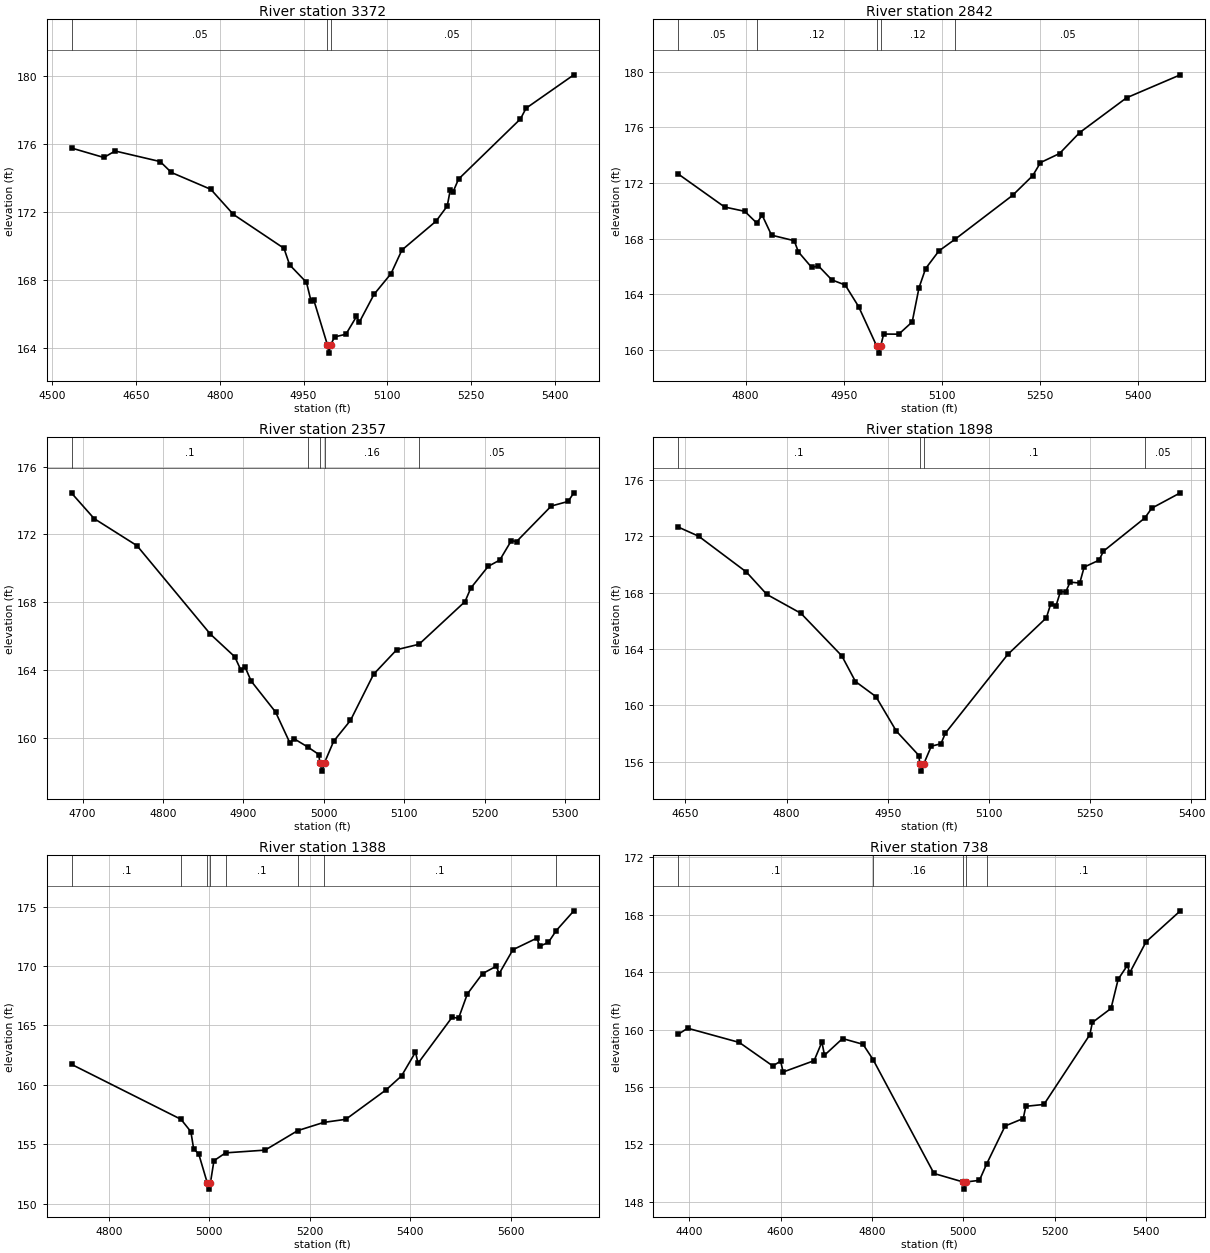
Type RM Length L Ch R = 1,3372,530,530,530
BEGIN DESCRIPTION:
UNT033 IN SPCR 6.0
END DESCRIPTION:
XS GIS Cut Line= 2
      2264644.73     13327234.38      2263752.82     13327124.94
#Sta/Elev= 30
  4535.1  175.74  4592.5  175.19  4612.7  175.57  4693.3  174.95  4713.4  174.31
  4784.0  173.32  4824.3  171.85  4914.9  169.86  4925.0  168.89  4955.2  167.86
  4963.3  166.77  4968.3  166.82  4992.5  164.21  4995.3  163.71  4998.5  164.21
  5005.6  164.66  5025.8  164.82  5044.7  165.86  5049.7  165.52  5076.1  167.16
  5106.4  168.37  5126.0  169.76  5187.0  171.45  5207.1  172.34  5212.4  173.27
  5217.5  173.17  5227.3  173.92  5338.1  177.45  5348.2  178.08  5433.7  180.04
#Mann=3,-1,0
  4535.1    0.05       0  4992.5    0.03       0  4998.5    0.05       0
Bank Sta=4992.5,4998.5
Exp/Cntr=0.3,0.1

Type RM Length L Ch R = 1,2842,485,485,485
BEGIN DESCRIPTION:
UNT033 IN SPCR 5.0
END DESCRIPTION:
XS GIS Cut Line= 2
      2264497.02     13326594.17      2263747.39     13326758.33
#Sta/Elev= 30
  4697.0  172.65  4767.9  170.28  4798.7  169.97  4817.0  169.13  4825.3  169.69
  4839.6  168.26  4874.3  167.86  4880.6  167.06  4901.0  165.94  4911.3  166.05
  4931.7  165.05  4952.2  164.68  4972.7  163.13  5000.4  160.29  5003.1  159.79
  5006.4  160.29  5011.0  161.16  5034.1  161.15  5054.6  162.03  5065.0  164.48
  5075.1  165.86  5095.5  167.13  5120.5  167.98  5208.1  171.12  5238.8  172.53
  5250.7  173.47  5279.8  174.12  5310.5  175.62  5382.2  178.12  5464.4  179.77
#Mann=5,-1,0
  4697.0    0.05       0  4817.0    0.12       0  5000.4    0.07       0
  5006.4    0.12       0  5120.5    0.05       0
Bank Sta=5000.4,5006.4
Exp/Cntr=0.3,0.1

Type RM Length L Ch R = 1,2357,459,459,459
BEGIN DESCRIPTION:
UNT033 IN SPCR 4.0
END DESCRIPTION:
XS GIS Cut Line= 3
      2264387.68     13326146.86      2264087.72     13326196.85
      2263837.68     13326396.88
#Sta/Elev= 30
  4686.6  174.43  4714.4  172.94  4767.7  171.34  4858.9  166.12  4889.3  164.78
  4896.9  163.99  4902.0  164.19  4909.6  163.35  4940.0  161.52  4957.7  159.71
  4962.8  159.95  4980.5  159.44  4993.9  159.01  4994.9  158.53  4997.7  158.03
  5000.9  158.53  5012.3  159.80  5033.1  161.02  5061.9  163.75  5090.7  165.20
  5118.4  165.52  5175.6  168.04  5182.8  168.84  5204.4  170.12  5218.8  170.49
  5233.2  171.64  5239.6  171.58  5282.8  173.68  5303.7  173.95  5310.9  174.46
#Mann=5,-1,0
  4686.6     0.1       0  4980.5    0.16       0  4994.9    0.07       0
  5000.9    0.16       0  5118.4    0.05       0
Bank Sta=4994.9,5000.9
Exp/Cntr=0.3,0.1

Type RM Length L Ch R = 1,1898,510,510,510
BEGIN DESCRIPTION:
UNT033 IN SPCR 3.0
END DESCRIPTION:
XS GIS Cut Line= 3
      2264237.70     13325746.86      2263887.72     13325796.85
      2263637.75     13326096.82
#Sta/Elev= 30
  4639.5  172.65  4669.8  172.00  4740.5  169.46  4770.8  167.87  4821.3  166.53
  4881.9  163.51  4902.1  161.69  4932.4  160.62  4962.7  158.17  4996.3  156.43
  4997.2  155.83  4999.9  155.33  5003.2  155.83  5014.5  157.10  5028.8  157.27
  5035.3  158.02  5127.8  163.61  5185.0  166.21  5191.5  167.20  5199.4  167.08
  5205.9  168.07  5213.7  168.05  5220.2  168.74  5234.5  168.68  5241.0  169.81
  5263.1  170.30  5269.6  170.94  5330.8  173.29  5341.2  173.99  5383.5  175.08
#Mann=4,-1,0
  4639.5     0.1       0  4997.2    0.07       0  5003.2     0.1       0
  5330.8    0.05       0
Bank Sta=4997.2,5003.2
Exp/Cntr=0.3,0.1

Type RM Length L Ch R = 1,1388,650,650,650
BEGIN DESCRIPTION:
UNT033 IN SPCR 2.0
END DESCRIPTION:
XS GIS Cut Line= 4
      2263829.42     13325259.09      2263637.92     13325313.80
      2263594.14     13325625.69      2263533.95     13326107.23
#Sta/Elev= 30
  4726.4  161.72  4943.8  157.11  4963.5  156.07  4969.0  154.62  4979.1  154.20
  4996.3  151.74  4999.1  151.24  5002.3  151.74  5009.4  153.63  5032.6  154.29
  5111.2  154.52  5176.2  156.16  5227.9  156.85  5271.9  157.11  5352.5  159.60
  5382.8  160.76  5410.6  162.76  5415.6  161.82  5483.6  165.70  5496.3  165.60
  5513.8  167.65  5544.0  169.36  5571.8  169.99  5576.9  169.34  5604.5  171.37
  5652.5  172.35  5657.5  171.66  5675.0  171.98  5690.8  172.98  5725.8  174.64
#Mann=8,-1,0
  4726.4     0.1       0  4943.8    0.16       0  4996.3    0.07       0
  5002.3    0.16       0  5032.6     0.1       0  5176.2    0.16       0
  5227.9     0.1       0  5690.8    0.05       0
Bank Sta=4996.3,5002.3
Exp/Cntr=0.3,0.1

Type RM Length L Ch R = 1,738,521,521,521
BEGIN DESCRIPTION:
Mapping XS 572a4e48
END DESCRIPTION:
XS GIS Cut Line= 3
      2263752.20     13325213.36      2263028.21     13325562.33
      2262955.30     13325848.79
#Sta/Elev= 30
  4376.0  159.68  4396.6  160.10  4509.7  159.11  4583.1  157.47  4600.1  157.81
  4605.7  157.05  4673.5  157.84  4690.6  159.14  4696.2  158.22  4735.8  159.38
  4780.6  158.98  4802.5  157.92  4936.0  149.98  4999.6  149.39  5002.4  148.89
  5005.6  149.39  5035.4  149.50  5051.4  150.65  5091.7  153.29  5131.4  153.81
  5137.0  154.66  5176.7  154.79  5277.2  159.65  5282.7  160.50  5323.6  161.48
  5339.2  163.51  5359.4  164.48  5364.5  163.96  5400.3  166.12  5475.3  168.28
#Mann=5,-1,0
  4376.0     0.1       0  4802.5    0.16       0  4999.6    0.07       0
  5005.6    0.16       0  5051.4     0.1       0
Bank Sta=4999.6,5005.6
Exp/Cntr=0.3,0.1

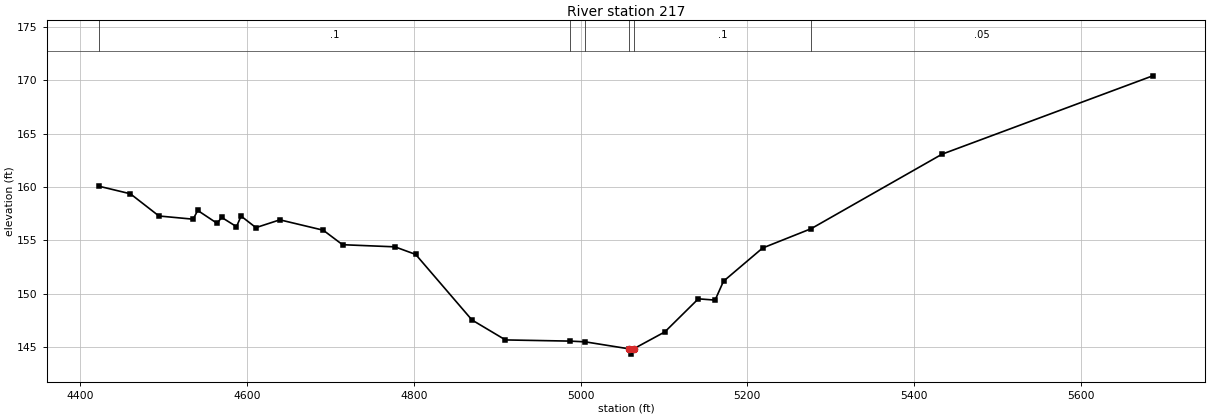
Type RM Length L Ch R = 1,217,0,0,0
BEGIN DESCRIPTION:
UNT033 IN SPCR 1.0
END DESCRIPTION:
XS GIS Cut Line= 4
      2263391.70     13325319.28      2263046.97     13325166.06
      2262581.88     13325116.82      2262302.85     13325428.68
#Sta/Elev= 30
  4422.9  160.06  4460.1  159.36  4494.4  157.28  4535.4  156.98  4540.9  157.80
  4564.2  156.59  4569.6  157.15  4587.4  156.28  4592.9  157.27  4610.7  156.19
  4639.4  156.92  4691.4  155.95  4714.6  154.59  4777.4  154.39  4802.3  153.68
  4869.8  147.54  4910.0  145.67  4987.4  145.56  5005.7  145.49  5057.8  144.84
  5060.6  144.34  5063.8  144.84  5101.1  146.42  5141.3  149.52  5161.4  149.40
  5171.5  151.17  5218.4  154.28  5276.6  156.09  5433.6  163.07  5686.3  170.41
#Mann=6,-1,0
  4422.9     0.1       0  4987.4    0.05       0  5005.7     0.1       0
  5057.8   0.035       0  5063.8     0.1       0  5276.6    0.05       0
Bank Sta=5057.8,5063.8
Exp/Cntr=0.3,0.1

Chan Stop Cuts=-1