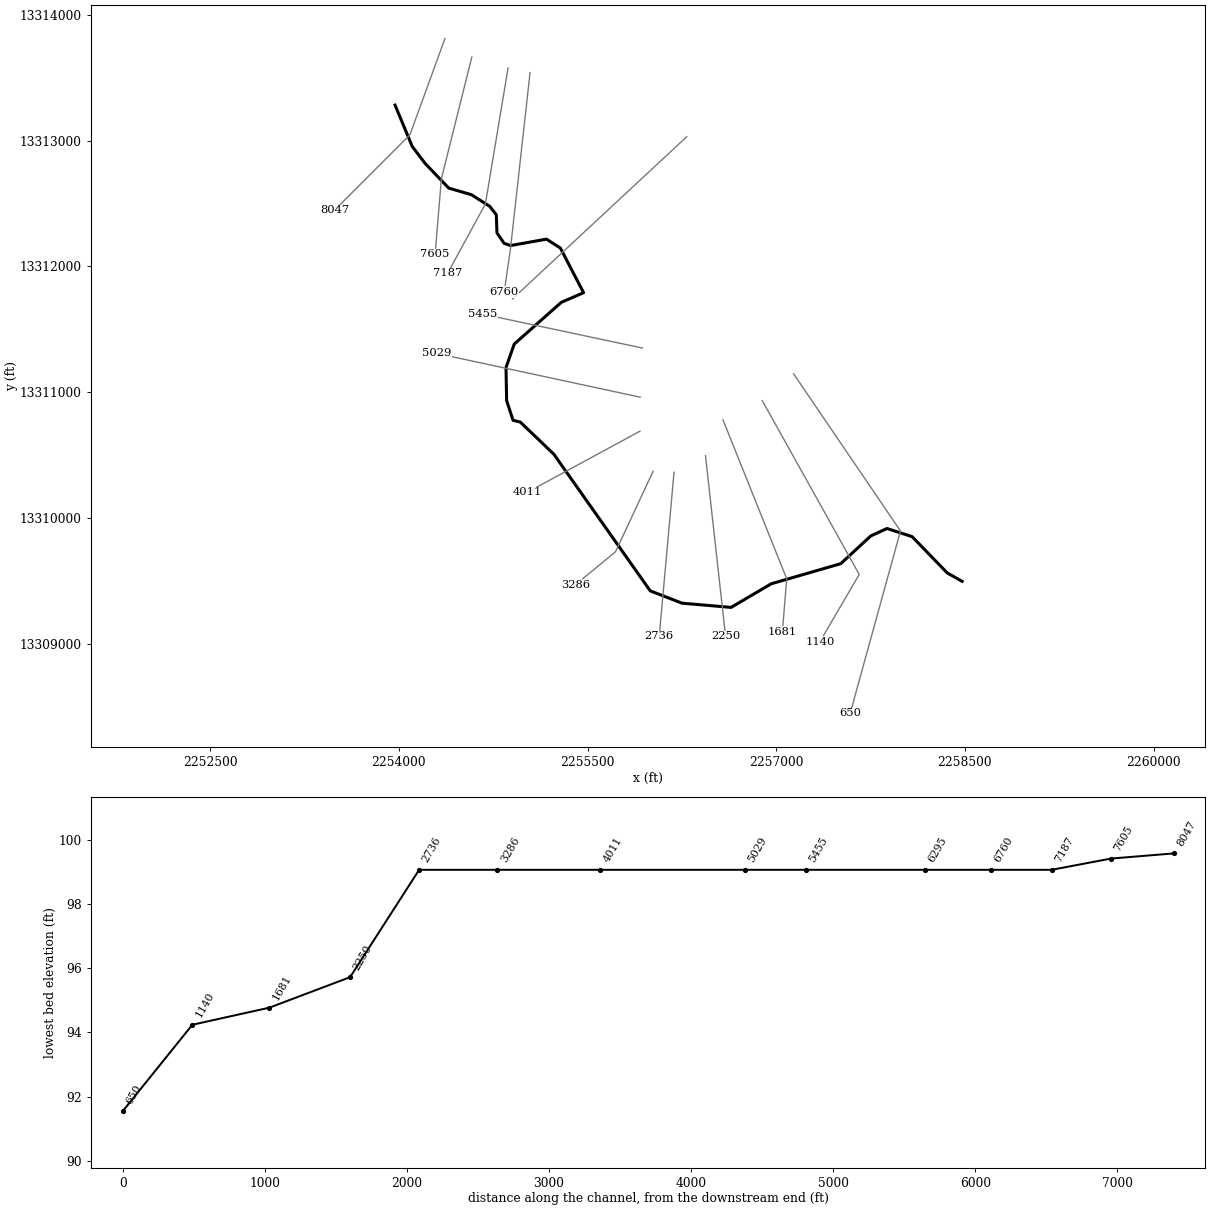
--- UNT034 IN SPCR.prj (project) ---

Proj Title=UNT034 IN SPCR Base Level Engineering
Current Plan=p01
Default Exp/Contr=0.3,0.1
English Units
Geom File=g01
Flow File=f01
Plan File=p01
BEGIN DESCRIPTION:
UNT034 IN SPCR
END DESCRIPTION:

--- UNT034 IN SPCR.p01 (plan) ---

Plan Title=Multiple Run
Short Identifier=Multiple
Geom File=g01
Flow File=f01
Subcritical Flow
K Sum by GR= 0
Std Step Tol= 0.01
Critical Tol= 0.01
Num of Std Step Trials= 20
Max Error Tol= 0.3
Flow Tol Ratio= 0.001
Split Flow NTrial= 30
Split Flow Tol= 0.02
Split Flow Ratio= 0.02
Log Output Level= 0
Friction Slope Method= 1
Unsteady Friction Slope Method= 2
Unsteady Bridges Friction Slope Method= 1
Parabolic Critical Depth
Global Vel Dist=  1 , 1 , 1
Global Log Level= 0
CheckData=True
Encroach Param= -1, 0, 0, 0
BEGIN DESCRIPTION:
Multiple Run
END DESCRIPTION:

--- UNT034 IN SPCR.f01 (steady flow) ---

Flow Title=Multiple
Number of Profiles=7
Profile Names=10-year,25-year,50-year,1pct_min,100-year,1pct_plu,500-year
River Rch & RM= UNT034 IN SPCR,Reach-1,8047
     905    1326    1694    1585    2144    2899    3488
Boundary for River Rch & Prof#=UNT034 IN SPCR,Reach-1,1
Up Type=0
Dn Type=3
Dn Slope=0.005
Boundary for River Rch & Prof#=UNT034 IN SPCR,Reach-1,2
Up Type=0
Dn Type=3
Dn Slope=0.005
Boundary for River Rch & Prof#=UNT034 IN SPCR,Reach-1,3
Up Type=0
Dn Type=3
Dn Slope=0.005
Boundary for River Rch & Prof#=UNT034 IN SPCR,Reach-1,4
Up Type=0
Dn Type=3
Dn Slope=0.005
Boundary for River Rch & Prof#=UNT034 IN SPCR,Reach-1,5
Up Type=0
Dn Type=3
Dn Slope=0.005
Boundary for River Rch & Prof#=UNT034 IN SPCR,Reach-1,6
Up Type=0
Dn Type=3
Dn Slope=0.005
Boundary for River Rch & Prof#=UNT034 IN SPCR,Reach-1,7
Up Type=0
Dn Type=3
Dn Slope=0.005

--- UNT034 IN SPCR.g01 (geometry) ---

Geom Title=Existing Conditions

River Reach=UNT034 IN SPCR,Reach-1
Reach XY= 30
      2253969.34     13313282.92      2254105.97     13312954.21
      2254209.06     13312818.48      2254396.33     13312622.83
      2254575.80     13312570.99      2254722.50     13312477.68
      2254774.15     13312411.27      2254779.80     13312266.74
      2254835.79     13312184.71      2254887.00     13312166.04
      2255173.03     13312217.26      2255283.70     13312146.51
      2255468.22     13311791.59      2255291.12     13311714.78
      2254916.98     13311383.07      2254851.41     13311196.64
      2254856.55     13310933.07      2254907.72     13310776.85
      2254965.01     13310763.05      2255231.67     13310507.61
      2255997.99     13309421.30      2256250.62     13309323.06
      2256640.79     13309289.37      2256960.79     13309477.44
      2257512.68     13309636.95      2257751.41     13309857.45
      2257880.41     13309916.80      2258080.34     13309851.79
      2258359.65     13309563.25      2258477.72     13309496.85

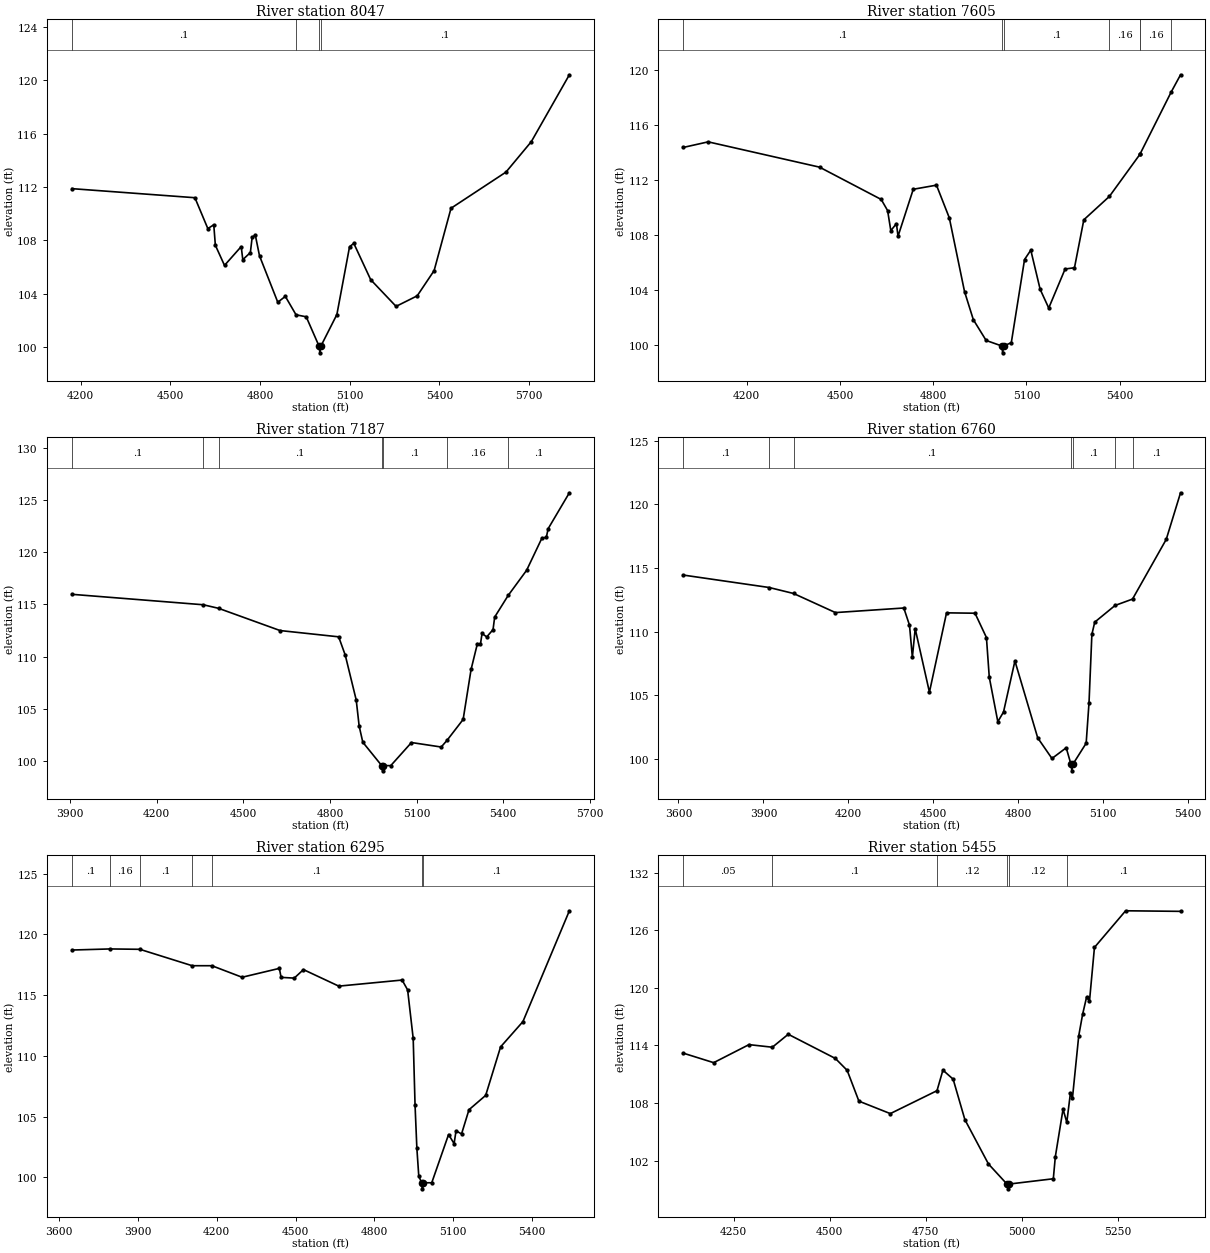
Type RM Length L Ch R = 1,8047,442,442,442
BEGIN DESCRIPTION:
UNT034 IN SPCR 10.0
END DESCRIPTION:
XS GIS Cut Line= 3
      2254366.58     13313813.72      2254087.72     13313046.85
      2253487.74     13312446.87
#Sta/Elev= 30
  4170.2  111.87  4581.9  111.19  4625.1  108.88  4645.0  109.16  4650.3  107.63
  4680.9  106.12  4736.8  107.53  4742.1  106.55  4767.4  107.08  4773.4  108.22
  4784.0  108.39  4798.0  106.84  4859.2  103.36  4884.4  103.80  4920.2  102.42
  4954.3  102.27  4997.3  100.07  5000.1   99.57  5003.3  100.07  5056.9  102.44
  5099.3  107.52  5113.5  107.77  5170.0  105.05  5254.9  103.05  5325.6  103.84
  5382.2  105.73  5438.7  110.40  5622.6  113.11  5707.4  115.39  5834.7  120.40
#Mann=4,-1,0
  4170.2     0.1       0  4920.2    0.16       0  4997.3    0.07       0
  5003.3     0.1       0
Bank Sta=4997.3,5003.3
Exp/Cntr=0.3,0.1

Type RM Length L Ch R = 1,7605,418,418,418
BEGIN DESCRIPTION:
UNT034 IN SPCR 9.0
END DESCRIPTION:
XS GIS Cut Line= 3
      2254579.84     13313665.35      2254337.72     13312696.85
      2254287.72     13312096.83
#Sta/Elev= 30
  3995.3  114.35  4076.2  114.76  4434.4  112.92  4632.8  110.57  4653.4  109.76
  4663.7  108.30  4681.8  108.81  4686.9  107.89  4735.9  111.31  4810.6  111.61
  4851.9  109.23  4900.8  103.87  4929.2  101.82  4970.4  100.31  5020.7   99.91
  5023.5   99.41  5026.7   99.91  5051.3  100.15  5093.9  106.20  5114.0  106.88
  5144.1  104.03  5171.7  102.67  5224.4  105.51  5254.5  105.60  5284.6  109.09
  5366.8  110.79  5465.3  113.86  5466.2  113.91  5565.5  118.38  5595.7  119.64
#Mann=7,-1,0
  3995.3     0.1       0  5020.7    0.07       0  5026.7     0.1       0
  5366.8    0.16       0  5465.3     0.1       0  5466.2    0.16       0
  5565.5     0.1       0
Bank Sta=5020.7,5026.7
Exp/Cntr=0.3,0.1

Type RM Length L Ch R = 1,7187,427,427,427
BEGIN DESCRIPTION:
UNT034 IN SPCR 8.0
END DESCRIPTION:
XS GIS Cut Line= 3
      2254867.92     13313578.08      2254687.72     13312496.85
      2254387.74     13311946.89
#Sta/Elev= 30
  3906.3  115.96  4361.2  114.96  4414.1  114.62  4627.3  112.49  4830.1  111.89
  4852.9  110.14  4890.9  105.84  4901.1  103.34  4913.7  101.80  4979.2   99.56
  4981.9   99.06  4985.2   99.56  5010.5   99.56  5082.2  101.77  5185.2  101.34
  5205.6  101.99  5261.1  103.98  5288.6  108.77  5310.5  111.24  5320.9  111.17
  5326.6  112.21  5342.7  111.88  5364.6  112.58  5370.3  113.78  5417.0  115.85
  5480.9  118.26  5533.5  121.32  5549.2  121.42  5555.4  122.24  5628.9  125.68
#Mann=7,-1,0
  3906.3     0.1       0  4361.2    0.16       0  4414.1     0.1       0
  4979.2    0.07       0  4985.2     0.1       0  5205.6    0.16       0
  5417.0     0.1       0
Bank Sta=4979.2,4985.2
Exp/Cntr=0.3,0.1

Type RM Length L Ch R = 1,6760,465,465,465
BEGIN DESCRIPTION:
UNT034 IN SPCR 7.0
END DESCRIPTION:
XS GIS Cut Line= 3
      2255042.71     13313541.76      2254887.72     13312146.85
      2254837.73     13311796.90
#Sta/Elev= 30
  3616.1  114.44  3920.3  113.46  4006.5  112.99  4154.3  111.49  4395.8  111.85
  4415.9  110.50  4426.0  107.98  4436.0  110.22  4486.3  105.24  4546.7  111.47
  4647.3  111.44  4687.6  109.53  4697.6  106.42  4727.8  102.92  4747.9  103.68
  4788.2  107.69  4868.7  101.65  4919.0  100.03  4969.3  100.87  4986.4   99.56
  4989.2   99.06  4992.4   99.56  5039.8  101.23  5049.9  104.42  5060.0  109.78
  5070.1  110.74  5141.9  112.05  5203.5  112.55  5322.6  117.24  5373.1  120.90
#Mann=7,-1,0
  3616.1     0.1       0  3920.3    0.16       0  4006.5     0.1       0
  4986.4    0.07       0  4992.4     0.1       0  5141.9    0.16       0
  5203.5     0.1       0
Bank Sta=4986.4,4992.4
Exp/Cntr=0.3,0.1

Type RM Length L Ch R = 1,6295,840,840,840
BEGIN DESCRIPTION:
UNT034 IN SPCR 6.0
END DESCRIPTION:
XS GIS Cut Line= 2
      2256288.43     13313031.64      2254902.74     13311742.10
#Sta/Elev= 30
  3648.6  118.71  3793.5  118.80  3907.2  118.77  4106.3  117.42  4181.3  117.42
  4296.3  116.47  4438.0  117.20  4444.8  116.46  4494.7  116.40  4529.8  117.10
  4664.2  115.74  4905.1  116.24  4926.1  115.43  4947.3  111.44  4954.4  105.93
  4961.3  102.39  4968.6  100.09  4979.8   99.56  4982.5   99.06  4985.8   99.56
  5017.9   99.56  5081.9  103.53  5102.9  102.78  5110.3  103.83  5131.3  103.58
  5159.6  105.57  5223.1  106.75  5279.8  110.74  5364.8  112.82  5541.5  121.94
#Mann=7,-1,0
  3648.6     0.1       0  3793.5    0.16       0  3907.2     0.1       0
  4106.3    0.16       0  4181.3     0.1       0  4979.8    0.07       0
  4985.8     0.1       0
Bank Sta=4979.8,4985.8
Exp/Cntr=0.3,0.1

Type RM Length L Ch R = 1,5455,426,426,426
BEGIN DESCRIPTION:
Mapping XS de665a86
END DESCRIPTION:
XS GIS Cut Line= 2
      2255935.75     13311351.50      2254668.40     13311620.60
#Sta/Elev= 30
  4118.5  113.21  4198.3  112.21  4290.3  114.09  4351.1  113.82  4392.5  115.17
  4515.2  112.65  4545.9  111.41  4576.5  108.20  4658.3  106.90  4779.9  109.29
  4795.3  111.43  4821.9  110.49  4852.5  106.27  4913.9  101.65  4962.0   99.56
  4964.7   99.06  4968.0   99.56  5082.8  100.11  5088.0  102.40  5108.1  107.36
  5117.9  106.00  5127.4  109.06  5132.5  108.48  5149.0  115.02  5159.2  117.27
  5169.4  119.04  5177.0  118.63  5189.9  124.22  5271.1  128.04  5414.1  127.98
#Mann=6,-1,0
  4118.5    0.05       0  4351.1     0.1       0  4779.9    0.12       0
  4962.0    0.07       0  4968.0    0.12       0  5117.9     0.1       0
Bank Sta=4962,4968
Exp/Cntr=0.3,0.1

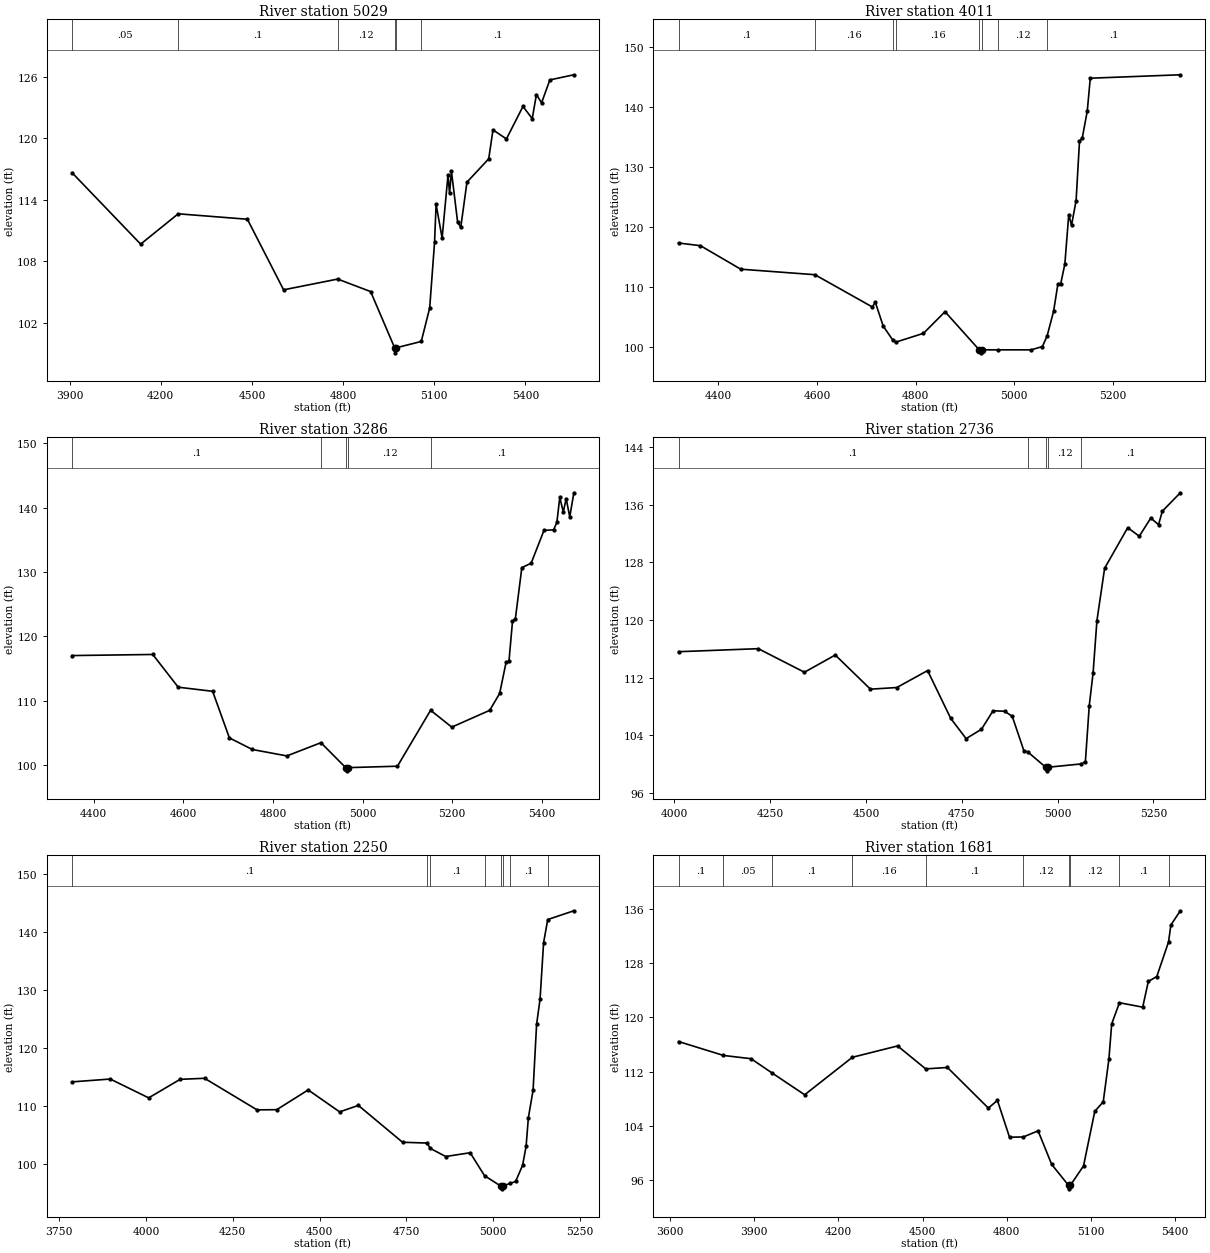
Type RM Length L Ch R = 1,5029,1018,1018,1018
BEGIN DESCRIPTION:
Mapping XS d871f7f9
END DESCRIPTION:
XS GIS Cut Line= 2
      2255918.40     13310960.88      2254303.81     13311308.10
#Sta/Elev= 30
  3908.2  116.64  4133.9  109.67  4257.5  112.63  4485.2  112.10  4604.4  105.21
  4782.3  106.26  4890.8  105.04  4969.7   99.56  4972.4   99.06  4975.7   99.56
  5057.5  100.17  5085.2  103.44  5101.2  109.84  5106.3  113.55  5126.1  110.26
  5145.5  116.42  5150.6  114.63  5156.8  116.77  5177.2  111.80  5187.5  111.32
  5207.9  115.72  5279.5  118.00  5293.5  120.82  5337.8  119.94  5392.2  123.11
  5422.7  121.92  5436.5  124.27  5453.4  123.46  5480.7  125.70  5559.7  126.20
#Mann=6,-1,0
  3908.2    0.05       0  4257.5     0.1       0  4782.3    0.12       0
  4969.7    0.07       0  4975.7    0.12       0  5057.5     0.1       0
Bank Sta=4969.7,4975.7
Exp/Cntr=0.3,0.1

Type RM Length L Ch R = 1,4011,725,725,725
BEGIN DESCRIPTION:
Mapping XS f3c22dfa
END DESCRIPTION:
XS GIS Cut Line= 2
      2255916.63     13310690.46      2255021.79     13310204.89
#Sta/Elev= 30
  4319.0  117.35  4363.5  116.90  4445.2  112.99  4595.7  112.07  4712.4  106.69
  4718.1  107.53  4734.2  103.53  4753.3  101.23  4760.1  100.85  4816.0  102.31
  4859.7  105.91  4929.1   99.56  4931.9   99.06  4935.1   99.56  4967.1   99.56
  5034.6   99.56  5057.3  100.11  5066.9  101.89  5080.0  106.00  5088.8  110.57
  5094.5  110.60  5102.8  113.83  5110.7  122.09  5116.3  120.30  5125.6  124.38
  5132.5  134.27  5138.2  134.87  5148.3  139.32  5154.4  144.79  5337.1  145.36
#Mann=8,-1,0
  4319.0     0.1       0  4595.7    0.16       0  4753.3     0.1       0
  4760.1    0.16       0  4929.1    0.07       0  4935.1    0.16       0
  4967.1    0.12       0  5066.9     0.1       0
Bank Sta=4929.1,4935.1
Exp/Cntr=0.3,0.1

Type RM Length L Ch R = 1,3286,550,550,550
BEGIN DESCRIPTION:
Mapping XS 19ce6ca6
END DESCRIPTION:
XS GIS Cut Line= 3
      2256020.81     13310371.00      2255722.21     13309732.14
      2255402.79     13309468.28
#Sta/Elev= 30
  4352.0  116.99  4532.0  117.16  4588.8  112.07  4665.6  111.43  4703.0  104.18
  4754.2  102.38  4831.2  101.38  4907.2  103.44  4962.4   99.56  4965.1   99.06
  4968.4   99.56  5077.9   99.78  5151.9  108.48  5199.1  105.86  5283.7  108.47
  5305.9  111.09  5320.3  115.94  5326.7  116.09  5334.6  122.29  5341.1  122.75
  5355.4  130.66  5376.2  131.36  5404.9  136.47  5426.2  136.54  5433.6  137.71
  5440.1  141.60  5447.9  139.32  5454.4  141.40  5462.3  138.55  5471.5  142.31
#Mann=5,-1,0
  4352.0     0.1       0  4907.2    0.12       0  4962.4    0.07       0
  4968.4    0.12       0  5151.9     0.1       0
Bank Sta=4962.4,4968.4
Exp/Cntr=0.3,0.1

Type RM Length L Ch R = 1,2736,486,486,486
BEGIN DESCRIPTION:
UNT034 IN SPCR 5.0
END DESCRIPTION:
XS GIS Cut Line= 2
      2256187.49     13310364.06      2256069.58     13309060.18
#Sta/Elev= 30
  4011.1  115.59  4219.2  116.01  4339.6  112.74  4420.0  115.13  4511.8  110.39
  4580.6  110.62  4660.9  112.97  4721.2  106.34  4761.4  103.53  4801.5  104.83
  4831.6  107.39  4861.8  107.33  4881.8  106.62  4912.0  101.87  4922.1  101.69
  4969.2   99.56  4972.0   99.06  4975.2   99.56  5061.9  100.02  5072.6  100.33
  5082.7  108.11  5092.7  112.64  5102.7  119.90  5122.8  127.17  5183.1  132.80
  5213.2  131.61  5243.3  134.14  5263.4  133.21  5273.4  135.09  5320.3  137.64
#Mann=5,-1,0
  4011.1     0.1       0  4922.1    0.12       0  4969.2    0.07       0
  4975.2    0.12       0  5061.9     0.1       0
Bank Sta=4969.2,4975.2
Exp/Cntr=0.3,0.1

Type RM Length L Ch R = 1,2250,569,569,569
BEGIN DESCRIPTION:
UNT034 IN SPCR 4.0
END DESCRIPTION:
XS GIS Cut Line= 2
      2256437.49     13310496.06      2256597.03     13309060.20
#Sta/Elev= 30
  3787.4  114.18  3897.3  114.67  4008.0  111.42  4098.5  114.62  4168.9  114.80
  4319.9  109.35  4376.7  109.38  4467.2  112.79  4557.8  109.00  4611.6  110.12
  4738.9  103.76  4810.0  103.62  4818.1  102.72  4863.2  101.30  4933.6  101.95
  4974.9   97.99  5021.2   96.22  5023.9   95.72  5027.2   96.22  5049.6   96.67
  5064.4   97.00  5084.5   99.78  5094.6  103.06  5101.1  107.99  5114.7  112.74
  5124.8  124.10  5134.8  128.46  5144.9  138.17  5156.9  142.20  5232.1  143.71
#Mann=8,-1,0
  3787.4     0.1       0  4810.0    0.12       0  4818.1     0.1       0
  4974.9    0.12       0  5021.2    0.07       0  5027.2    0.12       0
  5049.6     0.1       0  5156.9    0.12       0
Bank Sta=5021.2,5027.2
Exp/Cntr=0.3,0.1

Type RM Length L Ch R = 1,1681,541,541,541
BEGIN DESCRIPTION:
UNT034 IN SPCR 3.0
END DESCRIPTION:
XS GIS Cut Line= 3
      2256576.37     13310780.79      2257083.32     13309516.87
      2257048.60     13309093.29
#Sta/Elev= 30
  3631.2  116.46  3791.3  114.41  3889.3  113.93  3963.5  111.85  4080.3  108.62
  4250.2  114.14  4411.2  115.81  4511.4  112.43  4588.7  112.64  4734.4  106.66
  4766.7  107.79  4809.8  102.37  4859.1  102.41  4911.5  103.31  4959.9   98.37
  5020.1   95.27  5022.9   94.77  5026.1   95.27  5073.3   98.14  5113.4  106.18
  5143.5  107.58  5163.6  113.85  5173.6  119.05  5201.2  122.17  5284.0  121.52
  5304.1  125.31  5334.2  126.03  5376.1  131.13  5384.3  133.61  5418.0  135.71
#Mann=10,-1,0
  3631.2     0.1       0  3791.3    0.05       0  3963.5     0.1       0
  4250.2    0.16       0  4511.4     0.1       0  4859.1    0.12       0
  5020.1    0.07       0  5026.1    0.12       0  5201.2     0.1       0
  5376.1    0.05       0
Bank Sta=5020.1,5026.1
Exp/Cntr=0.3,0.1

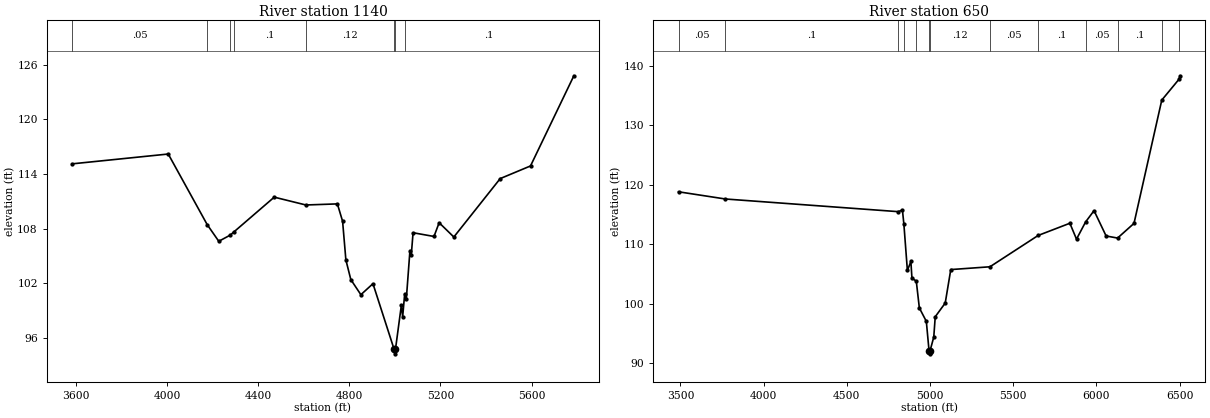
Type RM Length L Ch R = 1,1140,490,490,490
BEGIN DESCRIPTION:
UNT034 IN SPCR 2.0
END DESCRIPTION:
XS GIS Cut Line= 3
      2256888.88     13310933.53      2257659.71     13309551.59
      2257347.22     13309016.89
#Sta/Elev= 30
  3583.6  115.12  4005.6  116.20  4176.3  108.45  4227.3  106.61  4277.7  107.29
  4292.7  107.62  4470.7  111.46  4609.5  110.60  4747.7  110.72  4770.6  108.81
  4785.0  104.56  4806.7  102.40  4850.8  100.74  4903.8  101.95  4996.6   94.74
  4999.4   94.24  5002.6   94.74  5028.4   99.58  5034.1   98.31  5043.1  100.85
  5050.1  100.23  5066.1  105.59  5071.8  105.05  5079.8  107.55  5171.6  107.14
  5194.2  108.65  5258.7  107.08  5462.1  113.50  5595.1  114.89  5785.3  124.80
#Mann=8,-1,0
  3583.6    0.05       0  4176.3     0.1       0  4277.7    0.16       0
  4292.7     0.1       0  4609.5    0.12       0  4996.6    0.07       0
  5002.6    0.12       0  5043.1     0.1       0
Bank Sta=4996.6,5002.6
Exp/Cntr=0.3,0.1

Type RM Length L Ch R = 1,650,0,0,0
BEGIN DESCRIPTION:
UNT034 IN SPCR 1.0
END DESCRIPTION:
XS GIS Cut Line= 3
      2257137.69     13311146.90      2257987.72     13309896.85
      2257587.73     13308446.89
#Sta/Elev= 30
  3488.8  118.80  3770.3  117.59  4809.1  115.46  4834.4  115.73  4843.1  113.38
  4864.2  105.57  4885.2  107.08  4891.6  104.27  4917.7  103.78  4936.1   99.27
  4978.1   97.01  4994.4   92.05  4997.2   91.55  5000.4   92.05  5022.8   94.38
  5031.6   97.79  5091.6  100.09  5125.0  105.72  5360.4  106.19  5650.3  111.46
  5840.7  113.51  5880.6  110.84  5935.3  113.73  5986.0  115.63  6058.6  111.37
  6127.4  111.02  6226.2  113.49  6393.1  134.22  6495.6  137.69  6504.6  138.31
#Mann=13,-1,0
  3488.8    0.05       0  3770.3     0.1       0  4809.1    0.12       0
  4843.1    0.05       0  4917.7    0.12       0  4994.4    0.07       0
  5000.4    0.12       0  5360.4    0.05       0  5650.3     0.1       0
  5935.3    0.05       0  6127.4     0.1       0  6393.1    0.16       0
  6495.6     0.1       0
Bank Sta=4994.4,5000.4
Exp/Cntr=0.3,0.1

Chan Stop Cuts=-1