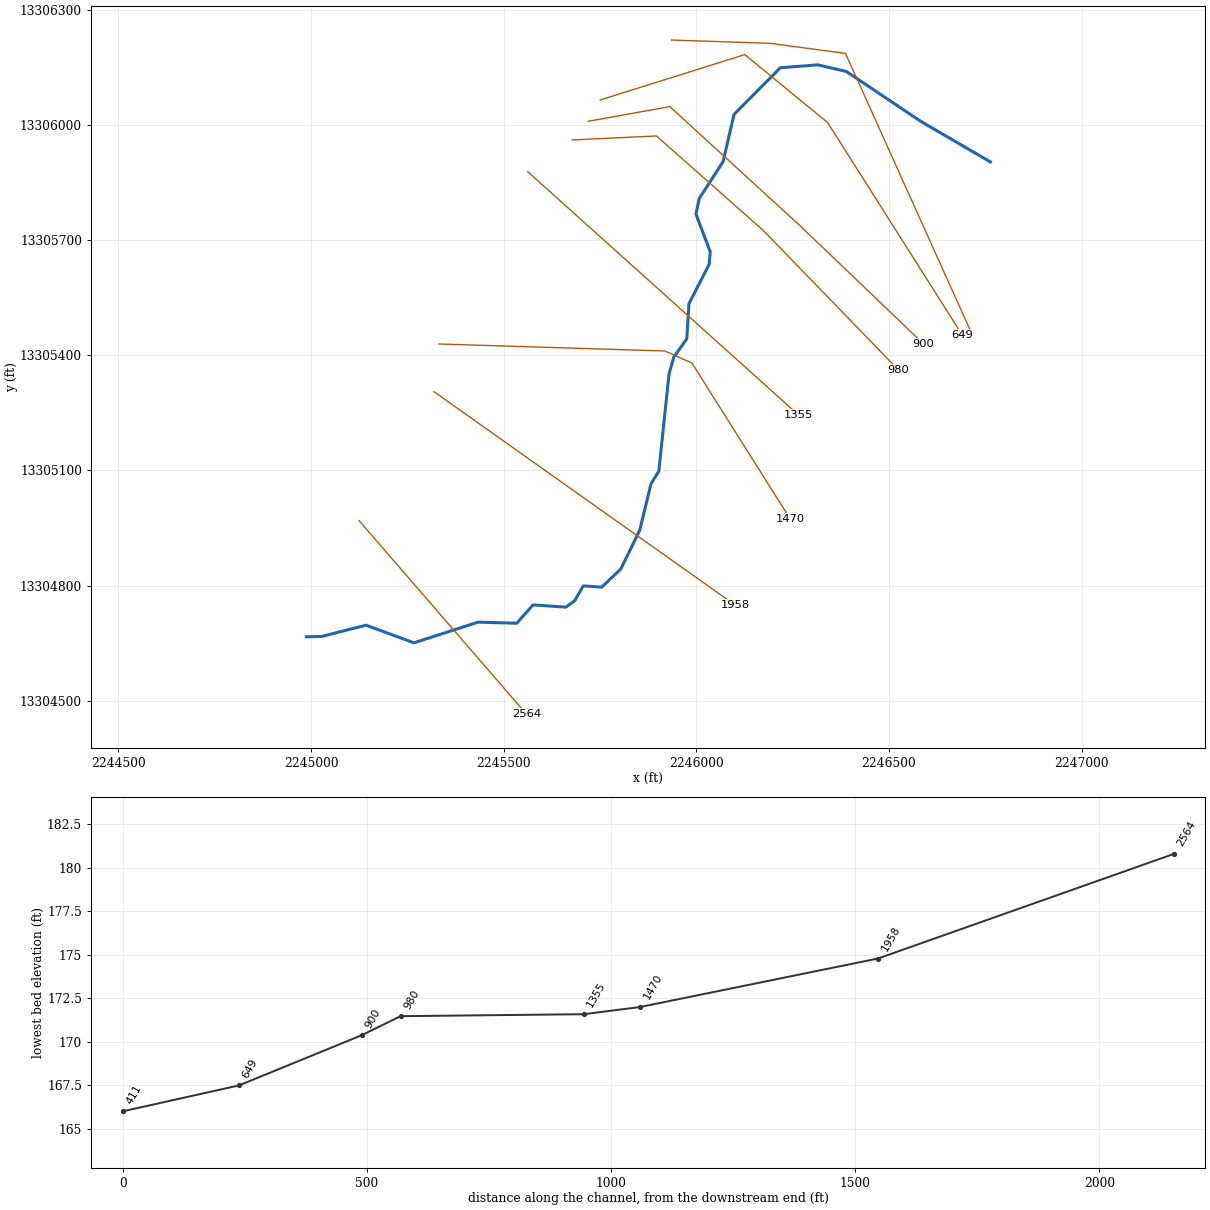
--- UNT035 IN SPCR.prj (project) ---

Proj Title=UNT035 IN SPCR Base Level Engineering
Current Plan=p01
Default Exp/Contr=0.3,0.1
English Units
Geom File=g01
Flow File=f01
Plan File=p01
Y Axis Title=Elevation
X Axis Title(PF)=Main Channel Distance
X Axis Title(XS)=Station
BEGIN DESCRIPTION:
UNT035 IN SPCR
END DESCRIPTION:
DSS Export Rating Curves= 0
DSS Export Rating Curve Sorted= 0
DSS Export Volume Flow Curves= 0
DXF OffsetX= 0
DXF OffsetY= 0
DXF ScaleX= 1
DXF ScaleY= 10

--- UNT035 IN SPCR.p01 (plan) ---

Plan Title=Multiple Run
Short Identifier=Multiple
Geom File=g01
Flow File=f01
Subcritical Flow
K Sum by GR= 0
Std Step Tol= 0.01
Critical Tol= 0.01
Num of Std Step Trials= 20
Max Error Tol= 0.3
Flow Tol Ratio= 0.001
Split Flow NTrial= 30
Split Flow Tol= 0.02
Split Flow Ratio= 0.02
Log Output Level= 0
Friction Slope Method= 1
Unsteady Friction Slope Method= 2
Unsteady Bridges Friction Slope Method= 1
Parabolic Critical Depth
Global Vel Dist=  1 , 1 , 1
Global Log Level= 0
CheckData=True
Encroach Param= -1, 0, 0, 0
BEGIN DESCRIPTION:
Multiple Run
END DESCRIPTION:

--- UNT035 IN SPCR.f01 (steady flow) ---

Flow Title=Multiple
Program Version=4.10
Number of Profiles= 7
Profile Names=10-year,25-year,50-year,1pct_min,100-year,1pct_plu,500-year
River Rch & RM=UNT035 IN SPCR,Reach-1         ,2564
     224     311     383     347     470     635     717
River Rch & RM=UNT035 IN SPCR,Reach-1         ,411
     224     311     383     347     470     635     717
Boundary for River Rch & Prof#=UNT035 IN SPCR,Reach-1         , 1
Up Type= 0
Dn Type= 3
Dn Slope=0.008
Boundary for River Rch & Prof#=UNT035 IN SPCR,Reach-1         , 2
Up Type= 0
Dn Type= 3
Dn Slope=0.008
Boundary for River Rch & Prof#=UNT035 IN SPCR,Reach-1         , 3
Up Type= 0
Dn Type= 3
Dn Slope=0.008
Boundary for River Rch & Prof#=UNT035 IN SPCR,Reach-1         , 4
Up Type= 0
Dn Type= 3
Dn Slope=0.008
Boundary for River Rch & Prof#=UNT035 IN SPCR,Reach-1         , 5
Up Type= 0
Dn Type= 3
Dn Slope=0.008
Boundary for River Rch & Prof#=UNT035 IN SPCR,Reach-1         , 6
Up Type= 0
Dn Type= 3
Dn Slope=0.008
Boundary for River Rch & Prof#=UNT035 IN SPCR,Reach-1         , 7
Up Type= 0
Dn Type= 3
Dn Slope=0.008
DSS Import GetInterval= 0
DSS Import GetPeak= 0
DSS Import FillOption= 0

--- UNT035 IN SPCR.g01 (geometry) ---

Geom Title=Existing Conditions
Program Version=4.10

River Reach=UNT035 IN SPCR  ,Reach-1
Reach XY= 30
      2244987.72     13304666.86      2245027.35     13304667.63
      2245142.76     13304697.07      2245267.13     13304651.18
      2245433.55     13304704.91      2245534.03     13304702.18
      2245576.18     13304749.86      2245661.19     13304744.03
      2245683.99     13304760.37      2245706.69     13304799.42
      2245754.34     13304795.99      2245804.06     13304843.38
      2245853.06     13304944.19      2245882.46      13305065.3
      2245902.59     13305097.79      2245929.16     13305351.19
      2245941.66     13305395.21      2245975.24     13305442.64
      2245980.96     13305534.25      2246033.31     13305636.69
      2246036.08     13305669.33      2245999.07     13305767.65
      2246007.61     13305808.22      2246069.42     13305904.05
      2246097.89     13306026.97      2246218.03     13306148.49
      2246315.25     13306156.13      2246389.55     13306138.77
      2246582.61     13306008.91      2246763.26     13305903.39

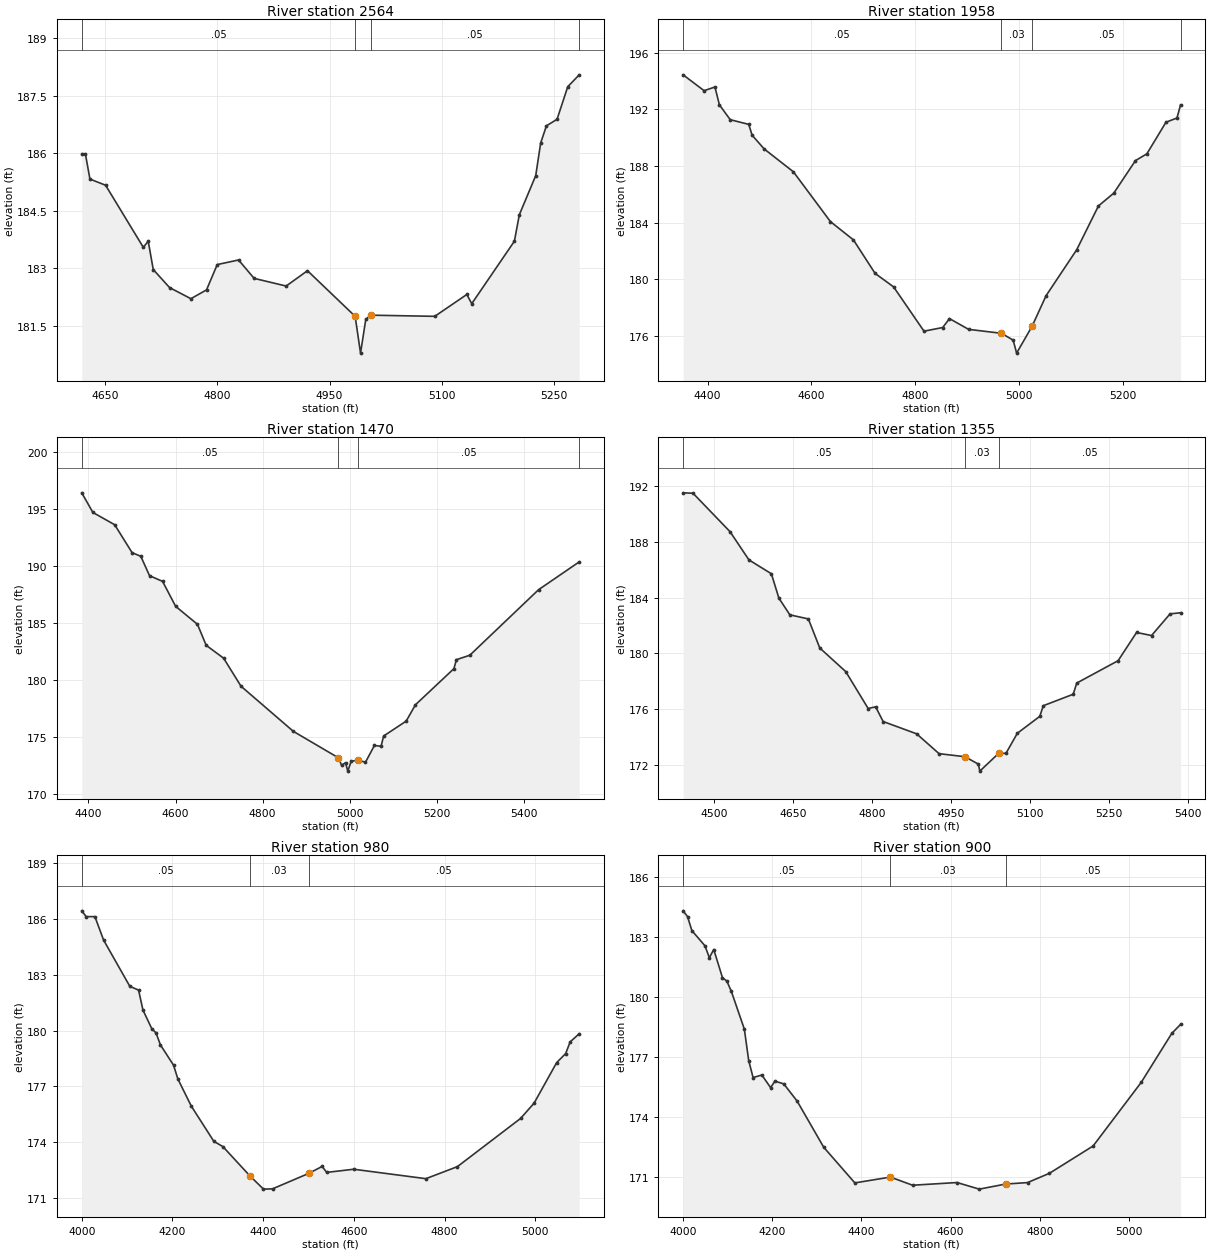
Type RM Length L Ch R = 1 ,2564    ,606,606,606
BEGIN DESCRIPTION:
UNT035 IN SPCR 3.0
END DESCRIPTION:
XS GIS Cut Line= 2
      2245124.82      13304969.2      2245558.83     13304465.75
#Sta/Elev= 30
  4618.9  185.99  4623.7  185.99  4629.8  185.33  4650.7  185.17  4701.1  183.55
  4707.7  183.71  4714.4  182.97  4736.2   182.5  4764.7  182.21  4785.6  182.44
  4799.9   183.1  4828.4  183.22  4849.2  182.74    4892  182.54  4920.5  182.94
  4984.2  181.75  4991.4  180.79  4998.4  181.67    5005  181.78  5090.6  181.75
  5133.4  182.32    5140  182.08    5197  183.71  5203.6   184.4  5225.5  185.42
  5232.1  186.27  5239.8  186.72    5254  186.89  5268.3  187.74  5283.6  188.05
#Mann= 4 ,-1 , 0
  4618.9     .05       0  4984.2     .03       0    5005     .05       0
  5283.6      .1       0
Bank Sta=4984.2,5005
XS Rating Curve= 0 ,0
Exp/Cntr=0.3,0.1

Type RM Length L Ch R = 1 ,1958    ,488,488,488
BEGIN DESCRIPTION:
UNT035 IN SPCR 2.0
END DESCRIPTION:
XS GIS Cut Line= 2
      2245319.38     13305304.94       2246100.6     13304749.41
#Sta/Elev= 30
    4353  194.44  4393.4  193.32  4414.3  193.58  4422.9  192.32  4443.8  191.27
  4479.5  190.94  4485.9  190.18    4509  189.21  4565.5  187.59  4636.9  184.07
  4681.2  182.78    4723  180.41  4758.6  179.46  4817.2  176.33  4853.3  176.59
  4866.3  177.22  4903.1  176.46  4966.4  176.18    4989   175.7  4995.7  174.78
  5025.5  176.68  5052.5  178.84  5111.6  182.09  5153.4  185.18  5182.9  186.08
  5224.7  188.38  5246.7  188.86  5283.5  191.09  5304.7  191.39  5311.6  192.32
#Mann= 4 ,-1 , 0
    4353     .05       0  4966.4     .03       0  5025.5     .05       0
  5311.6     .05       0
Bank Sta=4966.4,5025.5
XS Rating Curve= 0 ,0
Exp/Cntr=0.3,0.1

Type RM Length L Ch R = 1 ,1470    ,115,115,115
BEGIN DESCRIPTION:
Mapping XS 8ba182c9
END DESCRIPTION:
XS GIS Cut Line= 4
       2245332.3     13305429.28      2245918.22     13305411.05
      2245988.53      13305379.8      2246243.26     13304974.32
#Sta/Elev= 30
  4384.7  196.41  4410.1  194.69  4460.2  193.61  4500.2  191.16  4520.2  190.84
  4540.2  189.14  4570.2  188.64  4600.2  186.45  4650.3  184.87  4670.3  183.03
  4710.3   181.9  4750.3  179.44  4870.4  175.48  4973.4  173.17  4981.3   172.5
  4990.2  172.73  4995.4  171.99  5003.2  172.85  5018.9  172.96    5036  172.77
  5056.5  174.24  5071.8  174.17  5077.7  175.07  5129.5  176.38  5150.7  177.81
    5239  180.98  5244.9  181.77  5275.6  182.16  5433.4  187.91  5526.7  190.35
#Mann= 4 ,-1 , 0
  4384.7     .05       0  4973.4     .03       0  5018.9     .05       0
  5526.7     .05       0
Bank Sta=4973.4,5018.9
XS Rating Curve= 0 ,0
Exp/Cntr=0.3,0.1

Type RM Length L Ch R = 1 ,1355    ,375,375,375
BEGIN DESCRIPTION:
Mapping XS fc81b561
END DESCRIPTION:
XS GIS Cut Line= 2
      2245562.46     13305877.83      2246264.14     13305245.45
#Sta/Elev= 30
  4441.4  191.49  4460.2  191.46  4530.5  188.71  4566.4  186.69    4609   185.7
  4623.2  183.96  4644.1  182.76  4679.2  182.47  4700.9  180.39  4750.2   178.7
  4792.8  176.06    4807  176.18  4821.2  175.13  4884.8  174.25  4927.4  172.83
  4976.7  172.61  5002.1  172.08  5004.8  171.58  5040.8  172.86  5054.4  172.85
  5076.1  174.29  5118.7   175.5  5125.4  176.26  5182.2  177.08  5188.9  177.88
  5267.4  179.48  5302.5   181.5  5330.9  181.28  5366.1  182.83    5386  182.91
#Mann= 3 , 0 , 0
  4441.4     .05       0  4976.7     .03       0  5040.8     .05       0
Bank Sta=4976.7,5040.8
XS Rating Curve= 0 ,0
Exp/Cntr=0.3,0.1

Type RM Length L Ch R = 1 ,980     ,80,80,80
BEGIN DESCRIPTION:
Mapping XS 02adce2b
END DESCRIPTION:
XS GIS Cut Line= 4
      2245677.77     13305960.53      2245896.52     13305970.95
       2246174.3     13305724.42     2246523.497    13305362.715
#Sta/Elev= 30
    4000186.4471 4009.63 186.135  4028.9186.1343 4048.17184.8696 4105.98182.3819
 4125.25  182.18 4134.89181.1058 4154.16180.1128 4163.79179.8725 4173.43179.2292
 4202.33178.1399 4211.96 177.392  4241.5175.9352 4291.26174.0369 4311.16173.7564
 4370.86172.1766 4400.72171.4663 4420.62 171.481 4500.23172.3101 4530.08172.6881
 4540.03172.3669 4599.74172.5366 4758.84172.0288 4828.45 172.679 4967.66175.2717
  4997.5176.0969 5047.22178.2758  5067.1178.7642 5077.05179.3945 5096.94  179.83
#Mann= 3 , 0 , 0
    4000     .05       0 4370.86     .03       0 4500.23     .05       0
Bank Sta=4370.86,4500.23
XS Rating Curve= 0 ,0
Exp/Cntr=0.3,0.1

Type RM Length L Ch R = 1 ,900     ,251,251,251
BEGIN DESCRIPTION:
Mapping XS 30f8a9f0
END DESCRIPTION:
XS GIS Cut Line= 4
      2245719.47     13306009.15      2245931.24     13306047.34
      2246268.05     13305738.31     2246588.601    13305430.423
#Sta/Elev= 30
    4000184.3137 4009.81184.0285 4019.62183.3234 4049.05182.5593 4058.86181.9637
 4068.67182.3757 4088.28180.9643 4098.09180.7919  4107.9180.2944 4137.33 178.388
 4147.14176.8085 4156.95175.9597 4176.57176.0873 4196.19175.4576    4206175.7796
 4225.77175.6433 4255.68174.7837 4315.49172.4661 4385.27170.6812 4465.02170.9727
 4514.86170.5645 4614.55170.6999 4664.39170.3693 4723.72170.6243 4772.76170.6974
 4821.79 171.162 4919.86172.5317 5027.74175.7176 5096.39178.1741    5116178.6224
#Mann= 3 , 0 , 0
    4000     .05       0 4465.02     .03       0 4723.72     .05       0
Bank Sta=4465.02,4723.72
XS Rating Curve= 0 ,0
Exp/Cntr=0.3,0.1

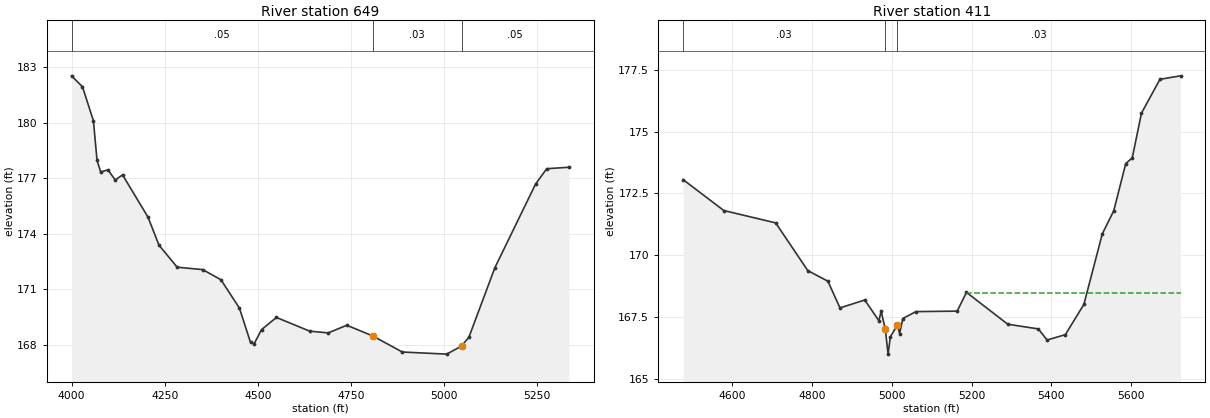
Type RM Length L Ch R = 1 ,649     ,238,238,238
BEGIN DESCRIPTION:
Mapping XS 5d9b3f95
END DESCRIPTION:
XS GIS Cut Line= 4
       2245750.7      13306064.7      2246125.68     13306182.75
      2246340.96     13306005.67     2246690.164    13305452.558
#Sta/Elev= 30
    4000182.5317 4029.34181.9403 4058.67180.1064 4068.45177.9582 4078.23177.3359
 4097.79177.4474 4117.34176.8998  4136.9 177.179 4205.35174.8903 4234.69173.3804
 4283.58172.1869 4352.03172.0574 4400.93171.5122  4450.6169.9782 4480.41168.1216
 4490.35168.0596 4510.22168.8164 4549.96 169.472 4639.38168.7302 4689.06168.6372
 4738.76169.0495 4808.34168.4743 4887.87167.6036 5007.15 167.489 5046.91167.9254
 5066.79168.4109 5136.37172.1609 5245.72176.6876 5275.54177.5115 5335.18177.5896
#Mann= 3 , 0 , 0
    4000     .05       0 4808.34     .03       0 5046.91     .05       0
Bank Sta=4808.34,5046.91
XS Rating Curve= 0 ,0
Exp/Cntr=0.3,0.1

Type RM Length L Ch R = 1 ,411     ,0,0,0
BEGIN DESCRIPTION:
UNT035 IN SPCR 1.0
END DESCRIPTION:
XS GIS Cut Line= 4
      2245935.73     13306220.74      2246191.77     13306212.07
      2246387.08     13306186.02      2246712.44     13305461.55
#Sta/Elev= 30
  4476.7  173.06  4578.7  171.81  4708.8  171.31  4789.3  169.38  4839.8  168.95
    4870  167.87  4932.2  168.19  4967.7  167.35  4973.2  167.74  4983.8     167
  4990.7     166  4996.4   166.7  5014.1  167.18  5019.6  166.83  5027.7  167.44
  5060.4  167.72    5164  167.74  5187.2   168.5  5290.8  167.21  5367.5  167.02
  5389.4  166.57  5435.3  166.79  5481.6  168.01    5528  170.87  5556.6   171.8
  5586.7  173.71    5603  173.94  5626.1  175.75  5672.5  177.12  5724.1  177.26
#Mann= 3 , 0 , 0
  4476.7     .03       0  4983.8    .025       0  5014.1     .03       0
#XS Ineff= 2 , 0
                         5185.91          168.46
Permanent Ineff=
       F       F
Bank Sta=4983.8,5014.1
XS Rating Curve= 0 ,0
Exp/Cntr=0.3,0.1

Chan Stop Cuts=-1
Use User Specified Reach Order=0
Composite Channel Slope=5