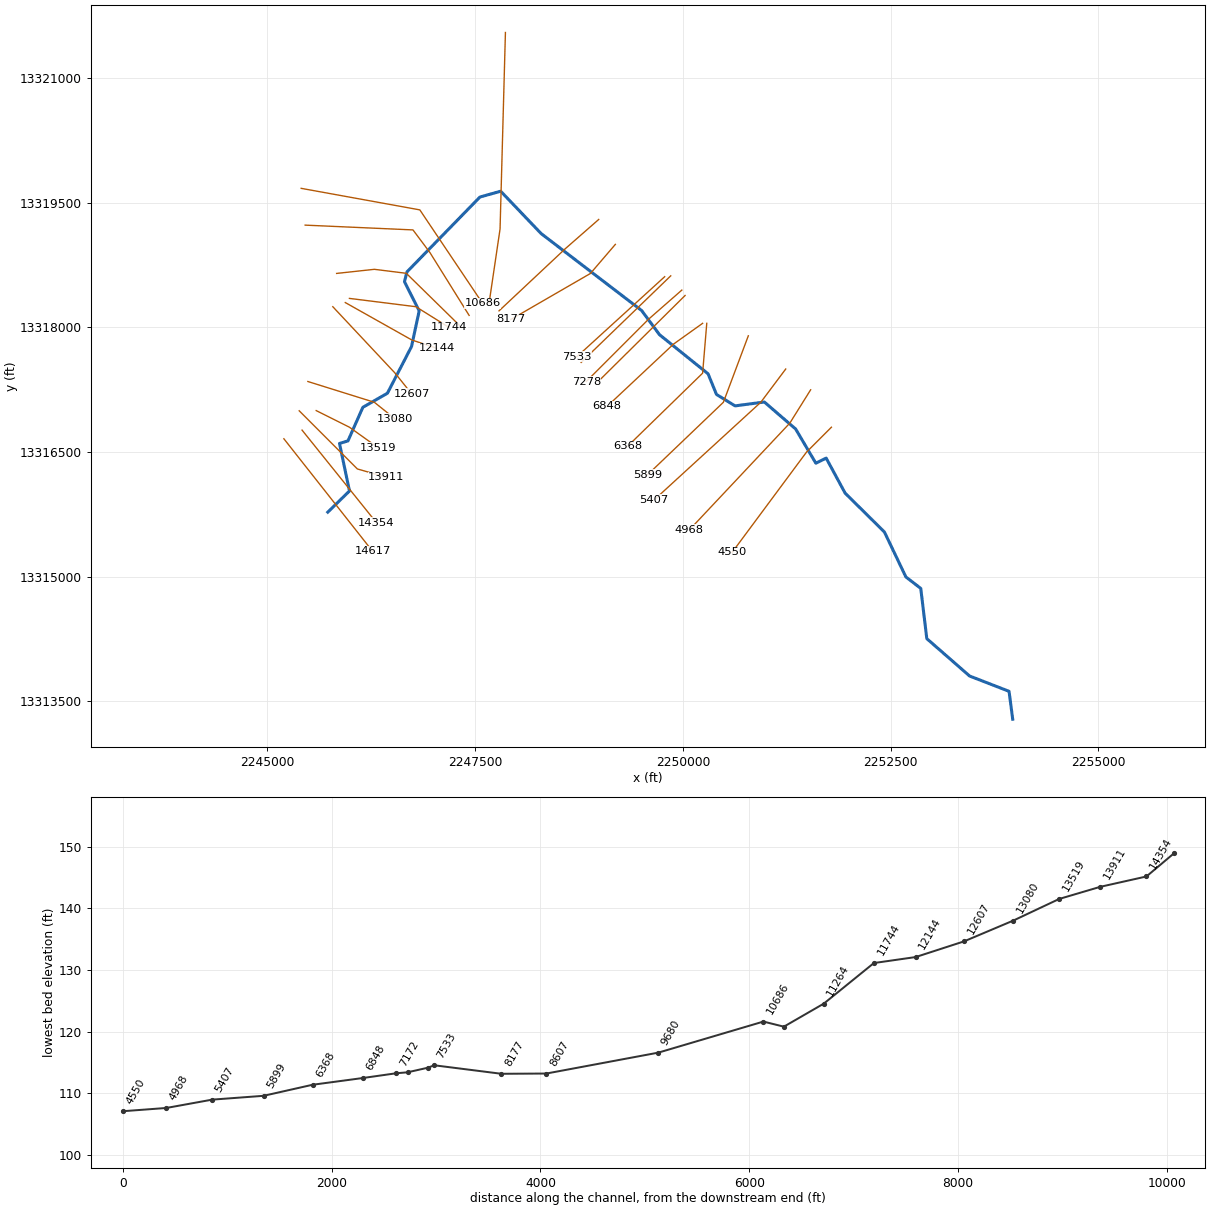
--- UNT036 IN SPCR.prj (project) ---

Proj Title=UNT036 IN SPCR Base Level Engineering
Current Plan=p01
Default Exp/Contr=0.3,0.1
English Units
Geom File=g01
Flow File=f01
Plan File=p01
Y Axis Title=Elevation
X Axis Title(PF)=Main Channel Distance
X Axis Title(XS)=Station
BEGIN DESCRIPTION:
UNT036 IN SPCR
END DESCRIPTION:
DSS File=dss
DSS Export Rating Curves= 0
DSS Export Rating Curve Sorted= 0
DSS Export Volume Flow Curves= 0
DXF OffsetX= 0
DXF OffsetY= 0
DXF ScaleX= 1
DXF ScaleY= 10

--- UNT036 IN SPCR.p01 (plan) ---

Plan Title=Multiple Run
Program Version=4.10
Short Identifier=Multiple Run
Geom File=g01
Flow File=f01
Subcritical Flow
K Sum by GR= 0
Std Step Tol= 0.01
Critical Tol= 0.01
Num of Std Step Trials= 20
Max Error Tol= 0.3
Flow Tol Ratio= 0.001
Split Flow NTrial= 30
Split Flow Tol= 0.02
Split Flow Ratio= 0.02
Log Output Level= 0
Friction Slope Method= 1
Unsteady Friction Slope Method= 2
Unsteady Bridges Friction Slope Method= 1
Parabolic Critical Depth
Global Vel Dist= 1 , 1 , 1
Global Log Level= 0
CheckData=True
Encroach Param=-1 ,0,0, 0
BEGIN DESCRIPTION:
Multiple Run
END DESCRIPTION:
Computation Interval=1HOUR
Output Interval=1HOUR
Run HTab= 0
Run UNet= 0
Run PostProcess= 0
Run WQNet= 0
UNET Theta= 1
UNET Theta Warmup= 1
UNET ZTol= 0.02
UNET ZSATol= 0.05
UNET MxIter= 20
UNET MaxInSteps= 0
UNET DtIC= 0
UNET DtMin= 0
UNET MaxCRTS= 20
UNET WFStab= 2
UNET SFStab= 1
UNET WFX= 1
UNET SFX= 1
UNET DSS MLevel= 4
UNET DZMax Abort= 100
UNET Convert EG Bridges= 0
UNET Use Existing IB Tables=-1
UNET Froude Reduction=False
UNET Froude Limit= 1
UNET Froude Power= 10
UNET Time Slicing=0,0, 5
UNET Junction Losses=0
Instantaneous Interval=1HOUR
DSS File=dss
Write IC File= 0
Write IC File at Sim End=0
Echo Input=False
Echo Parameters=False
Echo Output=False
Write Detailed= 0
WQ AD Non Conservative
WQ ULTIMATE=-1
WQ Max Comp Step=1HOUR
WQ Output Interval=15MIN
WQ Output Selected Increments= 0
WQ Output face flow=0
WQ Output face velocity=0
WQ Output face area=0
WQ Output face dispersion=0
WQ Output cell volume=0
WQ Output cell surface area=0
WQ Output cell continuity=0
WQ Output cumulative cell continuity=0
WQ Output face conc=0
WQ Output face dconc_dx=0
WQ Output face courant=0
WQ Output face peclet=0
WQ Output face adv mass=0
WQ Output face disp mass=0
WQ Output cell mass=0
WQ Output cell source sink temp=0
WQ Output cell source sink nsm=0
WQ Output MaxMinRange=-1
WQ Daily Max Min Mean=-1
WQ Daily Range=0
WQ Daily Time=0
WQ Create Restart=0
WQ Fixed Restart=0
WQ System Summary=0
WQ Use Fixed Temperature=0
Sorting and Armoring Iterations= 10
XS Update Threshold= 0.02
Hydraulics Update Threshold= 0.02
Energy Slope Method= 1
Volume Change Method= 0
XS Weighting Method= 0
Number of US Weighted Cross Sections= 1
Number of DS Weighted Cross Sections= 1
Upstream XS Weight=0.25
Main XS Weight=0.5
Downstream XS Weight=0.25
Number of DS XS's Weighted with US Boundary= 1
Upstream Boundary Weight= 1
Weight of XSs Associated with US Boundary= 0
Number of US XS's Weighted with DS Boundary= 1
Downstream Boundary Weight= 0.5
Weight of XSs Associated with DS Boundary= 0.5
Sediment Output Level= 4
Mass or Volume Output= 0
Output Increment Type= 1
Profile and TS Output Increment= 10
XS Output Flag= 0
XS Output Increment= 10
Disregard all LS=0
Disregard all Conn=0
Disregard all Breaches=0
Disregard all Pumps=0

--- UNT036 IN SPCR.f01 (steady flow) ---

Flow Title=Multiple
Number of Profiles=7
Profile Names=10-year,25-year,50-year,1pct_min,100-year,1pct_plu,500-year
River Rch & RM= UNT036 IN SPCR,Reach-1,14617
     155     208     250     221     299     405     435
River Rch & RM= UNT036 IN SPCR,Reach-1,14354
     258     355     436     393     531     718     801
River Rch & RM= UNT036 IN SPCR,Reach-1,6368
     328     459     567     515     697     943    1069
River Rch & RM= UNT036 IN SPCR,Reach-1,1881
     443     629     786     721     975    1319    1524
Boundary for River Rch & Prof#=UNT036 IN SPCR,Reach-1,1
Up Type=0
Dn Type=3
Dn Slope=0.005
Boundary for River Rch & Prof#=UNT036 IN SPCR,Reach-1,2
Up Type=0
Dn Type=3
Dn Slope=0.005
Boundary for River Rch & Prof#=UNT036 IN SPCR,Reach-1,3
Up Type=0
Dn Type=3
Dn Slope=0.005
Boundary for River Rch & Prof#=UNT036 IN SPCR,Reach-1,4
Up Type=0
Dn Type=3
Dn Slope=0.005
Boundary for River Rch & Prof#=UNT036 IN SPCR,Reach-1,5
Up Type=0
Dn Type=3
Dn Slope=0.005
Boundary for River Rch & Prof#=UNT036 IN SPCR,Reach-1,6
Up Type=0
Dn Type=3
Dn Slope=0.005
Boundary for River Rch & Prof#=UNT036 IN SPCR,Reach-1,7
Up Type=0
Dn Type=3
Dn Slope=0.005

--- UNT036 IN SPCR.g01 (geometry) ---

Geom Title=Existing Conditions
Program Version=4.10

River Reach=UNT036 IN SPCR  ,Reach-1
Reach XY= 30
      2245727.28     13315774.54      2245988.23     13316029.24
      2245868.31     13316601.09      2245970.33     13316632.38
      2246149.12     13317036.19      2246444.75     13317205.58
      2246735.07     13317767.89       2246827.2      13318196.7
      2246650.12     13318548.06      2246680.15     13318665.92
      2247557.82     13319566.25      2247807.72     13319636.85
      2248294.29      13319127.2      2249503.91     13318201.07
      2249718.67      13317910.4      2250303.34     13317439.62
       2250404.6     13317191.25      2250628.15     13317053.46
      2250980.18     13317100.16      2251356.86     13316775.99
      2251600.17     13316363.72      2251724.54     13316424.95
      2251952.51     13316003.65      2252425.51     13315535.96
      2252683.55     13314995.31      2252862.75     13314857.03
      2252935.62     13314252.56       2253450.2     13313803.08
       2253925.2      13313618.7      2253969.34     13313282.92

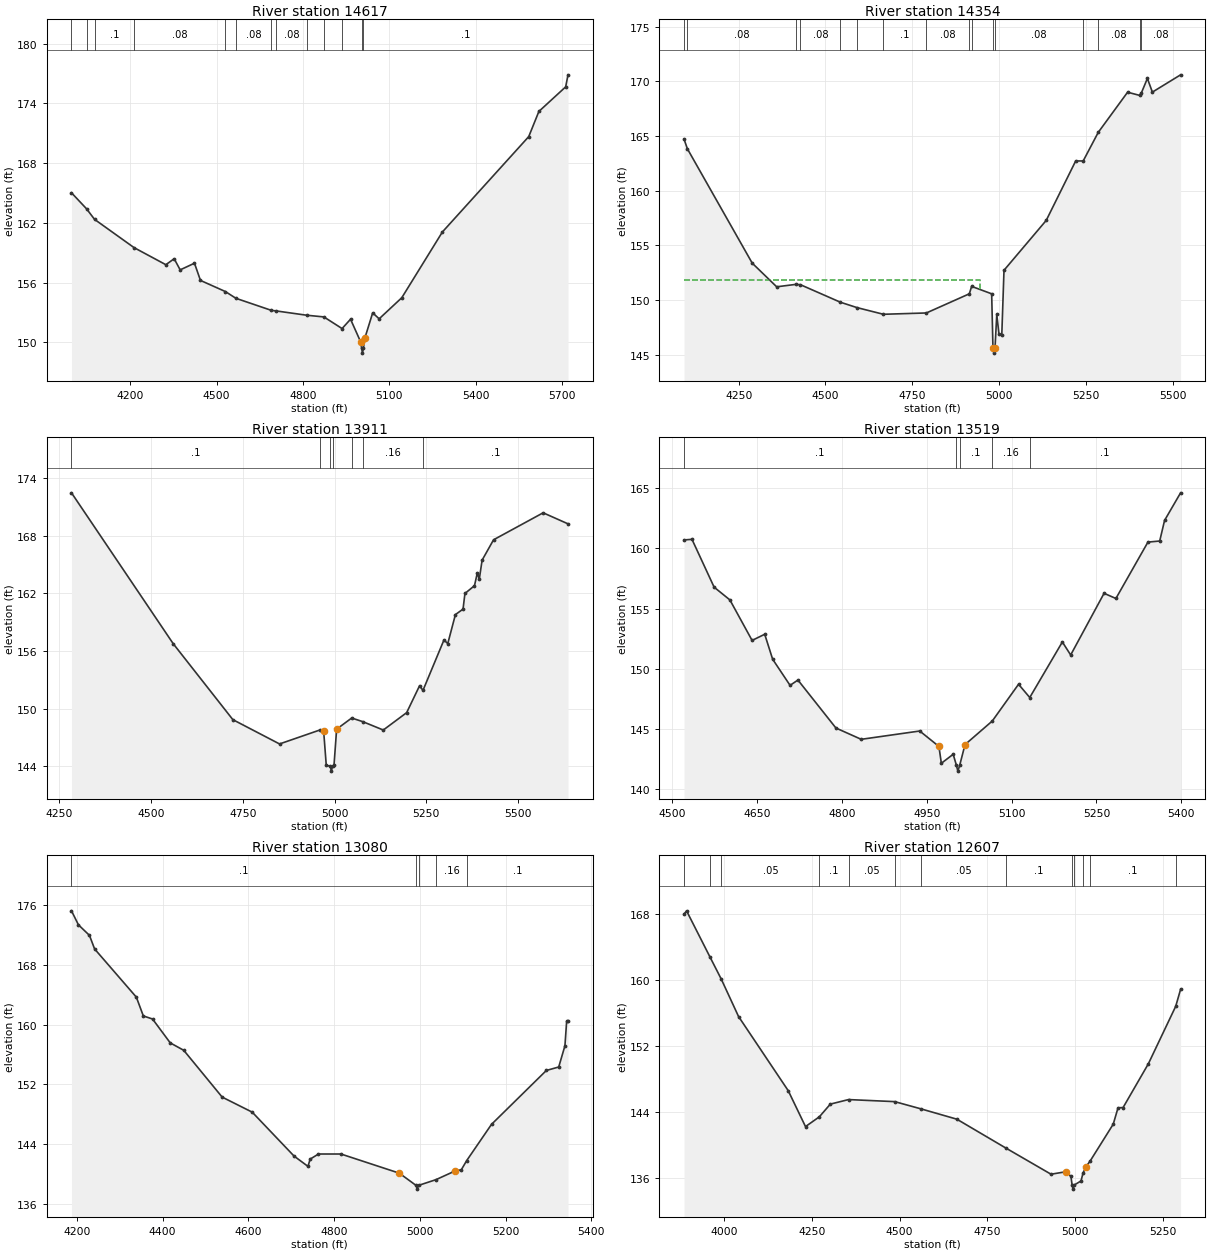
Type RM Length L Ch R = 1 ,14617   ,263,263,263
BEGIN DESCRIPTION:
UNT036 IN SPCR 27.0
END DESCRIPTION:
XS GIS Cut Line= 2
      2245198.79      13316657.9      2246266.46     13315303.78
#Sta/Elev= 30
  3996.3  165.02  4048.6  163.41  4076.3  162.35  4213.4  159.51    4324  157.79
  4352.9  158.39  4373.7  157.27  4423.4  157.94  4444.2  156.21  4530.8  155.09
  4567.5  154.41  4690.4   153.2    4708  153.14  4813.2  152.71  4872.8  152.54
    4936  151.37  4965.4  152.31  5000.7  150.02    5004   149.4  5006.8   148.9
    5010   149.4  5015.1  150.41  5042.3  152.95  5064.8  152.35  5143.4  154.47
  5284.4  161.08  5584.3  170.67  5619.5   173.2  5712.5  175.67  5720.7  176.88
#Mann= 13 ,-1 , 0
  3996.3      .1       0  4048.6     .08       0  4076.3      .1       0
  4213.4     .08       0  4530.8      .1       0  4567.5     .08       0
  4690.4      .1       0    4708     .08       0  4813.2      .1       0
  4872.8     .08       0    4936      .1       0    5004     .07       0
    5010      .1       0
Bank Sta=5000.7,5015.1
XS Rating Curve= 0 ,0
Exp/Cntr=0.3,0.1

Type RM Length L Ch R = 1 ,14354   ,443,443,443
BEGIN DESCRIPTION:
Mapping XS f0b811cb
END DESCRIPTION:
XS GIS Cut Line= 2
       2245417.5     13316762.12      2246313.04      13315647.9
#Sta/Elev= 30
  4092.8  164.71  4102.4  163.83  4289.1  153.38  4359.5  151.22  4414.1  151.44
    4428  151.41    4543  149.81  4590.7  149.32  4666.7  148.71  4790.4  148.83
  4914.1  150.58  4920.7  151.26  4978.4  150.58  4982.1  145.66  4984.9  145.16
  4988.1  145.66  4993.1  148.69  4999.5  146.87  5007.5  146.78  5013.9  152.73
  5135.5  157.29  5220.3  162.72  5241.9  162.72  5285.2  165.33  5369.7     169
  5404.7  168.71  5408.8  168.89  5426.7  170.26  5441.1  169.01  5522.3  170.59
#Mann= 16 ,-1 , 0
  4092.8      .1       0  4102.4     .08       0  4414.1      .1       0
    4428     .08       0    4543      .1       0  4590.7     .08       0
  4666.7      .1       0  4790.4     .08       0  4914.1      .1       0
  4920.7     .08       0  4982.1     .07       0  4988.1     .08       0
  5241.9      .1       0  5285.2     .08       0  5404.7      .1       0
  5408.8     .08       0
#XS Ineff= 2 , 0
         4945.45  151.87
Permanent Ineff=
       F       F
Bank Sta=4982.1,4988.1
XS Rating Curve= 0 ,0
Exp/Cntr=0.3,0.1

Type RM Length L Ch R = 1 ,13911   ,392,392,392
BEGIN DESCRIPTION:
UNT036 IN SPCR 26.0
END DESCRIPTION:
XS GIS Cut Line= 3
      2245383.28     13316994.56      2246083.25     13316294.59
      2246432.95     13316194.68
#Sta/Elev= 30
  4282.7  172.46    4560  156.75  4722.6  148.84  4849.9  146.31  4961.1  147.78
  4970.1  147.66  4977.2   144.1  4988.3  143.98  4991.1  143.48  4994.3  143.98
  4998.4  144.12  5005.5  147.85  5046.6  149.01  5076.9  148.63  5132.7  147.76
  5196.4  149.57  5231.7  152.38  5240.8  151.88  5298.1  157.14  5308.5  156.76
  5329.3  159.78  5350.1  160.35  5355.3  161.98  5381.3  162.79  5389.1  164.13
  5394.3  163.44  5402.1  165.45  5433.3  167.57  5568.5  170.38  5636.3  169.23
#Mann= 7 ,-1 , 0
  4282.7      .1       0  4961.1     .16       0  4988.3     .07       0
  4994.3     .16       0  5046.6      .1       0  5076.9     .16       0
  5240.8      .1       0
Bank Sta=4970.1,5005.5
XS Rating Curve= 0 ,0
Exp/Cntr=0.3,0.1

Type RM Length L Ch R = 1 ,13519   ,439,439,439
BEGIN DESCRIPTION:
UNT036 IN SPCR 25.0
END DESCRIPTION:
XS GIS Cut Line= 3
      2245587.74     13316996.85      2245987.72     13316796.85
      2246337.71     13316546.86
#Sta/Elev= 30
  4521.4  160.71  4535.4  160.76  4574.5  156.79  4602.4  155.73  4641.6  152.37
  4663.9  152.88  4677.9  150.81  4708.7  148.64  4722.6  149.08  4789.7   145.1
  4834.4  144.16  4937.8  144.85  4971.7  143.57    4976  142.17  4996.9  142.92
  5002.5  142.02  5005.2  141.52  5008.5  142.02  5017.8  143.72    5066  145.68
  5112.4  148.73  5132.2  147.63  5189.8  152.24  5204.5  151.16  5263.5  156.28
  5284.4  155.85    5341  160.53  5361.8  160.62  5370.4  162.33  5398.7  164.62
#Mann= 5 ,-1 , 0
  4521.4      .1       0  5002.5     .07       0  5008.5      .1       0
    5066     .16       0  5132.2      .1       0
Bank Sta=4971.7,5017.8
XS Rating Curve= 0 ,0
Exp/Cntr=0.3,0.1

Type RM Length L Ch R = 1 ,13080   ,473,473,473
BEGIN DESCRIPTION:
UNT036 IN SPCR 24.0
END DESCRIPTION:
XS GIS Cut Line= 3
      2245487.77     13317346.84      2246287.72     13317096.85
      2246537.75     13316896.83
#Sta/Elev= 30
  4187.4  175.19  4203.6  173.32  4229.3  171.91  4241.3   170.1  4338.7  163.66
    4355  161.15  4376.5  160.74  4417.8  157.55  4449.3  156.56  4538.9  150.31
    4609   148.3  4706.5  142.44    4739  141.06  4744.2  142.03  4763.6  142.71
    4816  142.71  4952.2  140.15  4991.1  138.52  4993.8  138.02  4997.1  138.52
  5037.9  139.29  5082.3  140.45  5096.7   140.6  5109.3  141.83  5167.2  146.67
  5295.2  153.87    5324  154.33  5338.5  157.17  5342.5  160.43  5345.7  160.43
#Mann= 5 ,-1 , 0
  4187.4      .1       0  4991.1     .07       0  4997.1      .1       0
  5037.9     .16       0  5109.3      .1       0
Bank Sta=4952.2,5082.3
XS Rating Curve= 0 ,0
Exp/Cntr=0.3,0.1

Type RM Length L Ch R = 1 ,12607   ,463,463,463
BEGIN DESCRIPTION:
UNT036 IN SPCR 23.0
END DESCRIPTION:
XS GIS Cut Line= 3
      2245787.74     13318246.83      2246537.72     13317446.85
      2246737.71     13317196.86
#Sta/Elev= 30
  3884.8  168.02  3891.9  168.42  3959.2  162.78  3991.2  160.11  4040.3  155.59
    4182  146.59  4231.3  142.23  4270.9  143.42  4302.2  144.96  4354.1  145.51
  4485.8  145.26  4560.1  144.39  4663.1  143.13    4804   139.6  4931.8  136.45
  4974.3  136.75  4988.6  136.19    4992  135.14  4994.7  134.64    4998  135.14
  5017.4  135.63  5023.2   136.6  5031.8  137.36  5044.3  138.11  5109.4  142.53
    5123  144.51  5137.4  144.54  5209.5  149.85  5287.6  156.83  5301.5  158.89
#Mann= 13 ,-1 , 0
  3884.8     .05       0  3959.2      .1       0  3991.2     .05       0
  4270.9      .1       0  4354.1     .05       0  4485.8      .1       0
  4560.1     .05       0    4804      .1       0    4992     .07       0
    4998      .1       0  5023.2     .16       0  5044.3      .1       0
  5287.6     .16       0
Bank Sta=4974.3,5031.8
XS Rating Curve= 0 ,0
Exp/Cntr=0.3,0.1

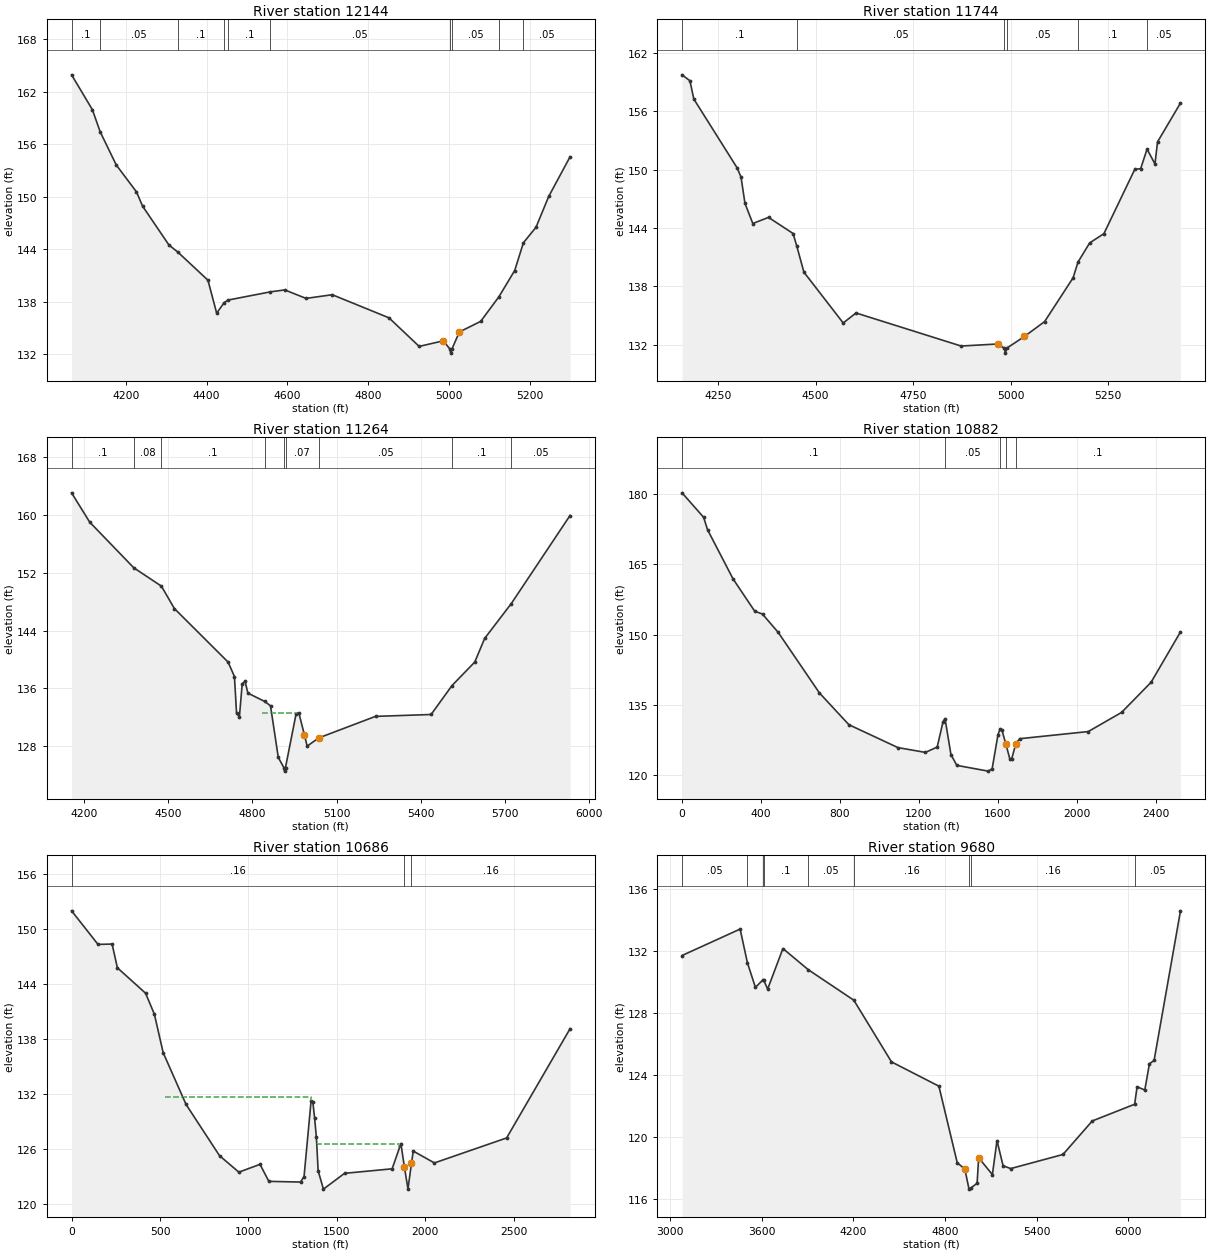
Type RM Length L Ch R = 1 ,12144   ,400,400,400
BEGIN DESCRIPTION:
UNT036 IN SPCR 22.0
END DESCRIPTION:
XS GIS Cut Line= 3
      2245937.68     13318296.88      2246737.72     13317846.85
      2247037.67     13317746.87
#Sta/Elev= 30
  4065.9  163.93  4117.3  159.95  4136.7  157.41  4176.5  153.62  4226.6  150.54
  4241.6  148.92  4306.9  144.47  4329.1  143.65  4403.5  140.44  4425.1  136.67
  4443.7  137.88  4453.4  138.17  4558.3  139.11  4593.7  139.33  4646.3  138.36
  4711.3  138.78  4851.6  136.14  4926.5  132.87  4986.5  133.51  5001.9   132.6
  5004.7   132.1  5007.9   132.6    5026  134.52  5078.7  135.73  5123.8  138.54
    5163  141.55  5184.6  144.73  5215.7  146.49  5247.3  150.03    5300  154.55
#Mann= 10 ,-1 , 0
  4065.9      .1       0  4136.7     .05       0  4329.1      .1       0
  4443.7     .05       0  4453.4      .1       0  4558.3     .05       0
  5001.9     .03       0  5007.9     .05       0  5123.8      .1       0
  5184.6     .05       0
Bank Sta=4986.5,5026
XS Rating Curve= 0 ,0
Exp/Cntr=0.3,0.1

Type RM Length L Ch R = 1 ,11744   ,480,480,480
BEGIN DESCRIPTION:
UNT036 IN SPCR 21.0
END DESCRIPTION:
XS GIS Cut Line= 3
      2245987.71     13318346.86      2246787.72     13318246.85
      2247187.69     13317996.87
#Sta/Elev= 30
  4157.8  159.75    4178  159.14    4188  157.26  4298.9  150.19    4309  149.24
  4319.1  146.54  4339.2  144.46  4379.5  145.09  4442.5  143.43  4451.6  142.19
  4470.2  139.46    4571  134.23  4603.8  135.26  4873.3  131.86    4967  132.07
    4984  131.63  4986.8  131.13    4990  131.63  5035.4  132.84  5087.3  134.37
  5160.4  138.88  5172.9  140.49  5202.8  142.46  5239.4  143.42  5318.4  150.02
  5333.7  150.11    5350  152.11  5370.3  150.58  5376.8  152.85  5435.7  156.85
#Mann= 6 ,-1 , 0
  4157.8      .1       0  4451.6     .05       0    4984     .04       0
    4990     .05       0  5172.9      .1       0    5350     .05       0
Bank Sta=4967,5035.4
XS Rating Curve= 0 ,0
Exp/Cntr=0.3,0.1

Type RM Length L Ch R = 1 ,11264   ,382,382,382
BEGIN DESCRIPTION:
UNT036 IN SPCR 20.0
END DESCRIPTION:
XS GIS Cut Line= 4
      2245833.66     13318647.43      2246287.72     13318696.85
      2246671.99     13318648.82      2247337.72     13317996.86
#Sta/Elev= 30
    4156  163.08  4220.4  159.03  4377.6   152.7    4476  150.16  4522.2  147.06
  4713.5  139.65  4736.2  137.65  4743.7  132.57  4753.8  132.04  4763.9  136.65
    4774  136.99  4784.1  135.35  4844.3  134.19  4864.7  133.59  4892.4  126.44
  4912.1  125.05  4914.8  124.55  4918.1  125.05  4955.4   132.4  4965.5  132.64
  4985.6  129.54  4995.3  128.01  5036.6  129.15  5238.8  132.13  5436.8  132.39
  5511.3   136.4  5592.4  139.65  5627.7  142.93  5722.2  147.73  5931.8  159.94
#Mann= 9 ,-1 , 0
    4156      .1       0  4377.6     .08       0    4476      .1       0
  4844.3     .07       0  4912.1     .07       0  4918.1     .07       0
  5036.6     .05       0  5511.3      .1       0  5722.2     .05       0
#XS Ineff= 1 ,-1
 4832.95 4961.36  132.58
Permanent Ineff=
       F
Bank Sta=4985.6,5036.6
XS Rating Curve= 0 ,0
Exp/Cntr=0.3,0.1

Type RM Length L Ch R = 1 ,10882   ,196,196,196
BEGIN DESCRIPTION:
UNT036 IN SPCR 19.0
END DESCRIPTION:
XS GIS Cut Line= 4
     2245454.901     13319228.55     2246752.367    13319171.037
     2246956.803    13318897.985     2247427.941    13318142.301
#Sta/Elev= 30
       0180.2668  109.42175.0376  129.31172.3797  258.62161.8749  368.03154.9959
  407.82154.3581  487.39150.4543  696.28137.5195  845.48130.7358 1094.15125.8444
 1233.41124.8161 1293.09125.9553 1322.93131.4167 1332.87132.0249 1362.71124.3683
 1392.54122.0434 1551.64120.8167 1571.53121.3126 1601.36128.6347 1611.31129.7232
 1621.25129.5786 1641.14126.5867 1661.03  123.47 1670.97  123.47 1690.86126.5721
 1710.75127.7412 2058.79129.2714 2227.83133.3649 2376.99139.7898 2526.15150.5537
#Mann= 5 ,-1 , 0
       0      .1       0 1332.87     .05       0 1611.31     .07       0
 1641.14     .03       0 1690.86      .1       0
#XS Ineff= 3 ,-1
  680.11 1327.84  130.95 1343.18 1609.09  128.67 1769.56 1950.39  127.97
Permanent Ineff=
       F       F       F
Bank Sta=1641.14,1690.86
XS Rating Curve= 0 ,0
Exp/Cntr=0.3,0.1

Type RM Length L Ch R = 1 ,10686   ,1006,1006,1006
BEGIN DESCRIPTION:
Mapping XS 5d22eaf2
END DESCRIPTION:
XS GIS Cut Line= 4
     2245407.158    13319671.258     2246834.814     13319412.07
     2247087.776    13319035.289     2247589.399    13318288.134
#Sta/Elev= 30
       0151.9862  149.39148.3258  229.06148.3628  258.94145.7755  418.29143.0078
  468.08140.7237  517.88136.5217  647.35130.8757  836.57125.2918  946.12123.4923
 1065.63124.3462 1115.43122.4903 1294.69122.4164 1314.61123.0109 1354.45131.2678
 1364.41131.1325 1374.37129.3829 1384.33127.3061 1394.29123.6553 1424.17121.6434
  1543.7123.3666 1812.67123.8581 1862.48126.6081 1882.41124.0091 1902.33  121.67
 1922.25124.4638 1932.21 125.792 2051.76124.4993  2460.2127.2235 2818.83139.1291
#Mann= 3 , 0 , 0
       0     .16       0 1882.41     .03       0 1922.25     .16       0
#XS Ineff= 3 ,-1
  525.63 1355.49   131.7 1380.85 1854.08  126.53  1936.9 2498.03  125.43
Permanent Ineff=
       F       F       T
Bank Sta=1882.41,1922.25
XS Rating Curve= 0 ,0
Exp/Cntr=0.3,0.1

Type RM Length L Ch R = 1 ,9680    ,1073,1073,1073
BEGIN DESCRIPTION:
UNT036 IN SPCR 18.0
END DESCRIPTION:
XS GIS Cut Line= 3
      2247864.89     13321546.71      2247800.34     13319182.23
      2247669.26     13318295.93
#Sta/Elev= 30
  3078.9  131.72  3458.9  133.43  3506.6  131.25  3558.9  129.66  3608.8  130.15
    3614  130.11    3639  129.55    3739  132.17  3905.1   130.8  4202.8  128.83
  4449.3  124.84  4759.4  123.27  4879.4  118.32  4929.4   117.9  4956.5  116.61
  4969.5  116.69  5009.5  116.99  5019.5  118.64  5109.5  117.55  5139.5  119.75
  5179.5  118.12  5229.6  117.94    5571  118.85  5763.1  121.02  6040.2   122.1
  6056.2  123.23  6106.6  123.02  6137.1  124.72  6167.4  124.93  6340.2  134.61
#Mann= 9 ,-1 , 0
  3078.9     .05       0  3506.6      .1       0  3608.8     .05       0
    3614      .1       0  3905.1     .05       0  4202.8     .16       0
  4956.5     .07       0  4969.5     .16       0  6040.2     .05       0
#Block Obstruct= 2 , 0
       0                  5139.5       0  119.75
Bank Sta=4929.4,5019.5
XS Rating Curve= 0 ,0
Exp/Cntr=0.3,0.1

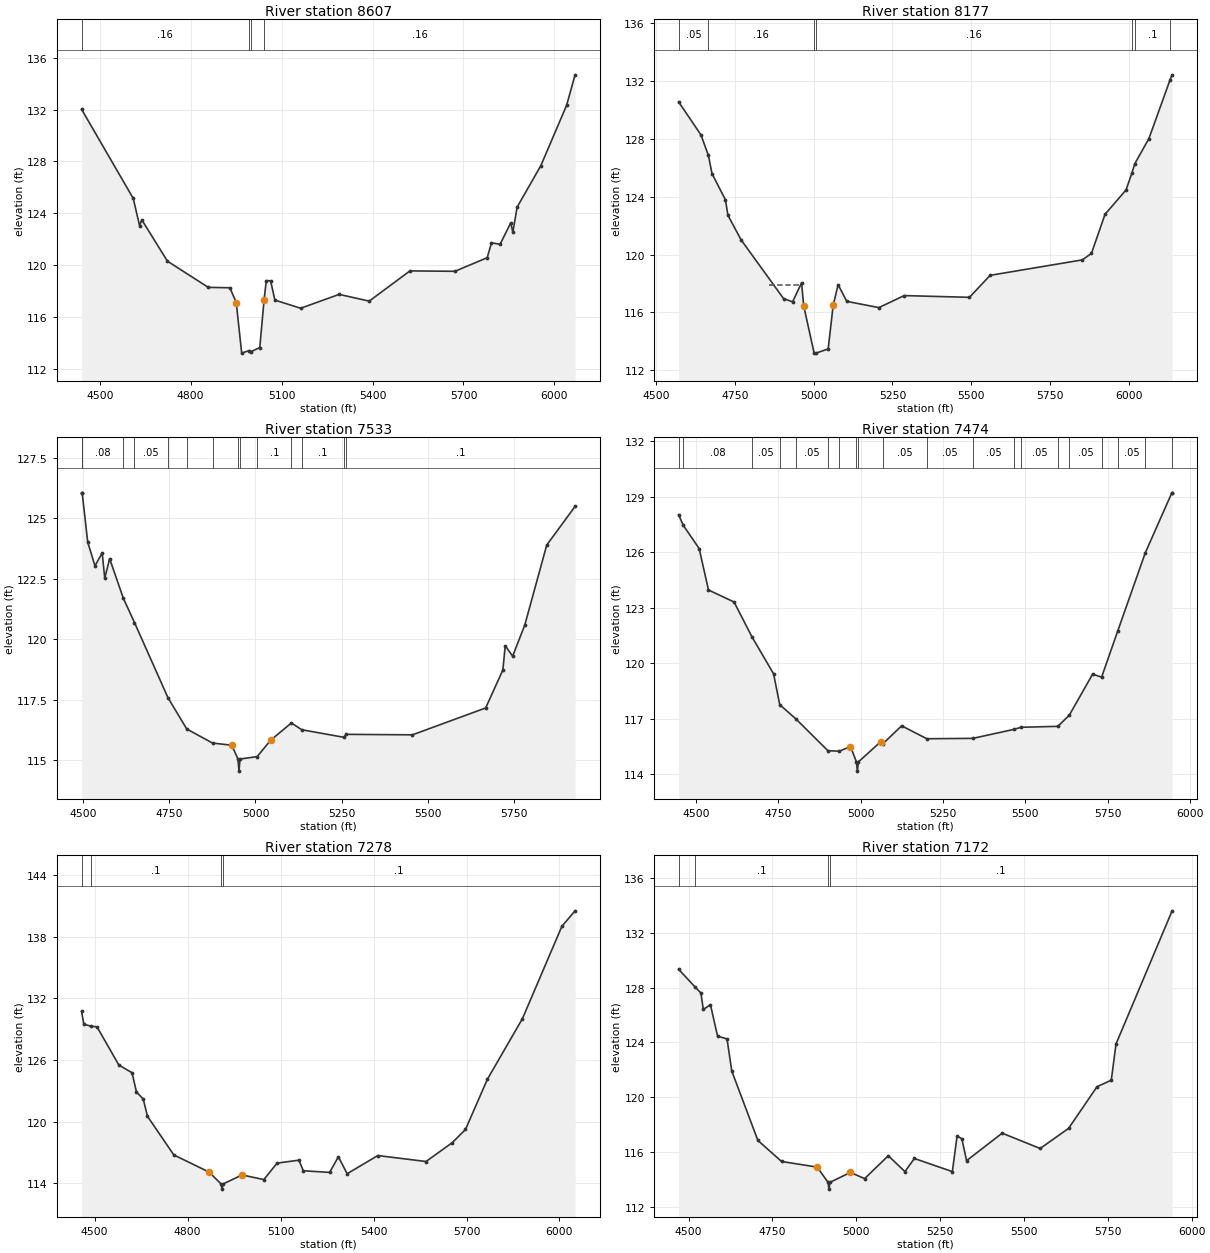
Type RM Length L Ch R = 1 ,8607    ,430,430,430
BEGIN DESCRIPTION:
UNT036 IN SPCR 17.0
END DESCRIPTION:
XS GIS Cut Line= 3
      2248987.72     13319296.86      2248587.72     13318946.85
      2247787.72     13318196.85
#Sta/Elev= 30
  4440.2  132.02  4610.6  125.15  4631.4  123.06    4639  123.49  4723.5  120.31
  4858.3  118.29  4929.5  118.26  4950.4  117.12  4968.4  113.22    4993  113.42
  4999.8  113.34  5028.1  113.65  5042.3  117.34  5049.6  118.81  5063.8   118.8
  5077.9  117.31  5162.9  116.68  5289.9  117.75  5389.1  117.23  5523.4  119.56
  5671.9  119.53  5778.4  120.58  5792.5  121.73  5820.9  121.61  5856.1  123.27
  5862.9  122.54  5877.1  124.48  5955.2  127.67  6040.2  132.32  6068.3  134.68
#Mann= 4 ,-1 , 0
  4440.2     .16       0    4993     .07       0  4999.8      .1       0
  5042.3     .16       0
#Block Obstruct= 2 , 0
                         5058.64          118.73
Bank Sta=4950.4,5042.3
XS Rating Curve= 0 ,0
Exp/Cntr=0.3,0.1

Type RM Length L Ch R = 1 ,8177    ,644,644,644
BEGIN DESCRIPTION:
UNT036 IN SPCR 16.0
END DESCRIPTION:
XS GIS Cut Line= 3
      2249187.71     13318996.84      2248887.72     13318646.85
      2247931.21     13318093.71
#Sta/Elev= 30
  4571.7  130.56  4642.5  128.28  4666.3  126.85  4677.6   125.6  4720.4  123.78
  4728.1  122.72  4769.8  121.02  4904.8  116.95  4933.3  116.73  4961.9  118.04
  4968.5  116.46  5001.7  113.18  5007.7  113.18  5046.3  113.47  5062.1  116.48
  5077.8  117.92  5105.2  116.76  5207.1  116.33  5287.5  117.16  5494.7  117.04
  5560.1  118.56  5852.8  119.63  5881.7  120.08  5924.7  122.78  5991.5  124.47
  6010.1  125.64  6019.4  126.29    6064  128.02  6130.9  132.07  6137.6  132.43
#Mann= 7 ,-1 , 0
  4571.7     .05       0  4666.3     .16       0  5001.7     .07       0
  5007.7     .16       0  6010.1     .05       0  6019.4      .1       0
  6130.9     .05       0
#XS Ineff= 2 ,-1
 4859.95 4953.86  117.88 5077.96  6137.6  117.86
Permanent Ineff=
       T       T
Bank Sta=4968.5,5062.1
XS Rating Curve= 0 ,0
Exp/Cntr=0.3,0.1

Type RM Length L Ch R = 1 ,7533    ,59,59,59
BEGIN DESCRIPTION:
Mapping XS 0f8e006c
END DESCRIPTION:
XS GIS Cut Line= 2
      2249781.29     13318608.04      2248724.06     13317644.55
#Sta/Elev= 30
  4496.1  126.06  4497.8  126.06  4513.9  124.02  4534.9  123.04  4555.8  123.58
  4563.2  122.53  4577.4  123.34  4616.9  121.71  4649.4   120.7  4746.3   117.6
  4800.9   116.3  4875.7  115.72  4931.5  115.63  4949.4  115.06  4952.2  114.56
  4955.4  115.06    5005  115.16  5044.3  115.84  5104.1  116.55  5134.4  116.27
  5255.6  115.96  5263.8  116.08  5455.1  116.06  5667.3  117.17  5717.2  118.74
    5724  119.74  5745.6  119.31  5780.8   120.6  5844.3   123.9  5926.5   125.5
#Mann= 14 ,-1 , 0
  4496.1      .1       0  4497.8     .08       0  4616.9      .1       0
  4649.4     .05       0  4746.3      .1       0  4800.9     .05       0
  4875.7      .1       0  4949.4     .04       0  4955.4      .1       0
    5005      .1       0  5104.1     .05       0  5134.4      .1       0
  5255.6     .05       0  5263.8      .1       0
Bank Sta=4931.5,5044.3
XS Rating Curve= 0 ,0
Exp/Cntr=0.3,0.1

Type RM Length L Ch R = 1 ,7474    ,196,196,196
BEGIN DESCRIPTION:
Mapping XS ce576772
END DESCRIPTION:
XS GIS Cut Line= 2
      2249854.23     13318618.47      2248776.13     13317576.84
#Sta/Elev= 30
  4447.1  128.03    4461  127.46  4509.5   126.2  4537.8  123.96  4615.5  123.31
  4670.1  121.42  4735.6  119.43  4754.3  117.76  4802.9     117  4900.9  115.27
  4935.6  115.25  4969.2   115.5  4987.3  114.67  4990.1  114.17  4993.3  114.67
  5061.1  115.76  5068.3  115.66  5124.6  116.62  5201.1  115.92  5340.8  115.94
  5466.6  116.43  5487.5  116.54  5599.3  116.59  5634.1   117.2  5704.7  119.41
  5732.1  119.25  5780.8  121.73  5864.8  125.97  5945.4  129.21  5946.2  129.21
#Mann= 20 ,-1 , 0
  4447.1     .05       0    4461     .08       0  4670.1     .05       0
  4754.3      .1       0  4802.9     .05       0  4900.9      .1       0
  4935.6     .05       0  4987.3     .04       0  4993.3     .05       0
  5068.3     .05       0  5201.1     .05       0  5340.8     .05       0
  5466.6      .1       0  5487.5     .05       0  5599.3      .1       0
  5634.1     .05       0  5732.1      .1       0  5780.8     .05       0
  5864.8      .1       0  5945.4     .05       0
Bank Sta=4969.2,5061.1
XS Rating Curve= 0 ,0
Exp/Cntr=0.3,0.1

Type RM Length L Ch R = 1 ,7278    ,106,106,106
BEGIN DESCRIPTION:
UNT036 IN SPCR 14.0
END DESCRIPTION:
XS GIS Cut Line= 3
      2249987.72     13318446.86      2249587.72     13318096.85
       2248837.7     13317346.83
#Sta/Elev= 30
  4458.1  130.72  4465.2  129.48    4488  129.29  4507.9  129.22  4578.2  125.51
  4620.9  124.75  4635.1  122.88  4656.9   122.2  4670.7  120.51  4755.7  116.75
  4869.5  115.08  4908.3  113.92  4911.1  113.42  4914.3  113.92  4975.8   114.8
  5046.2  114.35  5088.6  115.95  5159.3  116.24  5173.5  115.21  5258.3  115.05
  5286.6  116.57  5314.9  114.92  5413.9  116.69  5569.4  116.11  5654.3  117.95
  5696.7  119.23  5767.4  124.12  5880.6  130.03  6007.8  139.02  6050.3  140.52
#Mann= 4 ,-1 , 0
  4458.1     .08       0    4488      .1       0  4908.3     .07       0
  4914.3      .1       0
Bank Sta=4869.5,4975.8
XS Rating Curve= 0 ,0
Exp/Cntr=0.3,0.1

Type RM Length L Ch R = 1 ,7172    ,324,324,324
BEGIN DESCRIPTION:
Mapping XS 47f8c0a2
END DESCRIPTION:
XS GIS Cut Line= 2
      2250026.87     13318381.86      2248981.39     13317346.77
#Sta/Elev= 30
  4470.5  129.34  4519.7  128.04  4537.1   127.6  4544.1   126.4  4565.4  126.75
  4586.6  124.45  4614.8  124.25    4629   121.9  4706.8  116.83  4777.5  115.29
  4883.6  114.88  4915.9  113.77  4918.7  113.27  4921.9  113.77  4982.6  114.49
    5025  114.04  5095.7  115.71  5145.2  114.55  5173.4  115.51  5286.6  114.55
  5300.7  117.16  5314.9  116.95    5329  115.35  5435.1  117.36  5548.3  116.24
  5633.1  117.71    5718  120.76  5760.4  121.23  5774.5  123.88  5941.7  133.61
#Mann= 4 ,-1 , 0
  4470.5     .08       0  4519.7      .1       0  4915.9     .07       0
  4921.9      .1       0
Bank Sta=4883.6,4982.6
XS Rating Curve= 0 ,0
Exp/Cntr=0.3,0.1

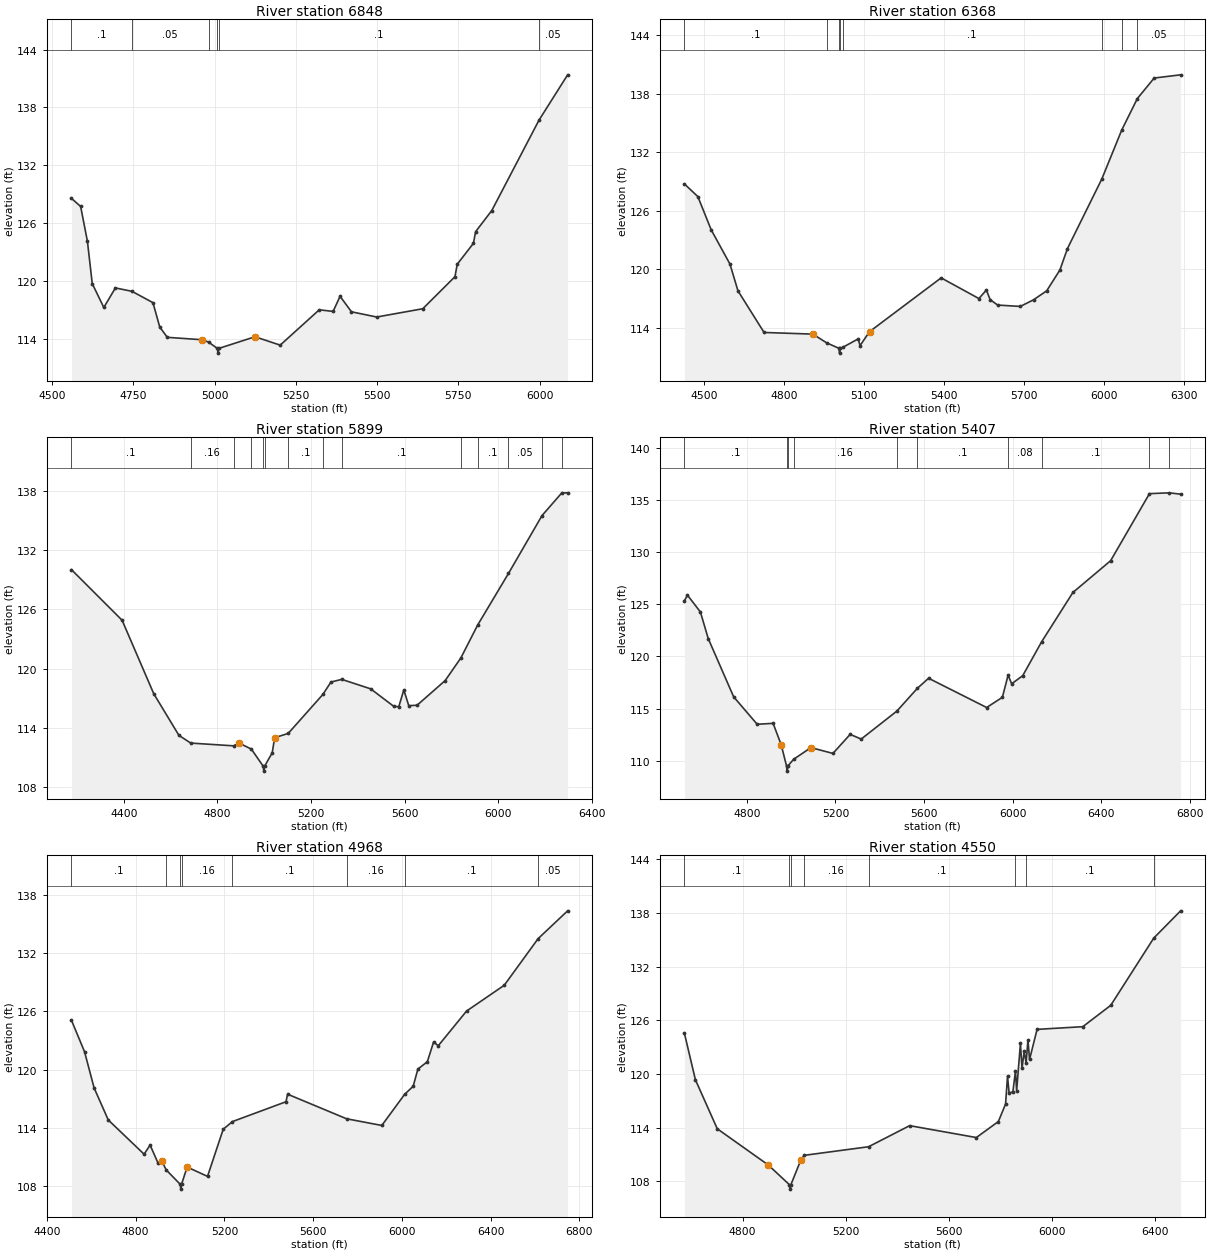
Type RM Length L Ch R = 1 ,6848    ,480,480,480
BEGIN DESCRIPTION:
UNT036 IN SPCR 13.0
END DESCRIPTION:
XS GIS Cut Line= 3
       2250237.7     13318046.84      2249887.72     13317796.85
       2249087.7     13317046.84
#Sta/Elev= 30
  4559.3  128.56  4587.5  127.72  4608.4   124.1  4623.2  119.71  4658.8  117.23
  4694.5  119.26  4745.3  118.91    4810  117.73  4830.9   115.2  4854.2  114.13
  4961.1  113.88    4981  113.64  5007.6  112.99  5010.4  112.49  5013.6  112.99
    5124  114.19  5201.6  113.32  5321.8  116.99  5364.3  116.82  5385.8  118.39
  5420.9  116.78  5498.6  116.24  5640.3   117.1  5739.4  120.43  5746.3  121.72
  5796.1  123.89  5802.9   125.1  5852.7   127.3  5997.9  136.68    6086  141.39
#Mann= 6 ,-1 , 0
  4559.3      .1       0  4745.3     .05       0    4981      .1       0
  5007.6     .07       0  5013.6      .1       0  5997.9     .05       0
Bank Sta=4961.1,5124
XS Rating Curve= 0 ,0
Exp/Cntr=0.3,0.1

Type RM Length L Ch R = 1 ,6368    ,469,469,469
BEGIN DESCRIPTION:
UNT036 IN SPCR 12.0
END DESCRIPTION:
XS GIS Cut Line= 3
      2250287.72     13318046.89      2250237.72     13317446.85
      2249335.91      13316568.5
#Sta/Elev= 30
  4426.8  128.75    4477  127.46  4527.2  124.04  4597.4  120.54  4627.5  117.79
  4725.4  113.52  4908.5  113.35  4959.9  112.46  5005.8   111.9  5008.6   111.4
  5011.8   111.9  5020.3  111.99  5078.4  112.86  5085.4  112.17  5120.9   113.6
  5389.6  119.12  5531.1     117  5559.4  117.87  5573.3  116.89  5601.6  116.33
  5686.5  116.19  5736.1  116.87  5785.5  117.79  5835.1  119.93  5863.4  122.13
  5992.2  129.26  6067.2   134.3  6125.4  137.51  6188.6  139.62  6287.8  139.95
#Mann= 8 ,-1 , 0
  4426.8      .1       0  4959.9     .16       0  5005.8     .07       0
  5011.8     .16       0  5020.3      .1       0  5992.2     .05       0
  6067.2      .1       0  6125.4     .05       0
Bank Sta=4908.5,5120.9
XS Rating Curve= 0 ,0
Exp/Cntr=0.3,0.1

Type RM Length L Ch R = 1 ,5899    ,492,492,492
BEGIN DESCRIPTION:
UNT036 IN SPCR 11.0
END DESCRIPTION:
XS GIS Cut Line= 3
      2250787.74      13317896.9      2250487.72     13317096.85
      2249572.67     13316221.89
#Sta/Elev= 30
  4176.5  130.01  4392.8  124.89  4528.1  117.45  4635.8  113.23  4686.2  112.45
    4870  112.17  4892.1  112.46  4945.3  111.84  4995.9  110.11  4998.7  109.61
  5001.9  110.11  5034.4  111.46  5044.9  112.99  5102.9  113.43  5250.8  117.37
  5285.5  118.63  5331.7   118.9  5455.4  117.94  5554.4  116.16  5575.5  116.14
  5596.9  117.83    5618  116.24  5653.5  116.28  5773.7  118.78  5840.7  121.07
  5912.2  124.39  6044.3  129.63  6187.7  135.49  6271.6  137.77    6297  137.79
#Mann= 14 ,-1 , 0
  4176.5      .1       0  4686.2     .16       0    4870      .1       0
  4945.3     .16       0  4995.9     .07       0  5001.9     .16       0
  5102.9      .1       0  5250.8     .16       0  5331.7      .1       0
  5840.7     .08       0  5912.2      .1       0  6044.3     .05       0
  6187.7      .1       0  6271.6     .05       0
Bank Sta=4892.1,5044.9
XS Rating Curve= 0 ,0
Exp/Cntr=0.3,0.1

Type RM Length L Ch R = 1 ,5407    ,439,439,439
BEGIN DESCRIPTION:
UNT036 IN SPCR 10.0
END DESCRIPTION:
XS GIS Cut Line= 3
      2251237.71     13317496.84      2250937.72     13317096.85
      2249655.36     13315922.67
#Sta/Elev= 30
  4518.8  125.36  4532.3  125.89  4590.7  124.28  4626.1  121.72  4740.7  116.13
  4846.9  113.49  4918.8  113.58  4955.2  111.53  4979.3  109.49  4982.1  108.99
  4985.3  109.49  5011.5  110.13  5089.4  111.25  5188.7  110.69  5266.4  112.52
  5316.3  112.07  5477.4  114.76  5569.9  116.95  5620.3  117.91  5882.4   115.1
  5953.3  116.08  5979.2  118.21  5995.2  117.38  6045.2  118.16  6130.3  121.41
  6271.5  126.15  6441.7   129.2  6616.9  135.64  6706.5  135.72  6757.5  135.59
#Mann= 10 ,-1 , 0
  4518.8      .1       0  4979.3     .07       0  4985.3      .1       0
  5011.5     .16       0  5477.4     .08       0  5569.9      .1       0
  5979.2     .08       0  6130.3      .1       0  6616.9     .05       0
  6706.5      .1       0
Bank Sta=4955.2,5089.4
XS Rating Curve= 0 ,0
Exp/Cntr=0.3,0.1

Type RM Length L Ch R = 1 ,4968    ,418,418,418
BEGIN DESCRIPTION:
UNT036 IN SPCR 9.0
END DESCRIPTION:
XS GIS Cut Line= 3
      2251537.73     13317246.87      2251287.72     13316846.85
      2250079.11     13315561.71
#Sta/Elev= 30
  4510.9  125.09  4569.9  121.83  4612.9   118.1  4676.6  114.79  4838.2  111.25
  4865.3  112.19  4901.8  110.29  4917.2  110.55  4938.1  109.62  5000.9  108.14
  5003.6  107.64  5006.9  108.14  5032.2  109.92    5124  108.96  5194.8  113.83
  5236.3  114.62  5477.6  116.67  5484.9  117.45  5750.7  114.91  5909.4  114.22
  6011.8  117.42    6051  118.28    6072  120.05  6114.5   120.8  6142.8  122.84
  6163.9  122.46  6291.3  126.04  6461.3  128.71    6614  133.53  6746.8   136.4
#Mann= 8 ,-1 , 0
  4510.9      .1       0  4938.1     .16       0  5000.9     .07       0
  5006.9     .16       0  5236.3      .1       0  5750.7     .16       0
  6011.8      .1       0    6614     .05       0
Bank Sta=4917.2,5032.2
XS Rating Curve= 0 ,0
Exp/Cntr=0.3,0.1

Type RM Length L Ch R = 1 ,4550    ,483,483,483
BEGIN DESCRIPTION:
UNT036 IN SPCR 8.0
END DESCRIPTION:
XS GIS Cut Line= 3
      2251787.73     13316796.86      2251487.72     13316496.85
      2250593.29      13315291.3
#Sta/Elev= 30
  4574.1  124.52  4616.5  119.35  4701.4  113.86  4899.4  109.81  4981.2  107.61
    4984  107.11  4987.2  107.61  5026.5  110.42  5038.7  110.89  5288.5  111.85
    5448  114.21  5706.8  112.88  5792.3  114.67  5820.2  116.63  5827.8  119.74
    5834  117.86  5848.6  117.99  5858.7  120.33  5863.2  118.12  5877.9   123.4
  5884.1  120.63  5892.5  122.55    5900  121.22  5907.1  123.81  5913.3  121.61
  5942.5  124.98  6119.9  125.28  6228.4  127.67  6395.3  135.19  6499.5  138.24
#Mann= 8 ,-1 , 0
  4574.1      .1       0  4981.2     .07       0  4987.2      .1       0
  5038.7     .16       0  5288.5      .1       0  5858.7     .05       0
    5900      .1       0  6395.3     .05       0
Bank Sta=4899.4,5026.5
XS Rating Curve= 0 ,0
Exp/Cntr=0.3,0.1