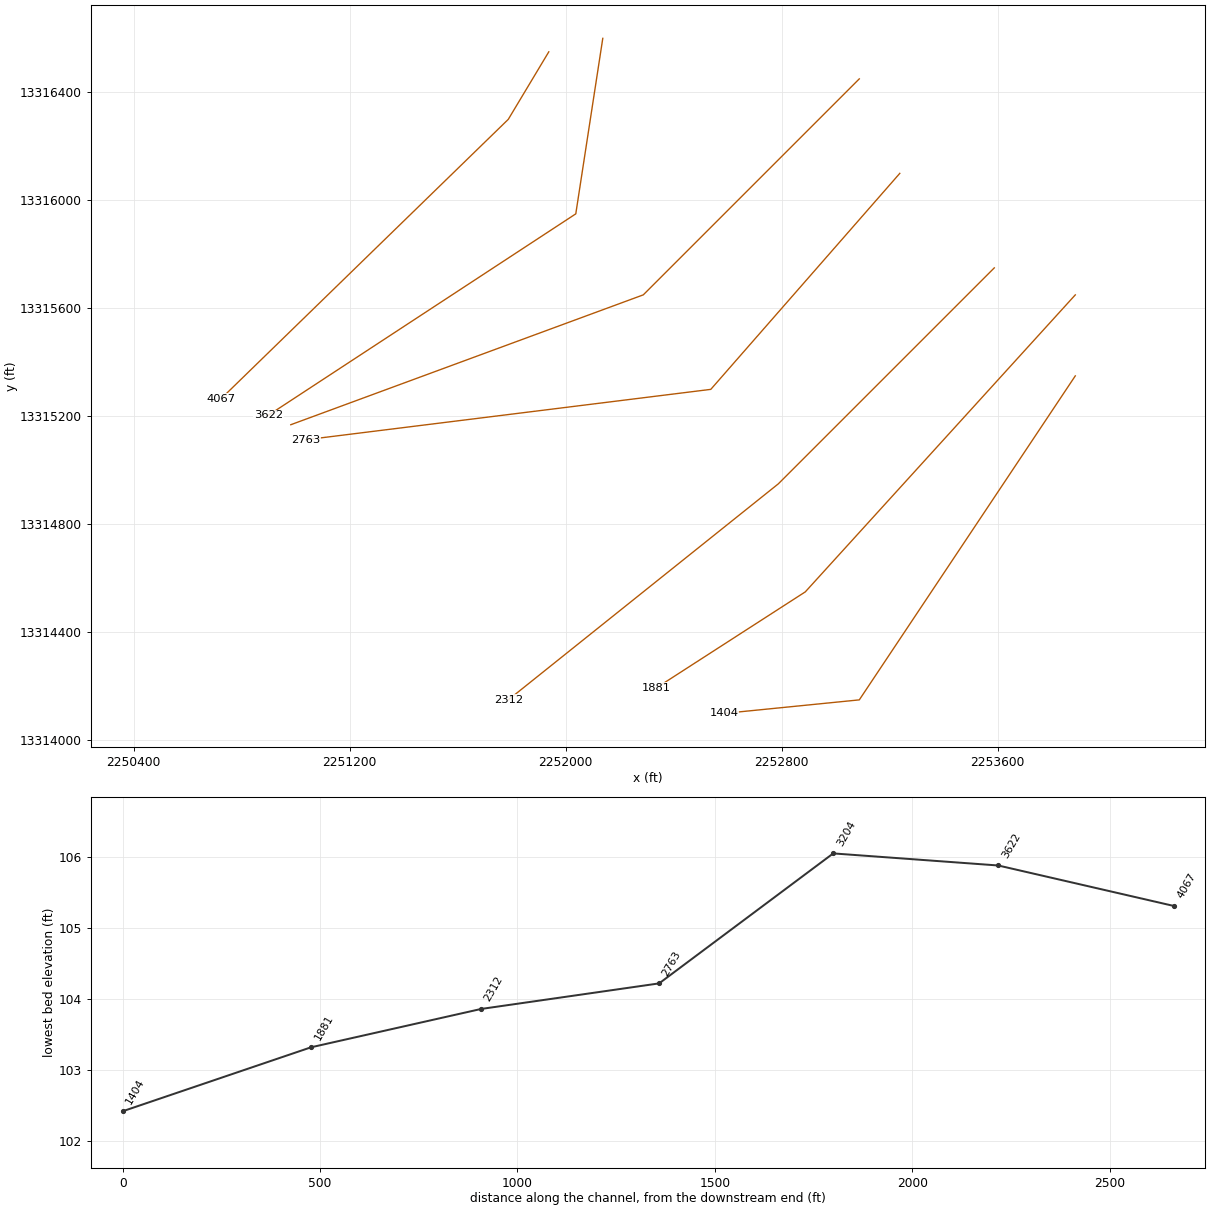
HEC-RAS study UNT036 IN SPCR.prj: UNT036 IN SPCR Base Level Engineering

--- UNT036 IN SPCR.g01 (geometry) --- (continued)

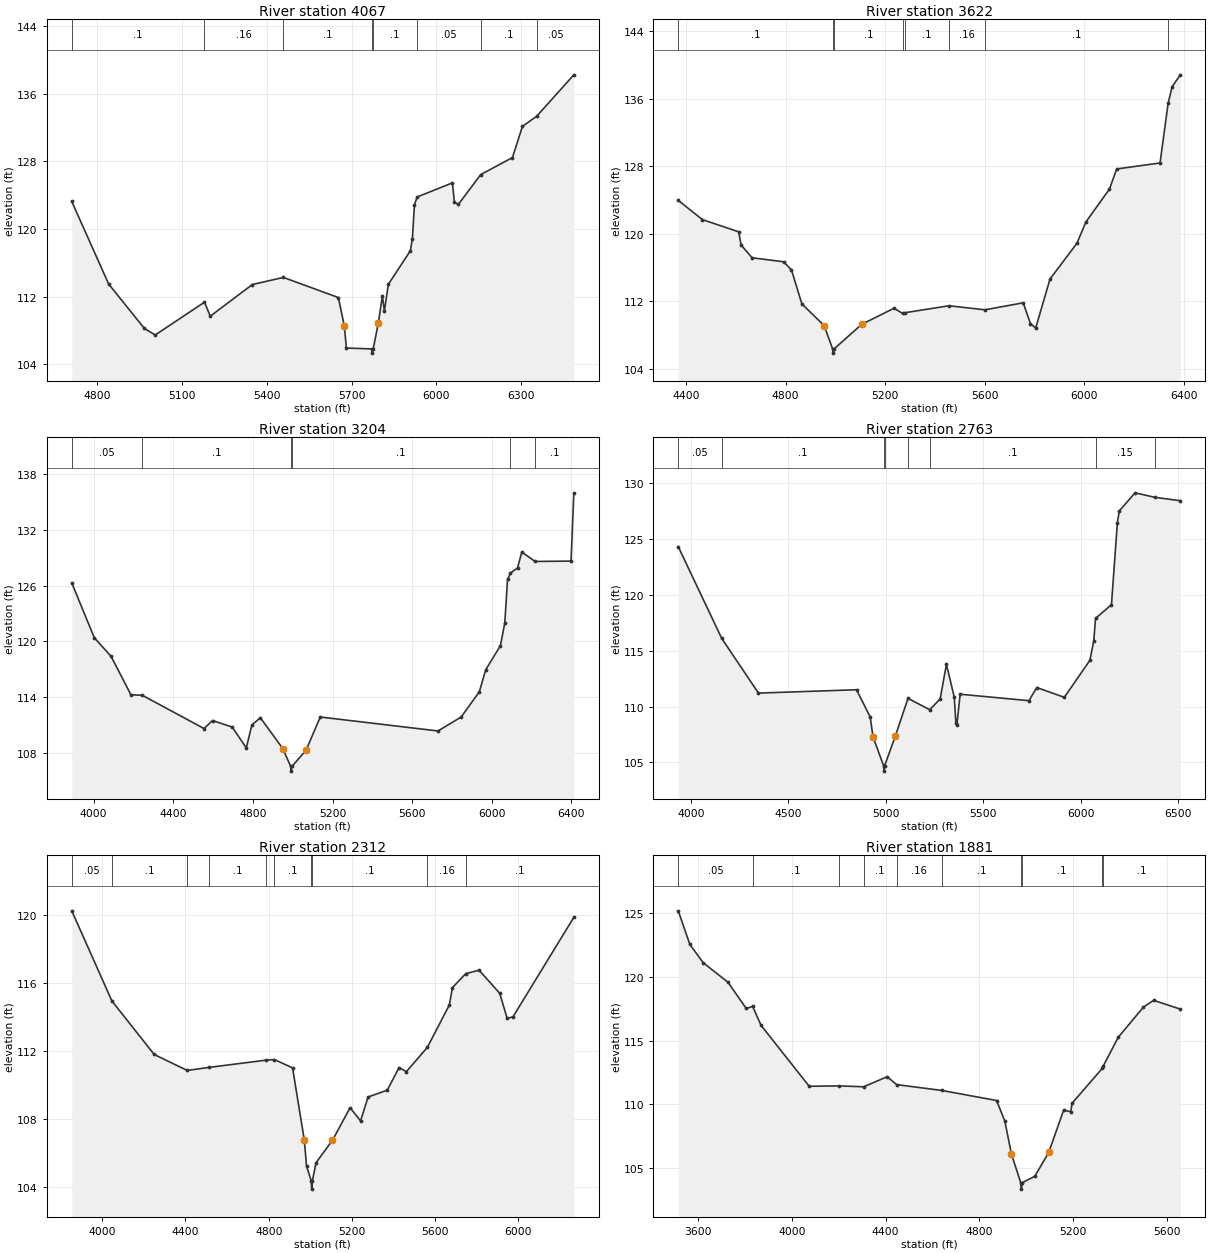
Type RM Length L Ch R = 1 ,4067    ,445,445,445
BEGIN DESCRIPTION:
UNT036 IN SPCR 7.0
END DESCRIPTION:
XS GIS Cut Line= 3
      2251937.74     13316546.88      2251787.72     13316296.85
      2250724.81     13315262.95
#Sta/Elev= 30
  4711.4  123.26  4841.7  113.49    4968  108.23  5006.5  107.46  5180.4  111.34
  5200.9  109.68  5349.6  113.43  5459.3  114.27  5653.6  111.89  5674.7  108.51
  5681.9  105.91  5770.8  105.81  5773.5  105.31  5776.8  105.81  5795.1  108.92
  5809.2  112.11  5816.2  110.29  5830.3  113.46  5908.2  117.43  5915.2  118.87
  5922.4  122.84  5931.8  123.79  6056.7  125.46  6063.7  123.16  6077.8  122.92
  6156.7  126.44  6268.9  128.46  6304.1  132.14  6354.8  133.36  6485.8  138.25
#Mann= 8 ,-1 , 0
  4711.4      .1       0  5180.4     .16       0  5459.3      .1       0
  5770.8     .07       0  5776.8      .1       0  5931.8     .05       0
  6156.7      .1       0  6354.8     .05       0
Bank Sta=5674.7,5795.1
XS Rating Curve= 0 ,0
Exp/Cntr=0.3,0.1

Type RM Length L Ch R = 1 ,3622    ,418,418,418
BEGIN DESCRIPTION:
UNT036 IN SPCR 6.0
END DESCRIPTION:
XS GIS Cut Line= 3
      2252137.73      13316596.9      2252037.72     13315946.85
      2250899.52     13315201.18
#Sta/Elev= 30
  4368.4  123.97  4465.8  121.69  4611.3  120.25  4621.4  118.67  4665.7  117.17
  4792.1   116.7  4823.7  115.73  4865.5  111.71  4955.3  109.13  4988.9  106.38
  4991.7  105.88  4994.9  106.38    5106  109.29  5235.6  111.19  5270.1  110.59
  5278.3  110.66  5457.1  111.49    5601  111.01  5755.3  111.84  5784.3  109.38
  5805.4  108.85  5862.9  114.65  5971.2  118.89  6007.4  121.42    6102  125.31
    6131  127.69  6305.3   128.4    6338   135.5  6354.1  137.44  6386.8  138.84
#Mann= 8 ,-1 , 0
  4368.4      .1       0  4988.9     .07       0  4994.9      .1       0
  5270.1     .16       0  5278.3      .1       0  5457.1     .16       0
    5601      .1       0    6338     .05       0
Bank Sta=4955.3,5106
XS Rating Curve= 0 ,0
Exp/Cntr=0.3,0.1

Type RM Length L Ch R = 1 ,3204    ,441,441,441
BEGIN DESCRIPTION:
UNT036 IN SPCR 5.0
END DESCRIPTION:
XS GIS Cut Line= 3
      2253087.69     13316446.82      2252287.72     13315646.85
      2250982.22     13315165.91
#Sta/Elev= 30
    3890  126.29  4003.1   120.4  4087.9  118.38  4186.9  114.27  4244.9   114.2
  4554.6  110.63  4597.1  111.49  4696.1  110.79  4766.8  108.55  4795.1  111.02
  4837.5  111.79  4950.6  108.47    4990  106.55  4992.8  106.05    4996  106.55
    5067  108.29  5138.6  111.87    5730  110.37  5846.5  111.87  5937.9  114.59
  5969.8  116.95  6043.7  119.54  6065.7  121.99  6079.4  126.66  6094.3  127.35
  6129.7   127.9    6151  129.61    6218   128.6  6398.4  128.64  6412.6  135.98
#Mann= 6 ,-1 , 0
    3890     .05       0  4244.9      .1       0    4990     .07       0
    4996      .1       0  6094.3     .15       0    6218      .1       0
Bank Sta=4950.6,5067
XS Rating Curve= 0 ,0
Exp/Cntr=0.3,0.1

Type RM Length L Ch R = 1 ,2763    ,451,451,451
BEGIN DESCRIPTION:
UNT036 IN SPCR 4.0
END DESCRIPTION:
XS GIS Cut Line= 3
      2253237.69     13316096.82      2252537.72     13315296.85
      2251037.36     13315110.19
#Sta/Elev= 30
  3935.1  124.33  4157.8  116.12  4346.5  111.21  4849.5  111.51  4919.8  109.06
    4934  107.29  4987.9  104.72  4990.7  104.22  4993.9  104.72  5048.5  107.36
  5113.5  110.74  5224.8  109.72  5278.4  110.69  5310.5  113.79  5350.8  110.84
  5359.2  108.49  5364.2  108.39    5381  111.11  5733.7  110.53    5774  111.71
  5915.1  110.83  6046.1  114.14  6066.2  115.88  6075.2   117.9  6156.9  119.13
  6187.2  126.47  6197.2  127.53  6277.9  129.15  6378.4  128.75    6510  128.44
#Mann= 8 ,-1 , 0
  3935.1     .05       0  4157.8      .1       0  4987.9     .07       0
  4993.9      .1       0  5113.5     .05       0  5224.8      .1       0
  6075.2     .15       0  6378.4      .1       0
Bank Sta=4934,5048.5
XS Rating Curve= 0 ,0
Exp/Cntr=0.3,0.1

Type RM Length L Ch R = 1 ,2312    ,431,431,431
BEGIN DESCRIPTION:
UNT036 IN SPCR 3.0
END DESCRIPTION:
XS GIS Cut Line= 3
      2253587.73     13315746.86      2252787.72     13314946.85
      2251787.73     13314146.86
#Sta/Elev= 30
    3854  120.23  4046.7  114.93    4250  111.78  4408.9  110.84  4513.1  111.02
  4789.2  111.45  4827.9  111.48  4914.7  110.99  4971.2  106.74  4981.8  105.22
    5004  104.36  5006.7  103.86    5010  104.36  5027.8  105.42  5106.2  106.73
  5191.1  108.65  5241.5  107.87  5277.5  109.28  5369.6  109.68  5426.4  111.01
  5461.6  110.77  5562.3   112.2  5668.1   114.7  5682.5  115.71  5746.3  116.53
  5810.6  116.74  5909.8  115.38  5945.8   113.9  5973.9     114    6266  119.85
#Mann= 10 ,-1 , 0
    3854     .05       0  4046.7      .1       0  4408.9     .16       0
  4513.1      .1       0  4789.2     .16       0  4827.9      .1       0
    5004     .07       0    5010      .1       0  5562.3     .16       0
  5746.3      .1       0
Bank Sta=4971.2,5106.2
XS Rating Curve= 0 ,0
Exp/Cntr=0.3,0.1

Type RM Length L Ch R = 1 ,1881    ,477,477,477
BEGIN DESCRIPTION:
UNT036 IN SPCR 2.0
END DESCRIPTION:
XS GIS Cut Line= 3
      2253887.71     13315646.84      2252887.72     13314546.85
      2252335.58     13314190.94
#Sta/Elev= 30
  3514.6  125.21  3564.2  122.57    3621  121.13  3727.1  119.59  3804.8  117.53
  3832.1  117.69  3868.3   116.2  4073.7  111.41  4200.4  111.44  4306.4  111.37
  4406.5  112.16  4447.1  111.54  4640.6  111.08  4873.8  110.29  4908.9  108.67
  4937.3  106.07  4976.9  103.82  4979.6  103.32  4982.9  103.82  5036.9  104.33
  5096.4  106.21  5159.9  109.53  5190.3  109.41  5196.2  110.08  5324.6  112.81
  5329.1     113  5392.9  115.26  5500.9  117.64  5544.1  118.17  5658.1  117.48
#Mann= 10 ,-1 , 0
  3514.6     .05       0  3832.1      .1       0  4200.4     .16       0
  4306.4      .1       0  4447.1     .16       0  4640.6      .1       0
  4976.9     .07       0  4982.9      .1       0  5324.6     .16       0
  5329.1      .1       0
Bank Sta=4937.3,5096.4
XS Rating Curve= 0 ,0
Exp/Cntr=0.3,0.1

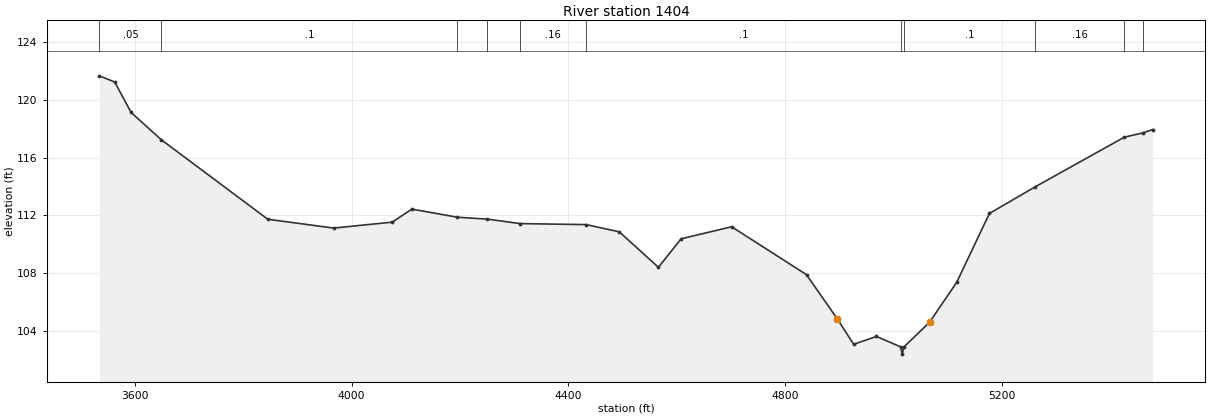
Type RM Length L Ch R = 1 ,1404    ,0,0,0
BEGIN DESCRIPTION:
UNT036 IN SPCR 1.0
END DESCRIPTION:
XS GIS Cut Line= 3
      2253887.71     13315346.84      2253087.72     13314146.85
      2252587.71     13314096.85
#Sta/Elev= 30
  3534.4  121.65  3562.9  121.22    3593  119.12  3648.9  117.23  3845.4  111.74
    3967  111.13  4075.2  111.54  4111.3  112.44  4195.2  111.88  4250.7  111.75
  4310.9  111.44  4433.1  111.37  4494.4  110.87  4566.5  108.42  4608.5  110.39
  4701.7  111.22  4839.9  107.91    4897  104.84    4927   103.1  4969.1  103.64
  5013.8  102.92  5016.5  102.42  5019.8  102.92    5067  104.62  5117.3  107.39
  5177.6  112.14  5261.1  113.96  5426.6  117.41  5461.2  117.71  5479.1  117.94
#Mann= 11 ,-1 , 0
  3534.4     .05       0  3648.9      .1       0  4195.2     .16       0
  4250.7      .1       0  4310.9     .16       0  4433.1      .1       0
  5013.8     .07       0  5019.8      .1       0  5261.1     .16       0
  5426.6      .1       0  5461.2     .16       0
Bank Sta=4897,5067
XS Rating Curve= 0 ,0
Exp/Cntr=0.3,0.1

Chan Stop Cuts=-1
Use User Specified Reach Order=0
Composite Channel Slope=5