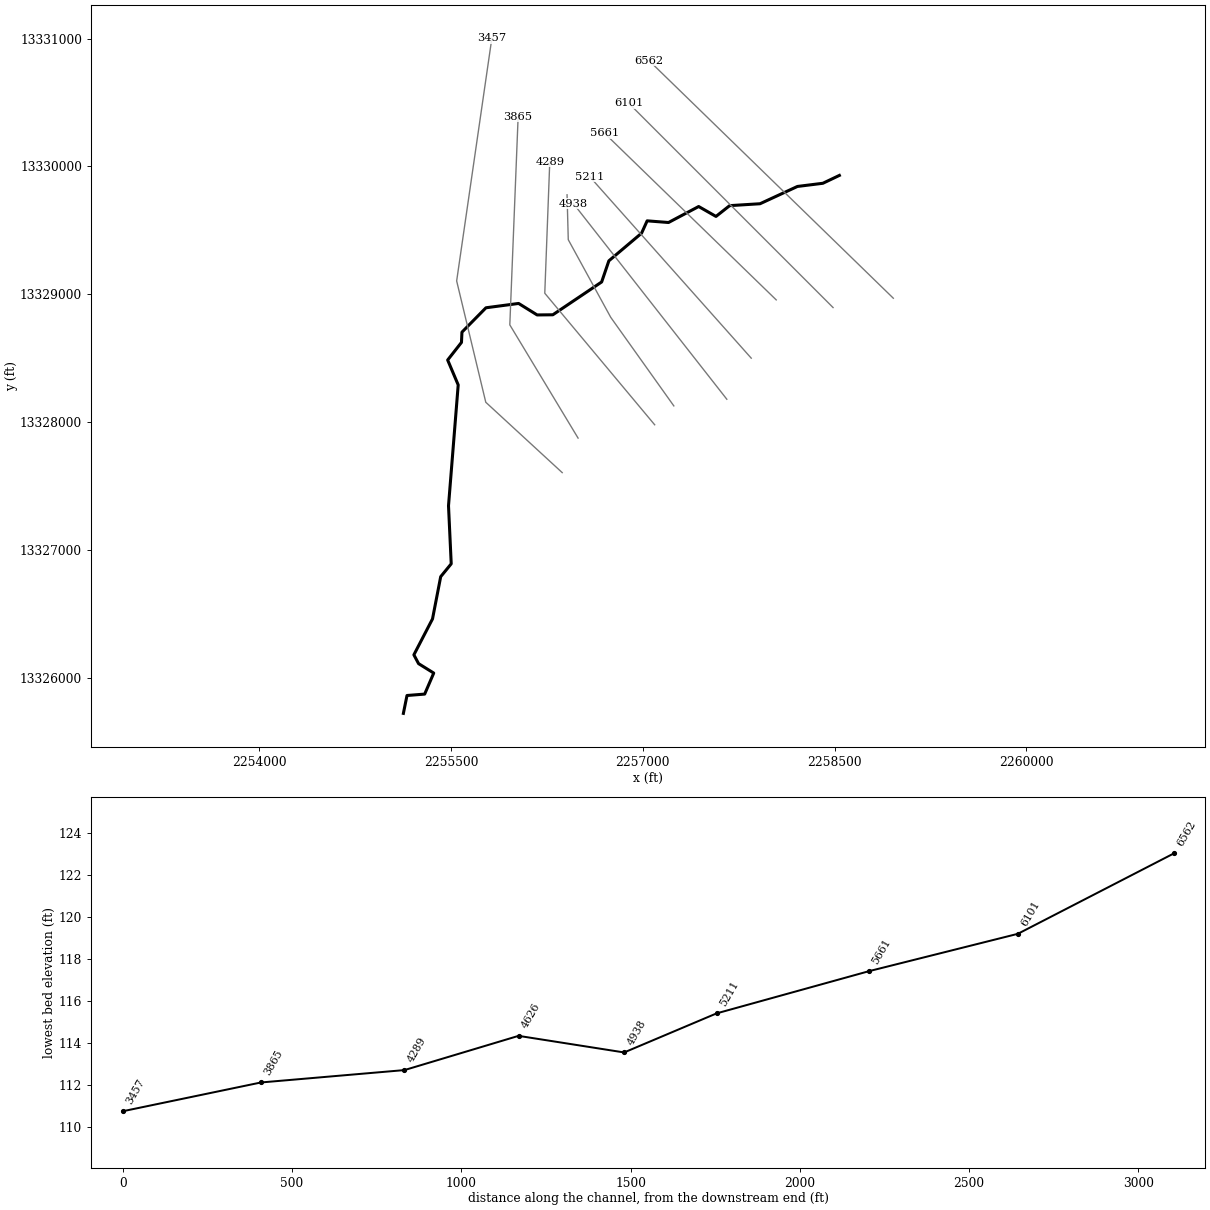
--- UNT037 IN SPCR.prj (project) ---

Proj Title=UNT037 IN SPCR Base Level Engineering
Current Plan=p01
Default Exp/Contr=0.3,0.1
English Units
Geom File=g01
Flow File=f01
Plan File=p01
BEGIN DESCRIPTION:
UNT037 IN SPCR
END DESCRIPTION:

--- UNT037 IN SPCR.p01 (plan) ---

Plan Title=Multiple Run
Short Identifier=Multiple
Geom File=g01
Flow File=f01
Subcritical Flow
K Sum by GR= 0
Std Step Tol= 0.01
Critical Tol= 0.01
Num of Std Step Trials= 20
Max Error Tol= 0.3
Flow Tol Ratio= 0.001
Split Flow NTrial= 30
Split Flow Tol= 0.02
Split Flow Ratio= 0.02
Log Output Level= 0
Friction Slope Method= 1
Unsteady Friction Slope Method= 2
Unsteady Bridges Friction Slope Method= 1
Parabolic Critical Depth
Global Vel Dist=  1 , 1 , 1
Global Log Level= 0
CheckData=True
Encroach Param= -1, 0, 0, 0
BEGIN DESCRIPTION:
Multiple Run
END DESCRIPTION:

--- UNT037 IN SPCR.f01 (steady flow) ---

Flow Title=Multiple
Number of Profiles=7
Profile Names=10-year,25-year,50-year,1pct_min,100-year,1pct_plu,500-year
River Rch & RM= UNT037 IN SPCR,Reach-1,6562
     284     394     486     440     595     805     906
Boundary for River Rch & Prof#=UNT037 IN SPCR,Reach-1,1
Up Type=0
Dn Type=3
Dn Slope=0.005
Boundary for River Rch & Prof#=UNT037 IN SPCR,Reach-1,2
Up Type=0
Dn Type=3
Dn Slope=0.005
Boundary for River Rch & Prof#=UNT037 IN SPCR,Reach-1,3
Up Type=0
Dn Type=3
Dn Slope=0.005
Boundary for River Rch & Prof#=UNT037 IN SPCR,Reach-1,4
Up Type=0
Dn Type=3
Dn Slope=0.005
Boundary for River Rch & Prof#=UNT037 IN SPCR,Reach-1,5
Up Type=0
Dn Type=3
Dn Slope=0.005
Boundary for River Rch & Prof#=UNT037 IN SPCR,Reach-1,6
Up Type=0
Dn Type=3
Dn Slope=0.005
Boundary for River Rch & Prof#=UNT037 IN SPCR,Reach-1,7
Up Type=0
Dn Type=3
Dn Slope=0.005

--- UNT037 IN SPCR.g01 (geometry) ---

Geom Title=Existing Conditions

River Reach=UNT037 IN SPCR,Reach-1
Reach XY= 30
      2258537.08     13329930.24      2258407.91     13329868.66
      2258208.98     13329843.84      2257916.68     13329708.67
      2257678.93     13329693.77      2257572.10     13329609.47
      2257436.75     13329686.91      2257200.86     13329561.93
      2257033.89     13329574.94      2256990.14     13329478.31
      2256734.42     13329262.22      2256678.02     13329096.88
      2256296.29     13328840.28      2256173.47     13328839.09
      2256028.73     13328928.96      2255773.36     13328895.14
      2255585.54     13328704.50      2255581.85     13328624.28
      2255473.78     13328486.62      2255556.22     13328291.82
      2255480.41     13327346.79      2255501.64     13326892.89
      2255419.32     13326792.27      2255355.37     13326462.12
      2255209.64     13326181.16      2255246.28     13326112.25
      2255364.86     13326038.44      2255294.01     13325874.05
      2255155.81     13325863.07      2255127.54     13325723.26

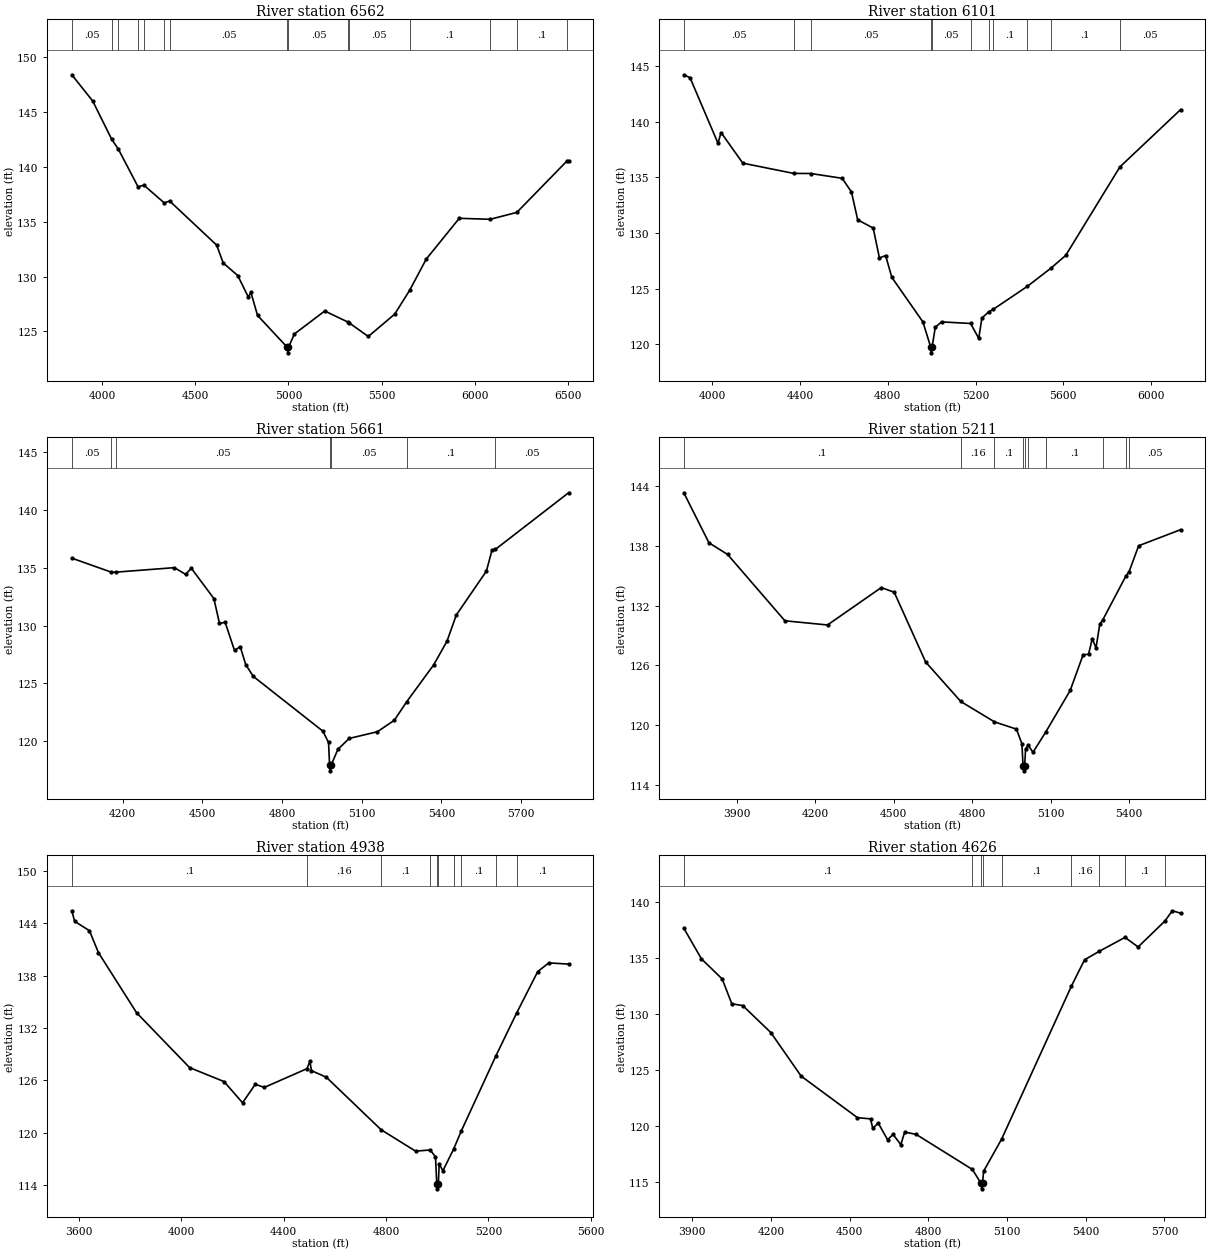
Type RM Length L Ch R = 1,6562,461,461,461
BEGIN DESCRIPTION:
UNT037 IN SPCR 14.0
END DESCRIPTION:
XS GIS Cut Line= 2
      2258958.95     13328969.77      2257049.21     13330827.42
#Sta/Elev= 30
  3837.9  148.37  3949.9  145.98  4051.7  142.50  4087.5  141.60  4192.8  138.18
  4224.9  138.31  4333.9  136.70  4362.3  136.88  4614.6  132.86  4649.9  131.23
  4727.8  130.09  4784.4  128.13  4798.5  128.55  4833.8  126.46  4993.6  123.55
  4996.3  123.05  4999.6  123.55  5031.8  124.77  5194.4  126.86  5321.5  125.83
  5323.8  125.80  5427.9  124.54  5569.4  126.57  5649.6  128.74  5738.9  131.59
  5915.9  135.30  6081.6  135.21  6224.7  135.84  6495.2  140.55  6502.1  140.51
#Mann=15,-1,0
  3837.9    0.05       0  4051.7     0.1       0  4087.5    0.05       0
  4192.8     0.1       0  4224.9    0.05       0  4333.9     0.1       0
  4362.3    0.05       0  4993.6   0.035       0  4999.6    0.05       0
  5321.5     0.1       0  5323.8    0.05       0  5649.6     0.1       0
  6081.6    0.05       0  6224.7     0.1       0  6495.2    0.05       0
Bank Sta=4993.6,4999.6
Exp/Cntr=0.3,0.1

Type RM Length L Ch R = 1,6101,440,440,440
BEGIN DESCRIPTION:
UNT037 IN SPCR 13.0
END DESCRIPTION:
XS GIS Cut Line= 3
      2258487.73     13328896.84      2257687.72     13329696.85
      2256887.69     13330496.88
#Sta/Elev= 30
  3871.1  144.20  3899.4  143.94  4026.7  138.05  4040.8  139.01  4139.8  136.26
  4371.3  135.34  4449.5  135.33  4592.4  134.90  4634.8  133.67  4663.1  131.17
  4733.8  130.43  4762.1  127.74  4790.4  127.96  4818.6  126.00  4960.1  122.00
  4996.0  119.72  4998.7  119.22  5002.0  119.72  5016.6  121.52  5044.9  122.00
  5177.3  121.86  5214.6  120.52  5228.8  122.34  5259.0  122.89  5280.8  123.13
  5435.7  125.19  5542.3  126.81  5610.6  127.97  5857.4  135.92  6133.9  141.07
#Mann=11,-1,0
  3871.1    0.05       0  4371.3     0.1       0  4449.5    0.05       0
  4996.0    0.03       0  5002.0    0.05       0  5177.3     0.1       0
  5259.0    0.05       0  5280.8     0.1       0  5435.7    0.05       0
  5542.3     0.1       0  5857.4    0.05       0
Bank Sta=4996,5002
Exp/Cntr=0.3,0.1

Type RM Length L Ch R = 1,5661,450,450,450
BEGIN DESCRIPTION:
UNT037 IN SPCR 12.0
END DESCRIPTION:
XS GIS Cut Line= 2
      2258043.17     13328956.73      2256702.35     13330258.50
#Sta/Elev= 30
  4009.3  135.82  4157.7  134.61  4174.0  134.61  4395.1  135.00  4437.5  134.42
  4458.8  134.95  4543.7  132.33  4564.8  130.18  4586.1  130.28  4621.4  127.84
  4642.7  128.18  4663.8  126.61  4692.1  125.60  4953.7  120.87  4975.1  119.89
  4979.0  117.94  4981.8  117.44  4985.0  117.94  5010.3  119.30  5052.8  120.24
  5159.0  120.82  5222.5  121.81  5269.1  123.41  5371.0  126.61  5420.6  128.64
  5455.8  130.91  5569.0  134.70  5590.3  136.54  5602.8  136.58  5878.1  141.47
#Mann=7,-1,0
  4009.3    0.05       0  4157.7     0.1       0  4174.0    0.05       0
  4979.0    0.03       0  4985.0    0.05       0  5269.1     0.1       0
  5602.8    0.05       0
Bank Sta=4979,4985
Exp/Cntr=0.3,0.1

Type RM Length L Ch R = 1,5211,273,273,273
BEGIN DESCRIPTION:
UNT037 IN SPCR 11.0
END DESCRIPTION:
XS GIS Cut Line= 2
      2257847.81     13328501.05      2256584.84     13329920.26
#Sta/Elev= 30
  3697.3  143.30  3793.6  138.28  3864.7  137.12  4083.8  130.47  4246.9  130.05
  4452.5  133.80  4501.9  133.33  4622.3  126.33  4756.5  122.38  4885.3  120.34
  4969.3  119.61  4990.2  118.16  4994.7  115.93  4997.5  115.43  5000.7  115.93
  5004.4  117.63  5014.0  118.01  5032.8  117.29  5082.1  119.35  5175.0  123.49
  5224.3  127.06  5245.2  127.12  5259.4  128.67  5273.7  127.75  5287.9  130.10
  5300.2  130.59  5387.8  134.95  5400.1  135.39  5436.7  137.99  5597.1  139.60
#Mann=10,-1,0
  3697.3     0.1       0  4756.5    0.16       0  4885.3     0.1       0
  4994.7    0.07       0  5000.7     0.1       0  5014.0    0.12       0
  5082.1     0.1       0  5300.2    0.16       0  5387.8     0.1       0
  5400.1    0.05       0
Bank Sta=4994.7,5000.7
Exp/Cntr=0.3,0.1

Type RM Length L Ch R = 1,4938,312,312,312
BEGIN DESCRIPTION:
UNT037 IN SPCR 10.0
END DESCRIPTION:
XS GIS Cut Line= 2
      2257656.88     13328179.82      2256458.98     13329707.58
#Sta/Elev= 30
  3572.0  145.43  3583.0  144.22  3640.8  143.15  3676.1  140.63  3825.3  133.74
  4032.3  127.46  4167.0  125.86  4239.3  123.43  4289.0  125.55  4324.3  125.19
  4491.0  127.34  4502.4  128.17  4508.7  127.11  4566.6  126.36  4780.5  120.35
  4915.2  117.89  4972.4  118.02  4993.3  117.25  4998.4  114.07  5001.1  113.57
  5004.4  114.07  5007.7  116.43  5022.2  115.64  5064.1  118.12  5094.9  120.25
  5229.6  128.82  5310.2  133.70  5392.8  138.46  5436.2  139.46  5513.4  139.32
#Mann=10,-1,0
  3572.0     0.1       0  4491.0    0.16       0  4780.5     0.1       0
  4972.4    0.12       0  4998.4    0.07       0  5004.4    0.12       0
  5064.1    0.16       0  5094.9     0.1       0  5229.6    0.16       0
  5310.2     0.1       0
Bank Sta=4998.4,5004.4
Exp/Cntr=0.3,0.1

Type RM Length L Ch R = 1,4626,337,337,337
BEGIN DESCRIPTION:
Mapping XS 3ef7fadd
END DESCRIPTION:
XS GIS Cut Line= 4
      2257242.37     13328127.81      2256749.03     13328820.37
      2256416.98     13329427.55      2256407.49     13329778.57
#Sta/Elev= 30
  3868.1  137.64  3935.4  134.90  4014.3  133.11  4051.0  130.89  4092.8  130.73
  4199.8  128.32  4315.3  124.43  4529.9  120.72  4579.7  120.61  4588.3  119.77
  4609.2  120.23  4644.8  118.75  4665.7  119.22  4695.2  118.31  4710.0  119.43
  4753.3  119.23  4968.1  116.09  5000.8  114.86  5003.5  114.36  5006.8  114.86
  5010.7  115.93  5079.6  118.81  5345.1  132.45  5395.5  134.82  5450.9  135.57
  5549.6  136.82  5599.8  135.97  5701.8  138.28  5729.9  139.20  5761.6  138.99
#Mann=9,-1,0
  3868.1     0.1       0  4968.1    0.12       0  5000.8    0.07       0
  5006.8    0.12       0  5079.6     0.1       0  5345.1    0.16       0
  5450.9    0.05       0  5549.6     0.1       0  5701.8    0.05       0
Bank Sta=5000.8,5006.8
Exp/Cntr=0.3,0.1

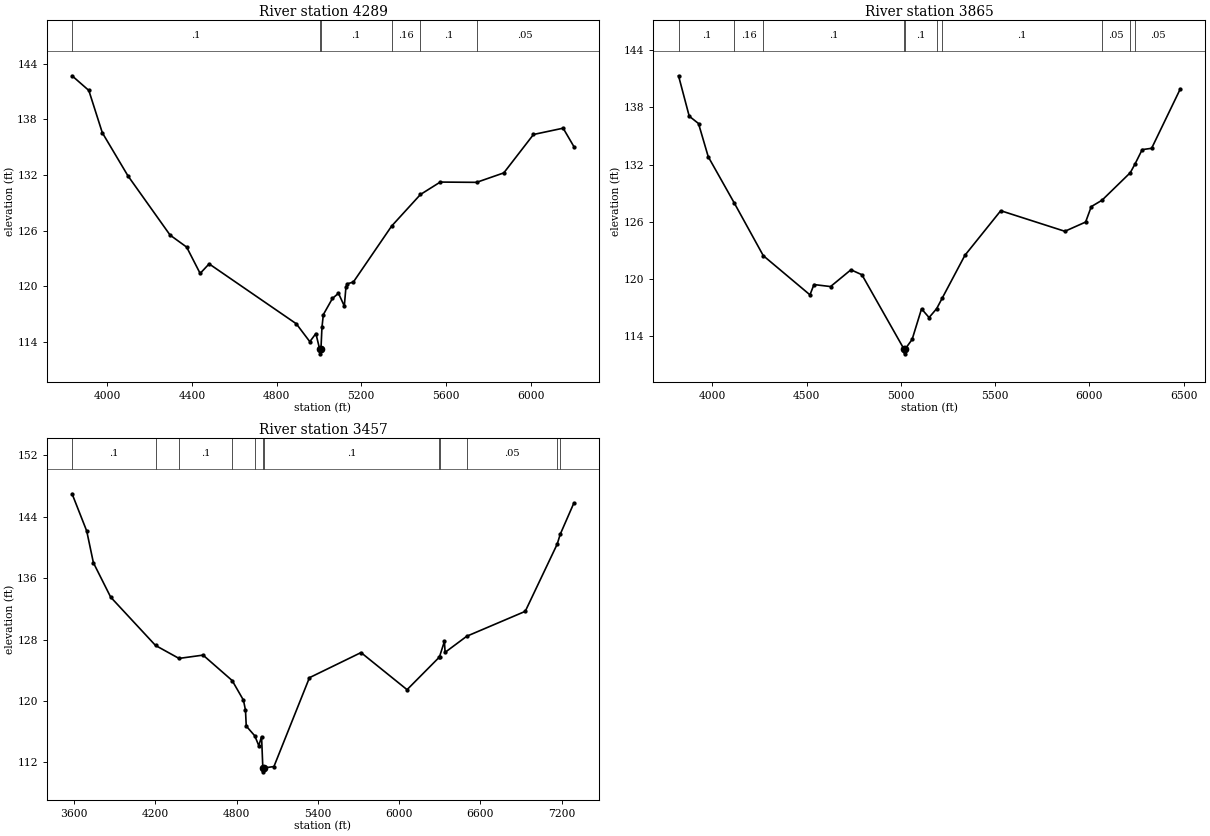
Type RM Length L Ch R = 1,4289,424,424,424
BEGIN DESCRIPTION:
UNT037 IN SPCR 9.0
END DESCRIPTION:
XS GIS Cut Line= 3
      2257092.61     13327980.21      2256233.25     13329008.83
      2256272.31     13330037.44
#Sta/Elev= 30
  3834.2  142.71  3913.3  141.13  3977.0  136.57  4098.1  131.92  4297.2  125.53
  4375.3  124.24  4439.0  121.40  4481.4  122.43  4893.2  115.97  4957.0  114.04
  4985.6  114.92  5003.5  113.23  5006.2  112.73  5009.5  113.23  5014.3  115.58
  5020.8  116.96  5063.7  118.70  5092.3  119.26  5119.9  117.88  5127.5  119.92
  5134.0  120.28  5162.6  120.47  5343.5  126.51  5479.4  129.91  5572.9  131.25
  5744.6  131.22  5873.1  132.24  6013.2  136.38  6153.3  137.06  6203.9  135.08
#Mann=6,-1,0
  3834.2     0.1       0  5003.5    0.07       0  5009.5     0.1       0
  5343.5    0.16       0  5479.4     0.1       0  5744.6    0.05       0
Bank Sta=5003.5,5009.5
Exp/Cntr=0.3,0.1

Type RM Length L Ch R = 1,3865,408,408,408
BEGIN DESCRIPTION:
UNT037 IN SPCR 8.0
END DESCRIPTION:
XS GIS Cut Line= 3
      2256493.65     13327876.05      2255959.82     13328761.44
      2256024.92     13330389.06
#Sta/Elev= 30
  3820.0  141.32  3876.7  137.08  3926.0  136.31  3977.7  132.82  4116.6  127.94
  4269.8  122.44  4517.4  118.33  4538.7  119.41  4626.7  119.20  4734.8  120.96
  4793.1  120.44  5016.4  112.64  5019.2  112.14  5022.4  112.64  5059.5  113.65
  5109.5  116.86  5149.5  115.95  5189.7  116.88  5219.6  118.00  5339.7  122.48
  5529.8  127.16  5870.1  125.00  5980.2  125.97  6010.2  127.59  6067.2  128.26
  6217.3  131.15  6243.1  132.09  6280.4  133.57  6330.5  133.71  6482.8  139.95
#Mann=10,-1,0
  3820.0     0.1       0  4116.6    0.16       0  4269.8     0.1       0
  5016.4    0.07       0  5022.4     0.1       0  5189.7    0.16       0
  5219.6     0.1       0  6067.2    0.05       0  6217.3     0.1       0
  6243.1    0.05       0
Bank Sta=5016.4,5022.4
Exp/Cntr=0.3,0.1

Type RM Length L Ch R = 1,3457,0,0,0
BEGIN DESCRIPTION:
UNT037 IN SPCR 1.0
END DESCRIPTION:
XS GIS Cut Line= 4
      2256369.55     13327606.01      2255771.85     13328156.27
      2255544.16     13329104.99      2255819.25     13331002.16
#Sta/Elev= 30
  3585.1  146.98  3693.3  142.13  3742.6  138.00  3870.2  133.52  4201.2  127.23
  4374.6  125.54  4552.4  125.97  4767.2  122.66  4850.6  120.10  4865.6  118.80
  4871.2  116.73  4934.2  115.46  4963.7  114.18  4984.3  115.36  4993.7  111.27
  4996.5  110.77  4999.7  111.27  5075.6  111.46  5337.8  123.03  5718.6  126.30
  6058.6  121.47  6294.8  125.67  6298.5  125.77  6334.4  127.76  6339.4  126.33
  6499.5  128.43  6931.2  131.67  7167.1  140.42  7189.4  141.70  7290.2  145.77
#Mann=12,-1,0
  3585.1     0.1       0  4201.2    0.16       0  4374.6     0.1       0
  4767.2    0.16       0  4934.2     0.1       0  4993.7    0.07       0
  4999.7     0.1       0  6294.8    0.05       0  6298.5     0.1       0
  6499.5    0.05       0  7167.1     0.1       0  7189.4    0.05       0
Bank Sta=4993.7,4999.7
Exp/Cntr=0.3,0.1

Chan Stop Cuts=-1