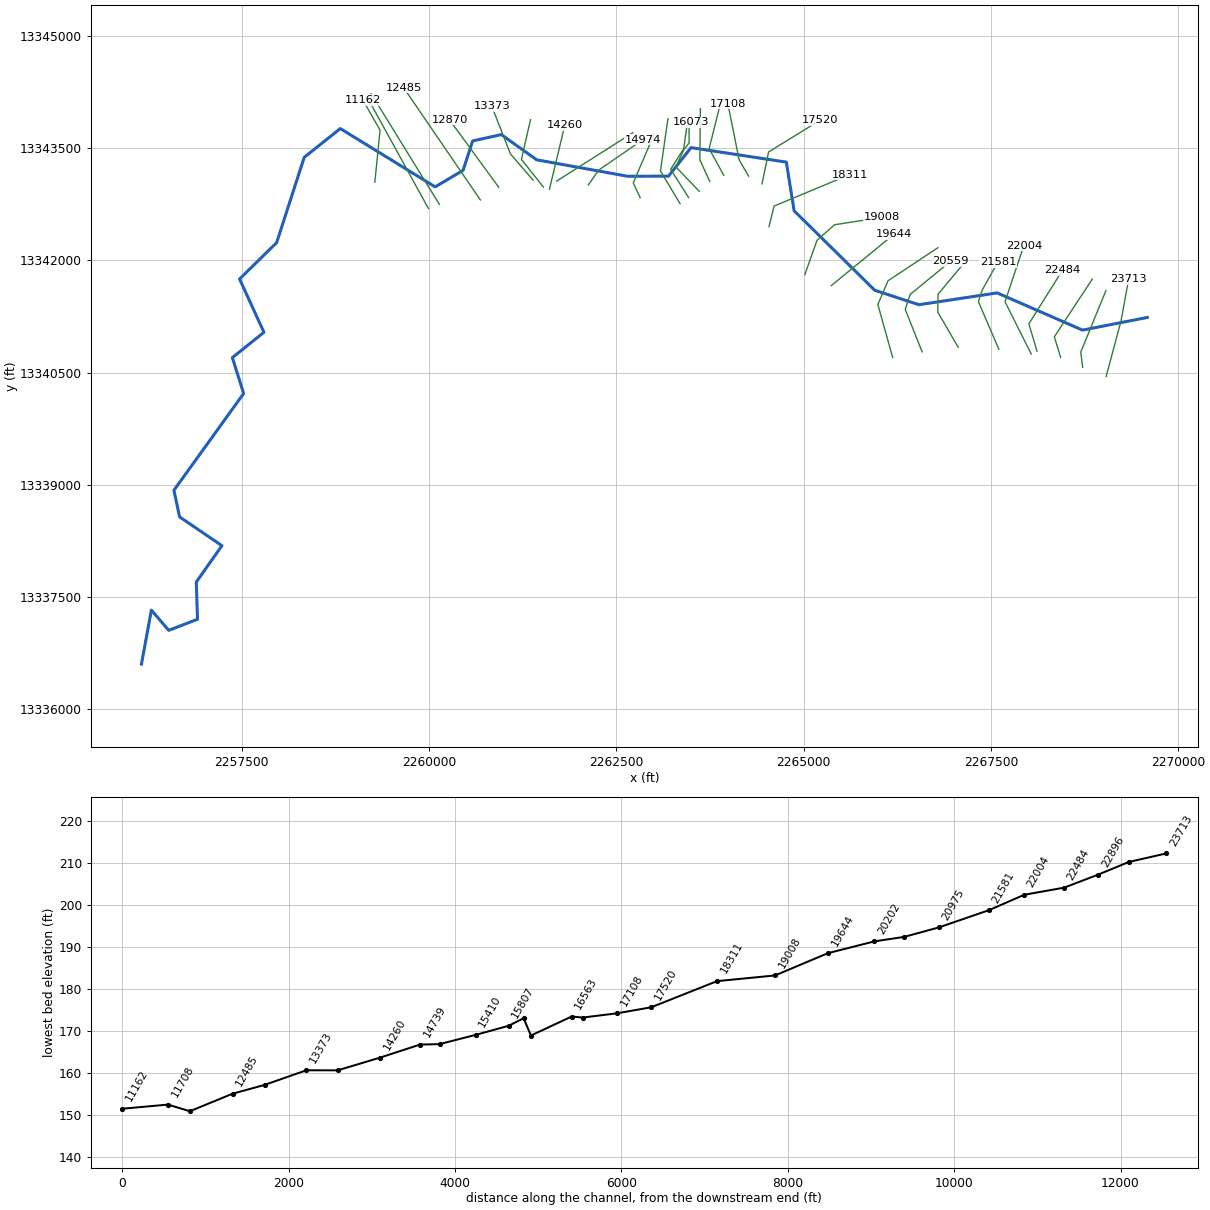
--- UNT038 IN SPCR.prj (project) ---

Proj Title=UNT038 IN SPCR Base Level Engineering
Current Plan=p01
Default Exp/Contr=0.3,0.1
English Units
Geom File=g01
Flow File=f01
Plan File=p01
Y Axis Title=Elevation
X Axis Title(PF)=Main Channel Distance
X Axis Title(XS)=Station
BEGIN DESCRIPTION:
UNT038 IN SPCR
END DESCRIPTION:
DSS Export Rating Curves= 0
DSS Export Rating Curve Sorted= 0
DSS Export Volume Flow Curves= 0
DXF OffsetX= 0
DXF OffsetY= 0
DXF ScaleX= 1
DXF ScaleY= 10

--- UNT038 IN SPCR.p01 (plan) ---

Plan Title=Multiple Run
Short Identifier=Multiple
Geom File=g01
Flow File=f01
Subcritical Flow
K Sum by GR= 0
Std Step Tol= 0.01
Critical Tol= 0.01
Num of Std Step Trials= 20
Max Error Tol= 0.3
Flow Tol Ratio= 0.001
Split Flow NTrial= 30
Split Flow Tol= 0.02
Split Flow Ratio= 0.02
Log Output Level= 0
Friction Slope Method= 1
Unsteady Friction Slope Method= 2
Unsteady Bridges Friction Slope Method= 1
Parabolic Critical Depth
Global Vel Dist=  1 , 1 , 1
Global Log Level= 0
CheckData=True
Encroach Param= -1, 0, 0, 0
BEGIN DESCRIPTION:
Multiple Run
END DESCRIPTION:

--- UNT038 IN SPCR.f01 (steady flow) ---

Flow Title=Multiple
Program Version=4.10
Number of Profiles= 7
Profile Names=10-year,25-year,50-year,1pct_min,100-year,1pct_plu,500-year
River Rch & RM=UNT038 IN SPCR,Reach-1         ,23713
     231     319     392     354     478     647     725
River Rch & RM=UNT038 IN SPCR,Reach-1         ,20559
     340     477     591     538     728     984    1122
River Rch & RM=UNT038 IN SPCR,Reach-1         ,11972
     422     598     748     686     928    1255    1453
Boundary for River Rch & Prof#=UNT038 IN SPCR,Reach-1         , 1
Up Type= 0
Dn Type= 3
Dn Slope=0.005
Boundary for River Rch & Prof#=UNT038 IN SPCR,Reach-1         , 2
Up Type= 0
Dn Type= 3
Dn Slope=0.005
Boundary for River Rch & Prof#=UNT038 IN SPCR,Reach-1         , 3
Up Type= 0
Dn Type= 3
Dn Slope=0.005
Boundary for River Rch & Prof#=UNT038 IN SPCR,Reach-1         , 4
Up Type= 0
Dn Type= 3
Dn Slope=0.005
Boundary for River Rch & Prof#=UNT038 IN SPCR,Reach-1         , 5
Up Type= 0
Dn Type= 3
Dn Slope=0.005
Boundary for River Rch & Prof#=UNT038 IN SPCR,Reach-1         , 6
Up Type= 0
Dn Type= 3
Dn Slope=0.005
Boundary for River Rch & Prof#=UNT038 IN SPCR,Reach-1         , 7
Up Type= 0
Dn Type= 3
Dn Slope=0.005
DSS Import GetInterval= 0
DSS Import GetPeak= 0
DSS Import FillOption= 0

--- UNT038 IN SPCR.g01 (geometry) ---

Geom Title=Existing Conditions
Program Version=4.10

River Reach=UNT038 IN SPCR  ,Reach-1
Reach XY= 30
      2269587.72     13341236.86       2268722.3     13341067.61
      2267582.61      13341565.4      2266537.97      13341407.2
      2265949.17     13341600.39       2264872.5     13342664.01
      2264768.15      13343315.7      2263496.44     13343509.96
      2263195.01     13343128.04      2262647.71     13343126.82
      2261434.86     13343347.08      2260963.34     13343684.24
       2260580.7     13343599.51      2260453.27     13343205.76
      2260080.17     13342984.58      2258813.63     13343765.14
      2258332.28     13343379.81      2257964.36     13342238.25
      2257469.51     13341751.31      2257794.71     13341038.08
      2257373.26     13340699.17      2257523.82     13340218.96
      2256592.99     13338923.51      2256668.64     13338567.74
      2257233.83     13338181.85      2256891.78     13337695.89
      2256907.73     13337197.33      2256523.43      13337048.7
      2256292.23     13337320.03      2256159.75     13336596.85

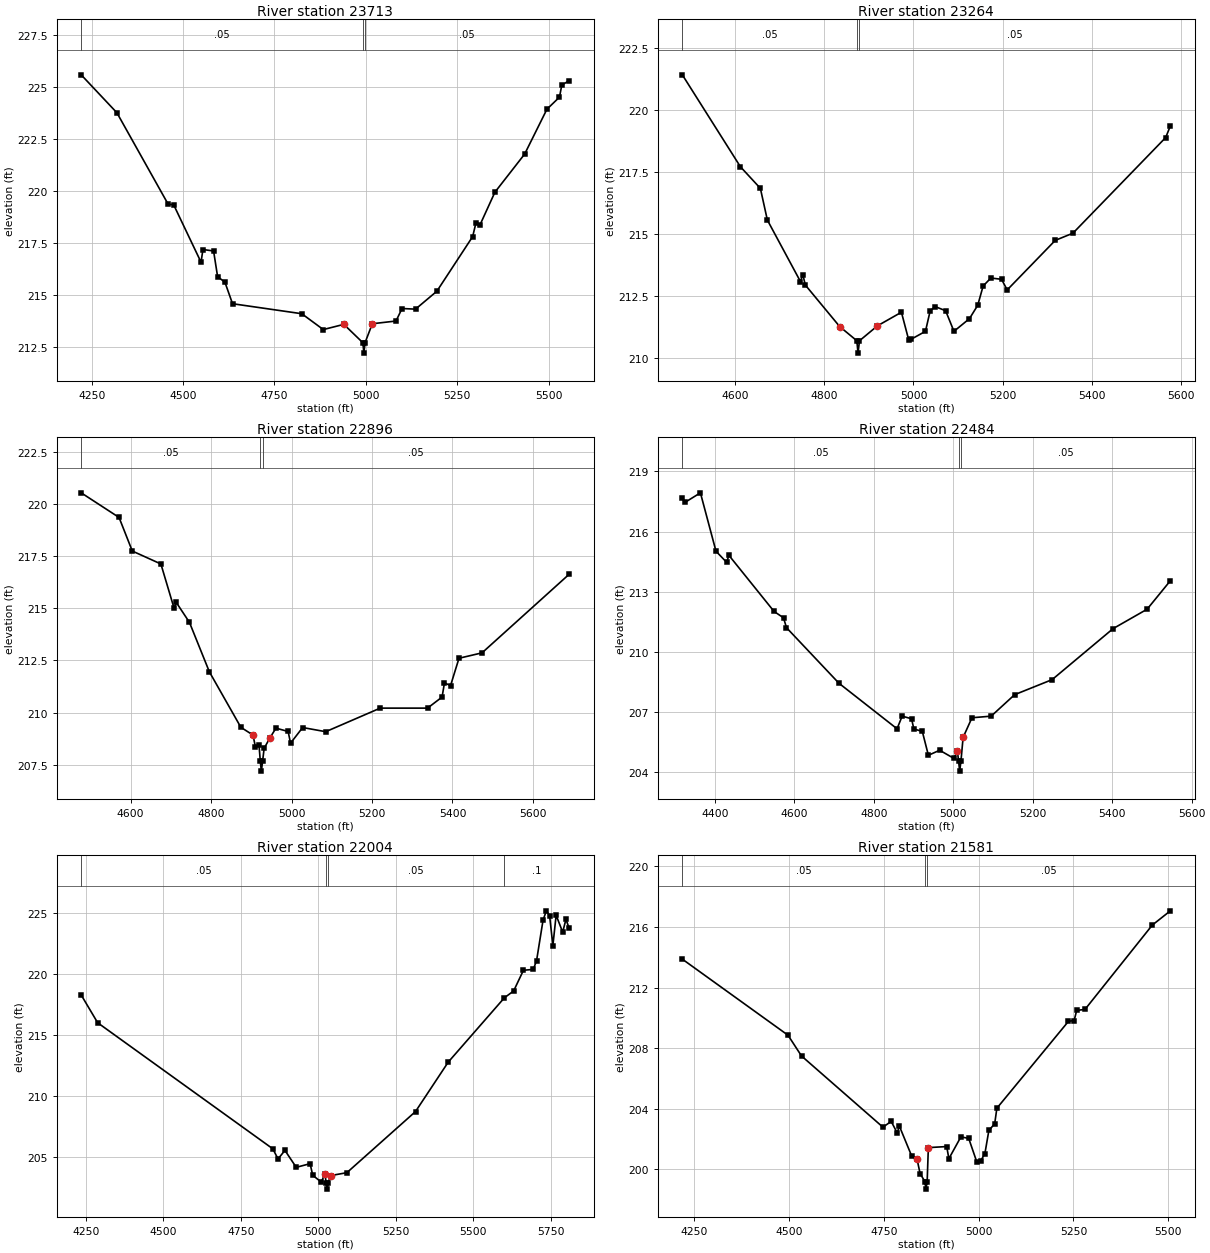
Type RM Length L Ch R = 1 ,23713   ,449,449,449
BEGIN DESCRIPTION:
UNT038 IN SPCR 42.0
END DESCRIPTION:
XS GIS Cut Line= 3
      2269037.72     13340446.86      2269237.72     13341196.85
      2269337.72     13341746.83
#Sta/Elev= 30
  4221.2  225.57  4318.9  223.75  4459.2  219.36  4474.1  219.34  4549.1  216.58
  4554.3  217.19  4583.4  217.12  4594.4  215.89  4614.5  215.62  4635.2  214.59
  4824.7  214.11  4883.6  213.35  4939.8   213.6  4991.8  212.72  4994.6  212.22
  4997.8  212.72  5017.7  213.63  5082.5  213.76    5099  214.36  5135.9  214.33
  5194.3  215.19  5292.2  217.81  5301.1  218.46  5312.5  218.38  5353.1  219.94
  5434.5  221.77  5495.4  223.92  5529.7   224.5  5536.1  225.08  5556.4  225.29
#Mann= 3 ,-1 , 0
  4221.2     .05       0  4991.8    .035       0  4997.8     .05       0
Bank Sta=4939.8,5017.7
XS Rating Curve= 0 ,0
Exp/Cntr=0.3,0.1

Type RM Length L Ch R = 1 ,23264   ,368,368,368
BEGIN DESCRIPTION:
UNT038 IN SPCR 41.0
END DESCRIPTION:
XS GIS Cut Line= 3
      2268723.96     13340567.32      2268698.76     13340773.09
      2269034.75     13341596.25
#Sta/Elev= 30
  4480.7  221.42  4611.2  217.71    4656  216.84  4671.7  215.56    4746  213.08
  4751.4  213.36  4756.9  212.94  4834.3  211.26  4872.7  210.69  4875.4  210.19
  4878.7  210.69  4918.9  211.29  4972.9  211.84  4989.3  210.72  4994.7  210.75
  5026.9  211.07  5037.4  211.89  5048.5  212.07  5072.2   211.9  5090.9  211.07
  5125.7  211.58  5144.3  212.12  5156.5   212.9  5173.8  213.22  5197.8  213.17
  5210.5  212.74  5318.5  214.74  5358.2  215.03  5566.6  218.89  5577.1  219.36
#Mann= 3 ,-1 , 0
  4480.7     .05       0  4872.7    .035       0  4878.7     .05       0
Bank Sta=4834.3,4918.9
XS Rating Curve= 0 ,0
Exp/Cntr=0.3,0.1

Type RM Length L Ch R = 1 ,22896   ,412,412,412
BEGIN DESCRIPTION:
UNT038 IN SPCR 40.0
END DESCRIPTION:
XS GIS Cut Line= 3
      2268429.98     13340701.72        2268346.     13340978.87
      2268853.42     13341750.48
#Sta/Elev= 30
  4477.2  220.53  4571.3  219.35  4604.2  217.74  4675.3  217.12  4708.2  214.99
  4713.4  215.28  4746.3  214.32  4795.8  211.95  4874.1  209.29  4904.2  208.92
  4910.2  208.36  4919.3  208.42  4922.3  207.69    4925  207.19  4928.3  207.69
  4931.9  208.28  4946.4  208.79  4961.4  209.25  4991.6  209.09  4997.6  208.53
  5027.7  209.28    5085  209.08  5220.5  210.21  5338.1  210.21  5374.2  210.74
  5380.2  211.42  5395.3  211.29  5416.3   212.6  5473.6  212.86  5690.3  216.63
#Mann= 3 ,-1 , 0
  4477.2     .05       0  4922.3    .035       0  4928.3     .05       0
Bank Sta=4904.2,4946.4
XS Rating Curve= 0 ,0
Exp/Cntr=0.3,0.1

Type RM Length L Ch R = 1 ,22484   ,480,480,480
BEGIN DESCRIPTION:
UNT038 IN SPCR 39.0
END DESCRIPTION:
XS GIS Cut Line= 3
      2268115.01     13340785.71      2268005.83     13341151.05
      2268455.17     13341869.15
#Sta/Elev= 30
    4318  217.66  4325.2  217.46  4363.5  217.93  4402.7  215.02  4429.8  214.46
    4435  214.82  4548.8  212.02  4572.7   211.7  4580.1  211.21  4712.2  208.44
  4858.4  206.17  4871.3   206.8  4894.9  206.67  4900.8  206.16    4922  206.04
  4937.3  204.85  4965.7   205.1  5001.1   204.7  5010.4  205.05  5013.3  204.56
  5016.1  204.06  5019.3  204.56  5024.7  205.74    5047  206.72  5095.4   206.8
  5154.4  207.87  5248.8  208.62  5402.1  211.16  5487.9  212.13  5546.4  213.55
#Mann= 3 ,-1 , 0
    4318     .05       0  5013.3    .035       0  5019.3     .05       0
Bank Sta=5010.4,5024.7
XS Rating Curve= 0 ,0
Exp/Cntr=0.3,0.1

Type RM Length L Ch R = 1 ,22004   ,423,423,423
BEGIN DESCRIPTION:
UNT038 IN SPCR 38.0
END DESCRIPTION:
XS GIS Cut Line= 3
      2268037.71     13340746.87      2267687.72     13341446.85
      2267937.73     13342196.88
#Sta/Elev= 30
  4235.6   218.3  4288.7  216.02  4853.3  205.67  4870.1  204.84  4892.4  205.54
  4928.8  204.15  4973.5  204.45  4981.9   203.5  5009.8  202.93  5020.8  203.62
  5025.7  202.86  5028.5  202.36  5031.7  202.86  5039.3  203.47    5092  203.71
  5313.3  208.73  5418.8  212.79  5599.8  218.07  5629.6  218.63  5661.2  220.33
  5692.8   220.4  5703.4   221.1  5724.4  224.44    5735  225.21  5745.5  224.82
  5756.1  222.36  5766.6  224.85  5787.7  223.46  5798.2  224.51  5808.8  223.77
#Mann= 4 ,-1 , 0
  4235.6     .05       0  5025.7    .035       0  5031.7     .05       0
  5599.8      .1       0
Bank Sta=5020.8,5039.3
XS Rating Curve= 0 ,0
Exp/Cntr=0.3,0.1

Type RM Length L Ch R = 1 ,21581   ,606,606,606
BEGIN DESCRIPTION:
UNT038 IN SPCR 37.0
END DESCRIPTION:
XS GIS Cut Line= 4
      2267605.47     13340810.88      2267332.03     13341448.91
      2267384.11     13341605.16      2267592.43      13341978.4
#Sta/Elev= 30
  4219.1  213.88  4497.6  208.86  4533.2  207.49  4747.8  202.79  4769.6  203.17
  4785.2  202.42  4791.3  202.85    4824  200.86  4837.8  200.67  4845.7  199.73
  4858.4   199.2  4861.1   198.7  4864.4   199.2  4867.5  201.44  4915.9  201.51
  4921.6  200.71  4953.3  202.15  4973.9  202.05  4995.4  200.48  5005.5  200.57
  5016.5  201.04    5027  202.57  5042.4  203.02  5048.1  204.04  5236.9  209.78
  5251.7  209.83  5258.6   210.5  5280.3  210.56  5457.8  216.13  5505.4  217.07
#Mann= 3 ,-1 , 0
  4219.1     .05       0  4858.4    .035       0  4864.4     .05       0
Bank Sta=4837.8,4867.5
XS Rating Curve= 0 ,0
Exp/Cntr=0.3,0.1

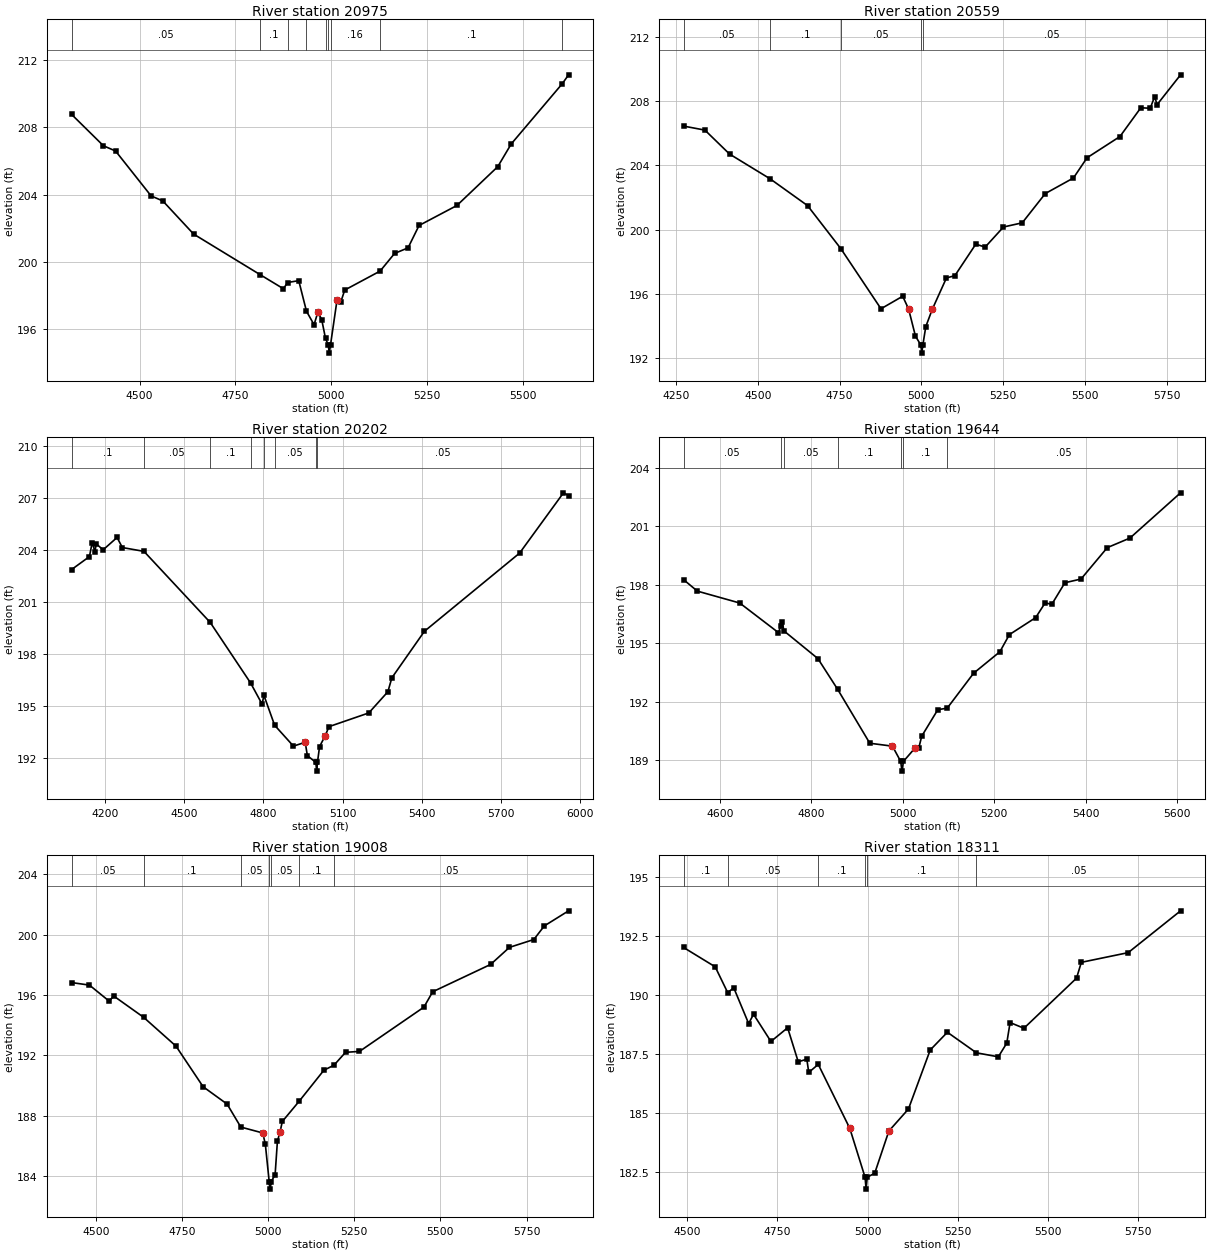
Type RM Length L Ch R = 1 ,20975   ,416,416,416
BEGIN DESCRIPTION:
UNT038 IN SPCR 36.0
END DESCRIPTION:
XS GIS Cut Line= 4
      2267062.93     13340836.95       2266789.5     13341310.03
      2266793.84     13341548.74      2267122.44      13341942.2
#Sta/Elev= 30
  4322.4  208.77  4405.8   206.9  4437.4  206.59  4530.2  203.92  4560.8  203.62
  4641.2  201.65  4814.6  199.24  4875.6   198.4  4886.8  198.77  4915.7  198.88
  4935.9  197.06  4955.7  196.26  4965.7  197.01  4975.7  196.56  4985.6  195.44
  4992.7  195.07  4995.4  194.57  4998.7  195.07  5015.7  197.73  5025.7  197.62
  5035.7  198.32  5128.2  199.45    5166   200.5  5201.1  200.83  5229.8  202.16
  5328.7  203.35  5435.4  205.66  5470.5  207.01  5604.1   210.6  5620.2  211.12
#Mann= 9 ,-1 , 0
  4322.4     .05       0  4814.6      .1       0  4886.8     .16       0
  4935.9     .05       0  4985.6     .16       0  4992.7     .07       0
  4998.7     .16       0  5128.2      .1       0  5604.1     .05       0
Bank Sta=4965.7,5015.7
XS Rating Curve= 0 ,0
Exp/Cntr=0.3,0.1

Type RM Length L Ch R = 1 ,20559   ,357,357,357
BEGIN DESCRIPTION:
UNT038 IN SPCR 35.0
END DESCRIPTION:
XS GIS Cut Line= 4
      2266581.18     13340776.14      2266355.47     13341344.75
      2266420.57      13341544.4      2266958.73     13341987.08
#Sta/Elev= 30
  4273.2  206.45  4338.5   206.2  4413.8  204.71  4537.6  203.17  4652.2   201.5
  4753.9  198.82  4876.5  195.08  4942.8  195.86  4960.8  195.07  4981.8  193.38
  4998.4  192.82  5001.1  192.32  5004.4  192.82  5013.4  193.97  5033.3  195.05
  5076.5     197  5102.2  197.14  5166.1   199.1  5194.8  198.92  5250.8  200.17
  5308.1  200.43  5378.5  202.25  5464.5  203.22  5506.2  204.48  5606.6   205.8
  5670.4  207.59  5699.1  207.56  5712.8  208.29  5719.9  207.78  5791.8  209.64
#Mann= 5 ,-1 , 0
  4273.2     .05       0  4537.6      .1       0  4753.9     .05       0
  4998.4    .035       0  5004.4     .05       0
Bank Sta=4960.8,5033.3
XS Rating Curve= 0 ,0
Exp/Cntr=0.3,0.1

Type RM Length L Ch R = 1 ,20202   ,558,558,558
BEGIN DESCRIPTION:
UNT038 IN SPCR 34.0
END DESCRIPTION:
XS GIS Cut Line= 4
      2266187.93     13340701.54      2265990.02     13341409.85
      2266125.43     13341727.56      2266792.12     13342170.28
#Sta/Elev= 30
  4073.9  202.86  4141.7  203.61  4152.1  204.42  4162.4   203.9  4167.6  204.34
  4193.6     204  4246.3  204.71  4266.3  204.13  4348.1  203.91  4598.8  199.82
  4751.4  196.34    4795  195.12  4802.1  195.62  4842.6   193.9  4913.8   192.7
  4958.3  192.92  4966.5  192.15  4998.7  191.76  5001.5  191.26  5004.7  191.76
  5012.6  192.67  5034.4  193.31  5048.2  193.82    5199  194.61  5271.2  195.83
  5286.2  196.63  5409.5  199.31  5769.7  203.81  5935.7  207.28    5955  207.12
#Mann= 8 ,-1 , 0
  4073.9      .1       0  4348.1     .05       0  4598.8      .1       0
  4751.4     .05       0  4802.1      .1       0  4842.6     .05       0
  4998.7     .03       0  5004.7     .05       0
Bank Sta=4958.3,5034.4
XS Rating Curve= 0 ,0
Exp/Cntr=0.3,0.1

Type RM Length L Ch R = 1 ,19644   ,636,636,636
BEGIN DESCRIPTION:
UNT038 IN SPCR 33.0
END DESCRIPTION:
XS GIS Cut Line= 2
      2265368.48     13341663.39      2266208.25       13342352.
#Sta/Elev= 30
  4520.9  198.27  4551.1  197.68  4643.7  197.07  4728.4  195.55  4733.5  195.91
  4736.3  196.11  4740.3  195.64  4814.5  194.22  4857.5  192.65  4927.9  189.88
  4977.4  189.73  4995.4  188.95  4998.2  188.45  5001.4  188.95  5026.9  189.64
  5034.8  189.62  5041.3  190.24  5076.5   191.6  5097.1  191.68  5154.7  193.47
  5212.1  194.57  5232.9  195.45  5290.3  196.32  5311.1  197.08  5325.5     197
  5354.2  198.11  5389.4   198.3  5446.8  199.91  5496.3   200.4  5606.9  202.72
#Mann= 7 ,-1 , 0
  4520.9     .05       0  4733.5      .1       0  4740.3     .05       0
  4857.5      .1       0  4995.4     .07       0  5001.4      .1       0
  5097.1     .05       0
Bank Sta=4977.4,5026.9
XS Rating Curve= 0 ,0
Exp/Cntr=0.3,0.1

Type RM Length L Ch R = 1 ,19008   ,697,697,697
BEGIN DESCRIPTION:
UNT038 IN SPCR 32.0
END DESCRIPTION:
XS GIS Cut Line= 4
      2265016.05     13341810.86      2265177.52     13342269.23
      2265411.89     13342477.56      2266047.28     13342576.51
#Sta/Elev= 30
  4429.4  196.82  4481.5  196.65  4538.1   195.6  4552.4  195.92  4638.6  194.52
  4732.6  192.61  4811.4  189.92    4881  188.77  4920.7  187.25  4984.4  186.86
  4991.9  186.12  5003.1  183.64  5005.9  183.14  5009.1  183.64  5020.3   184.1
    5027  186.32  5034.6  186.92  5041.2  187.62  5090.1  188.96  5161.7  191.01
  5191.3  191.35  5224.7   192.2  5265.2  192.26  5452.1  195.19  5477.7  196.21
  5645.8  198.02  5700.4  199.15  5771.2  199.67  5801.6  200.57    5872  201.57
#Mann= 7 ,-1 , 0
  4429.4     .05       0  4638.6      .1       0  4920.7     .05       0
  5003.1    .035       0  5009.1     .05       0  5090.1      .1       0
  5191.3     .05       0
Bank Sta=4984.4,5034.6
XS Rating Curve= 0 ,0
Exp/Cntr=0.3,0.1

Type RM Length L Ch R = 1 ,18311   ,791,791,791
BEGIN DESCRIPTION:
Mapping XS 983c77d7
END DESCRIPTION:
XS GIS Cut Line= 3
       2264536.9     13342451.56       2264604.6     13342727.56
      2265613.87     13343148.96
#Sta/Elev= 30
  4489.8  192.02  4577.6   191.2  4612.2  190.11  4629.1  190.31  4670.3   188.8
  4683.9  189.19  4732.1  188.04  4778.4  188.62  4807.8  187.18  4831.6  187.29
    4837  186.73  4863.3  187.07  4950.8  184.36  4993.1  182.29  4995.9  181.79
  4999.1  182.29    5020  182.47  5059.1  184.25  5113.3  185.18  5173.7  187.68
  5221.3  188.43  5301.8  187.56  5362.5  187.39  5385.9  187.97  5395.1  188.84
  5433.5   188.6  5579.3  190.72  5592.6  191.39  5722.5   191.8  5867.7  193.57
#Mann= 6 ,-1 , 0
  4489.8      .1       0  4612.2     .05       0  4863.3      .1       0
  4993.1     .07       0  4999.1      .1       0  5301.8     .05       0
Bank Sta=4950.8,5059.1
XS Rating Curve= 0 ,0
Exp/Cntr=0.3,0.1

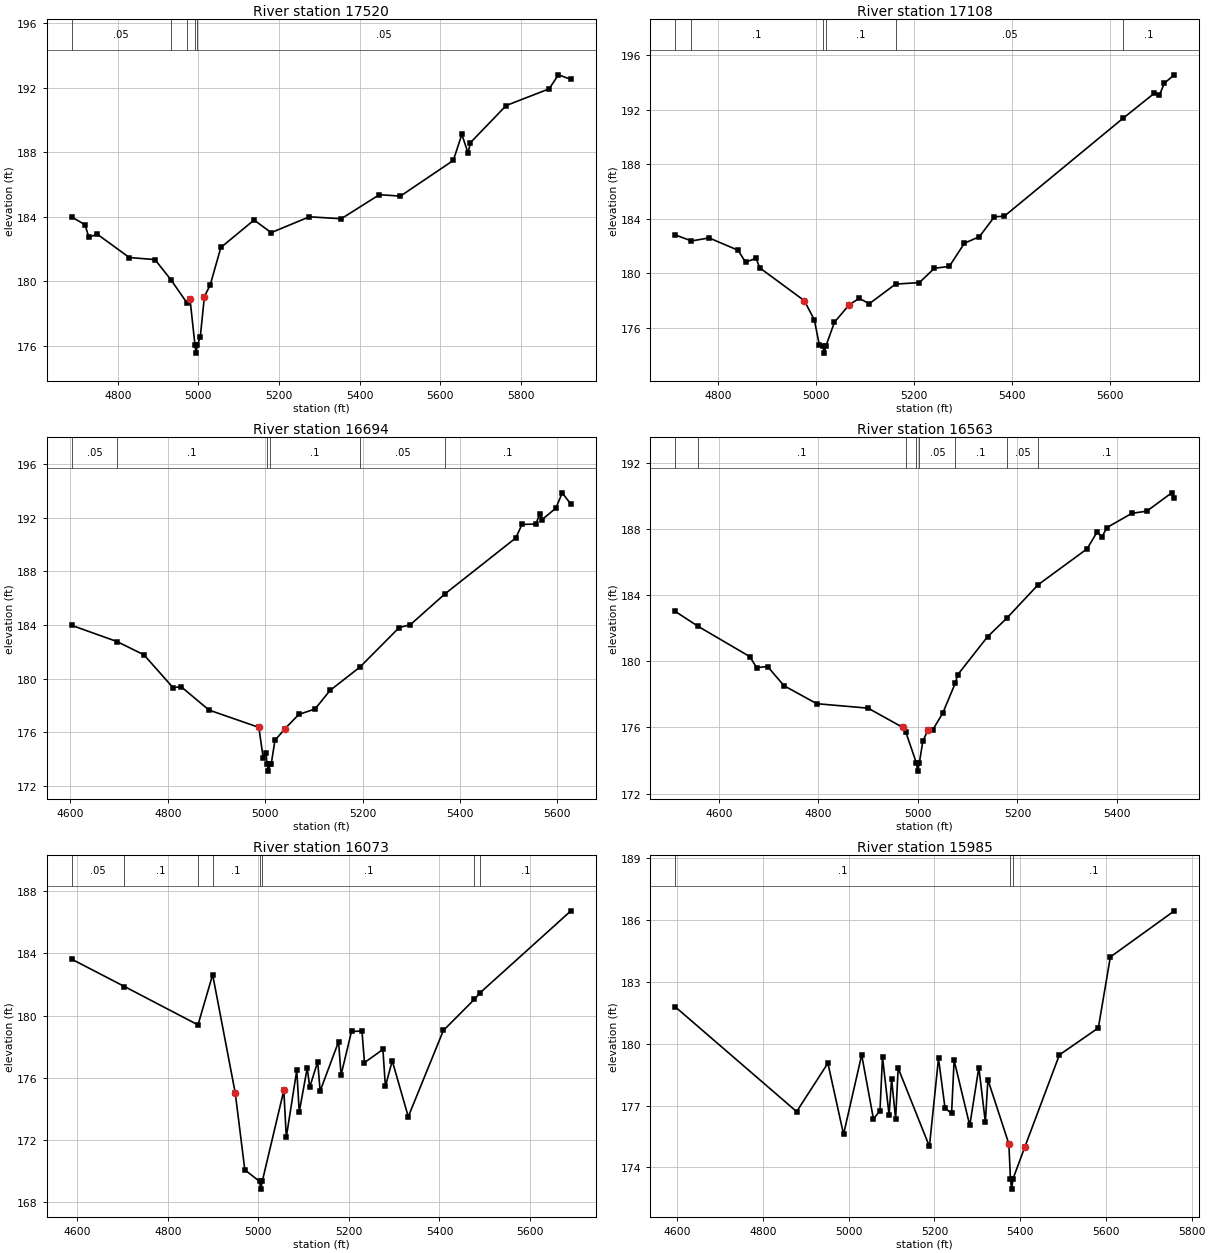
Type RM Length L Ch R = 1 ,17520   ,412,412,412
BEGIN DESCRIPTION:
Mapping XS 69ea2d7a
END DESCRIPTION:
XS GIS Cut Line= 3
      2264443.14     13343024.43      2264531.68     13343451.52
      2265214.01     13343873.42
#Sta/Elev= 30
  4685.6  183.99  4718.7  183.51  4728.3  182.74  4749.4  182.92  4828.6  181.48
  4892.3  181.35  4931.6  180.11  4971.7  178.67  4979.1  178.93  4991.5  176.06
  4994.2  175.56  4997.5  176.06  5004.7  176.57  5014.9  179.06  5029.3  179.78
  5055.7   182.1  5138.1   183.8  5180.6  183.02  5275.2     184  5354.4  183.88
  5448.9  185.37    5501  185.28  5632.2  187.49  5653.4   189.1  5668.8  187.95
  5674.7  188.59  5763.4  190.89  5869.7  191.92  5893.1  192.79    5924  192.51
#Mann= 5 ,-1 , 0
  4685.6     .05       0  4931.6      .1       0  4971.7     .05       0
  4991.5     .03       0  4997.5     .05       0
Bank Sta=4979.1,5014.9
XS Rating Curve= 0 ,0
Exp/Cntr=0.3,0.1

Type RM Length L Ch R = 1 ,17108   ,414,414,414
BEGIN DESCRIPTION:
UNT038 IN SPCR 31.0
END DESCRIPTION:
XS GIS Cut Line= 3
      2264265.44     13343127.91      2264137.72     13343346.85
      2263987.73     13344096.83
#Sta/Elev= 30
  4712.3  182.81  4745.8  182.36  4781.8  182.58  4840.5  181.68  4856.2   180.8
  4877.7  181.09  4884.7  180.39    4976  177.97  4996.4  176.56  5006.6   174.7
  5013.8  174.62  5016.5  174.12  5019.8  174.62  5037.2  176.38  5067.8  177.69
  5088.1  178.14  5108.5  177.75    5162  179.19  5210.5   179.3  5241.1  180.35
  5271.7  180.49  5302.3  182.19  5332.9  182.67  5363.5  184.13  5383.9  184.18
    5626  191.37  5689.8  193.21    5700  193.06  5710.2  193.95  5730.6  194.56
#Mann= 6 ,-1 , 0
  4712.3     .05       0  4745.8      .1       0  5013.8     .07       0
  5019.8      .1       0    5162     .05       0    5626      .1       0
Bank Sta=4976,5067.8
XS Rating Curve= 0 ,0
Exp/Cntr=0.3,0.1

Type RM Length L Ch R = 1 ,16694   ,131,131,131
BEGIN DESCRIPTION:
UNT038 IN SPCR 30.0
END DESCRIPTION:
XS GIS Cut Line= 3
      2263932.79     13343139.22      2263737.72     13343496.85
      2263887.71     13344096.82
#Sta/Elev= 30
  4602.4  183.97  4695.7  182.76  4751.1  181.77  4810.9  179.32    4827  179.41
  4884.5  177.66    4987  176.37    4996  174.09  5001.7  174.47  5003.9  173.61
  5006.7  173.11  5009.9  173.61  5012.3  173.61  5020.1   175.4  5040.7  176.27
    5069  177.33  5102.5  177.74  5133.5  179.13  5194.7  180.86  5275.2   183.8
  5298.4  184.02  5369.6  186.32  5514.9  190.48  5527.7  191.49  5556.1  191.51
  5563.8  192.23    5569  191.85  5597.3   192.7  5610.2  193.84  5628.2  192.99
#Mann= 6 ,-1 , 0
  4602.4     .05       0  4695.7      .1       0  5003.9     .07       0
  5009.9      .1       0  5194.7     .05       0  5369.6      .1       0
Bank Sta=4987,5040.7
XS Rating Curve= 0 ,0
Exp/Cntr=0.3,0.1

Type RM Length L Ch R = 1 ,16563   ,490,490,490
BEGIN DESCRIPTION:
Mapping XS 9ed1ee6a
END DESCRIPTION:
XS GIS Cut Line= 3
      2263745.89     13343057.63      2263614.14     13343347.49
      2263620.72     13344032.26
#Sta/Elev= 30
  4512.2  183.03  4558.6  182.12  4662.3  180.29  4676.1  179.62  4698.1  179.69
    4731  178.53  4796.9  177.44    4900  177.17    4970     176  4975.6  175.74
    4997  173.86  4999.7  173.36    5003  173.86    5010  175.16    5020  175.84
    5030  175.86    5050  176.87  5075.6  178.71    5080  179.19    5140  181.49
  5178.5  182.61  5241.7  184.64    5340  186.81    5360  187.82    5370  187.54
    5380   188.1    5430  188.96    5460  189.09    5510   190.2  5515.4  189.86
#Mann= 8 ,-1 , 0
  4512.2     .05       0  4558.6      .1       0  4975.6     .05       0
    4997     .03       0    5003     .05       0  5075.6      .1       0
  5178.5     .05       0  5241.7      .1       0
Bank Sta=4970,5020
XS Rating Curve= 0 ,0
Exp/Cntr=0.3,0.1

Type RM Length L Ch R = 1 ,16073   ,88,88,88
BEGIN DESCRIPTION:
Mapping XS ac574d4b
END DESCRIPTION:
XS GIS Cut Line= 6
      2263606.36     13342924.84      2263293.84     13343251.26
      2263394.53     13343473.48      2263470.92     13343574.17
      2263469.46     13343754.98      2263491.73     13343851.87
#Sta/Elev= 30
  4587.8  183.63  4704.4  181.87  4866.8   179.4  4899.2  182.63  4949.1  175.01
  4970.2  170.07  5002.7  169.33  5005.5  168.83  5008.7  169.33  5056.3  175.18
  5061.8  172.17  5084.9  176.47  5090.4  173.79    5108  176.63  5113.5  175.39
  5131.1  177.03  5136.5  175.14  5177.2  178.32  5182.7  176.18  5205.8  178.98
  5228.9     179  5234.4  176.97  5275.1  177.82  5280.6  175.44  5295.7  177.09
  5331.1  173.49  5408.6  179.04    5477  181.04  5489.5  181.46  5690.3  186.74
#Mann= 8 ,-1 , 0
  4587.8     .05       0  4704.4      .1       0  4866.8     .05       0
  4899.2      .1       0  5002.7     .07       0  5008.7      .1       0
    5477     .05       0  5489.5      .1       0
Bank Sta=4949.1,5056.3
XS Rating Curve= 0 ,0
Exp/Cntr=0.3,0.1

Type RM Length L Ch R = 1 ,15985   ,178,178,178
BEGIN DESCRIPTION:
Mapping XS b63f1456
END DESCRIPTION:
XS GIS Cut Line= 4
      2263463.99     13342841.51      2263224.39     13343220.01
        2263398.     13343494.31      2263453.46     13343882.49
#Sta/Elev= 30
    4595   181.8  4878.6  176.71  4951.5  179.06    4988  175.61  5030.3  179.46
  5057.8  176.35    5073  176.76  5078.9  179.35  5094.2  176.55  5100.1  178.29
  5109.5  176.35  5115.4  178.82  5188.3  175.02  5209.5  179.29  5224.7  176.88
    5240  176.62  5245.9   179.2  5282.4  176.04  5303.6  178.85  5318.8  176.19
  5324.7  178.26 5373.64  175.14  5377.3  173.45    5380  172.95  5383.3  173.45
  5410.6  174.98  5491.4  179.46  5582.3  180.77  5610.3  184.21  5759.7  186.45
#Mann= 3 ,-1 , 0
    4595      .1       0  5377.3     .07       0  5383.3      .1       0
Bank Sta=5373.64,5410.6
XS Rating Curve= 0 ,0
Exp/Cntr=0.3,0.1

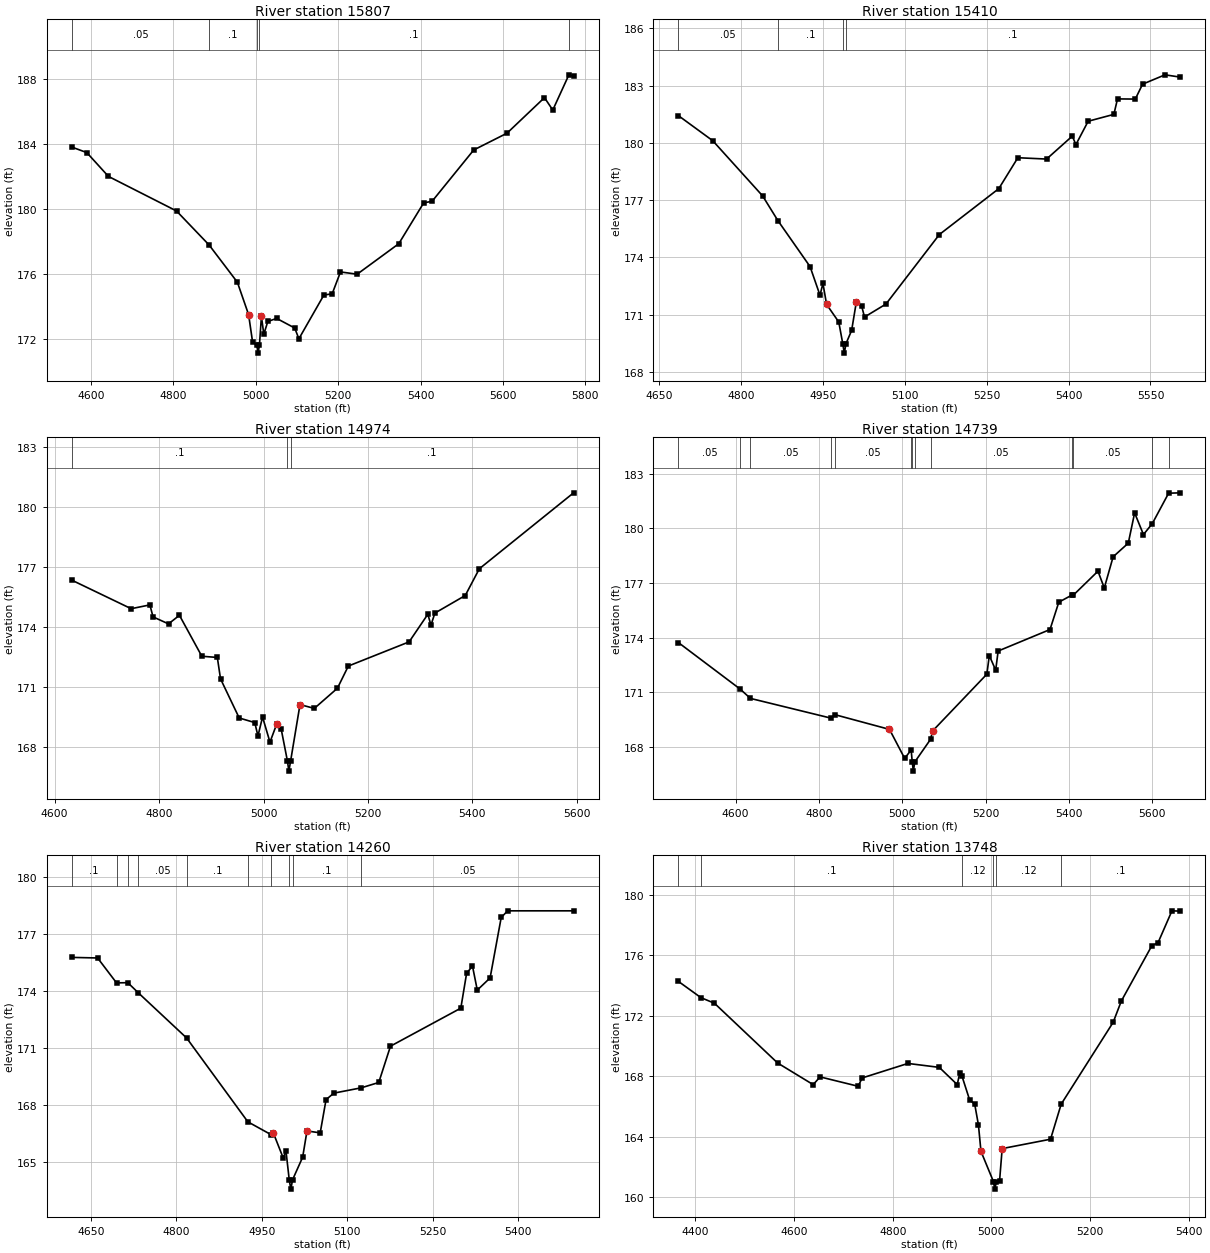
Type RM Length L Ch R = 1 ,15807   ,397,397,397
BEGIN DESCRIPTION:
UNT038 IN SPCR 28.0
END DESCRIPTION:
XS GIS Cut Line= 3
      2263350.52     13342758.85      2263087.72     13343196.85
      2263187.72     13343896.85
#Sta/Elev= 30
  4553.4   183.8  4589.9  183.46  4642.4     182  4807.6  179.88  4886.8  177.79
  4955.3  175.51  4982.6  173.52  4992.3  171.83  5002.9  171.66  5005.6  171.16
  5008.9  171.66  5013.7  173.41  5019.5  172.32  5029.2   173.1  5050.6  173.29
  5094.5   172.7  5104.6  172.04  5165.2  174.72  5185.4   174.8  5205.6  176.14
    5246     176    5347  177.87  5407.6  180.38  5427.8  180.47  5528.9  183.62
  5609.7  184.65  5700.6  186.83  5720.8  186.07  5759.9  188.23  5771.3  188.14
#Mann= 5 ,-1 , 0
  4553.4     .05       0  4886.8      .1       0  5002.9     .07       0
  5008.9      .1       0  5759.9     .08       0
Bank Sta=4982.6,5013.7
XS Rating Curve= 0 ,0
Exp/Cntr=0.3,0.1

Type RM Length L Ch R = 1 ,15410   ,436,436,436
BEGIN DESCRIPTION:
Mapping XS 19cb8941
END DESCRIPTION:
XS GIS Cut Line= 3
      2262817.08     13342840.25      2262724.85     13343037.89
      2263001.19     13343682.67
#Sta/Elev= 30
  4685.1  181.42  4747.9  180.11  4839.3  177.22  4867.2  175.93  4926.2  173.52
  4944.4  172.02  4949.8  172.64  4956.5  171.54  4978.8  170.62  4986.1  169.49
  4988.9  168.99  4992.1  169.49  5002.4  170.18  5010.9  171.65  5020.5  171.48
    5026  170.88  5065.3  171.56  5163.2   175.2    5272   177.6    5307  179.22
  5359.6  179.15  5406.7  180.35  5413.4  179.91  5435.8  181.13  5482.9  181.49
  5489.6   182.3  5522.2  182.29  5535.5  183.07  5576.6  183.56  5604.7  183.44
#Mann= 4 ,-1 , 0
  4685.1     .05       0  4867.2      .1       0  4986.1     .07       0
  4992.1      .1       0
Bank Sta=4956.5,5010.9
XS Rating Curve= 0 ,0
Exp/Cntr=0.3,0.1

Type RM Length L Ch R = 1 ,14974   ,235,235,235
BEGIN DESCRIPTION:
UNT038 IN SPCR 27.0
END DESCRIPTION:
XS GIS Cut Line= 3
      2262125.41     13343011.54      2262263.74     13343209.16
      2262856.56     13343617.55
#Sta/Elev= 30
  4632.7  176.34  4746.5  174.91  4782.3   175.1  4788.4   174.5    4818  174.15
  4838.9  174.58  4881.8  172.53  4911.5  172.47  4917.6   171.4  4953.4  169.44
  4983.2  169.21  4989.3  168.54  4998.1  169.49  5012.3  168.23  5025.1  169.13
  5033.9  168.87  5045.8  167.28  5048.5  166.78  5051.8  167.28  5069.8  170.11
  5097.3  169.92  5141.5  170.93  5162.4  172.04  5278.8  173.25  5314.6  174.63
  5320.7  174.09  5328.1  174.69  5386.3  175.57  5413.3  176.91  5593.8  180.71
#Mann= 3 ,-1 , 0
  4632.7      .1       0  5045.8     .07       0  5051.8      .1       0
Bank Sta=5025.1,5069.8
XS Rating Curve= 0 ,0
Exp/Cntr=0.3,0.1

Type RM Length L Ch R = 1 ,14739   ,479,479,479
BEGIN DESCRIPTION:
Mapping XS 6fe938d3
END DESCRIPTION:
XS GIS Cut Line= 2
      2261702.28     13343061.88      2262718.56      13343708.6
#Sta/Elev= 30
  4462.9  173.72    4611  171.17  4635.6  170.66  4828.5  169.58  4839.6  169.76
  4969.4  168.96  5005.8  167.37  5021.4  167.83    5024  167.17  5026.7  166.67
    5030  167.17  5068.1  168.42  5072.7  168.87  5203.1  171.99    5209  173.01
  5224.3  172.21  5230.2  173.26  5354.7  174.44  5375.8  175.94  5407.3  176.33
  5410.9  176.33  5469.8  177.64    5485  176.72  5506.2  178.43  5542.6  179.18
  5557.8  180.84    5579  179.65  5600.2  180.25  5639.4  181.92  5667.5  181.94
#Mann= 13 ,-1 , 0
  4462.9     .05       0    4611      .1       0  4635.6     .05       0
  4828.5      .1       0  4839.6     .05       0  5021.4      .1       0
    5024     .04       0    5030      .1       0  5068.1     .05       0
  5407.3      .1       0  5410.9     .05       0  5600.2      .1       0
  5639.4     .05       0
Bank Sta=4969.4,5072.7
XS Rating Curve= 0 ,0
Exp/Cntr=0.3,0.1

Type RM Length L Ch R = 1 ,14260   ,512,512,512
BEGIN DESCRIPTION:
Mapping XS 79afb79d
END DESCRIPTION:
XS GIS Cut Line= 2
      2261605.66     13342952.69      2261811.45     13343809.42
#Sta/Elev= 30
  4616.4  175.76  4661.8  175.73    4695  174.42  4714.8  174.43  4733.5  173.89
  4818.1  171.52  4925.6  167.11  4966.7  166.43  4970.4  166.52  4987.5  165.22
  4992.6  165.56  4998.2  164.07    5001  163.57  5004.2  164.07  5021.8  165.25
  5029.4  166.63  5052.6  166.53  5062.9  168.28  5076.6  168.62  5124.8   168.9
  5155.4  169.18    5176  171.09  5299.5  173.09  5309.7  174.93    5320   175.3
  5328.4  174.04  5350.9  174.68  5370.4  177.86  5381.7  178.21  5497.5  178.21
#Mann= 10 ,-1 , 0
  4616.4      .1       0    4695     .05       0  4714.8      .1       0
  4733.5     .05       0  4818.1      .1       0  4925.6     .12       0
  4966.7      .1       0  4998.2     .07       0  5004.2      .1       0
  5124.8     .05       0
Bank Sta=4970.4,5029.4
XS Rating Curve= 0 ,0
Exp/Cntr=0.3,0.1

Type RM Length L Ch R = 1 ,13748   ,375,375,375
BEGIN DESCRIPTION:
UNT038 IN SPCR 25.0
END DESCRIPTION:
XS GIS Cut Line= 3
      2261525.87     13342982.06      2261231.89     13343351.63
      2261353.32     13343883.41
#Sta/Elev= 30
  4365.6  174.26  4411.1  173.19  4438.5  172.82  4566.6  168.87  4638.7  167.44
  4652.8  167.95    4730  167.33    4738  167.88  4830.9  168.84  4894.5  168.58
  4930.9  167.44    4936  168.21  4940.7  167.98    4956  166.43  4966.3  166.15
  4973.9  164.77    4979  163.03  5004.3  161.03  5007.1  160.53  5010.3  161.03
  5016.8   161.1    5022  163.21  5120.1  163.83  5141.7  166.15  5247.1  171.56
  5263.7  172.97  5325.3  176.61  5338.2  176.83  5366.3  178.93  5383.3  178.91
#Mann= 6 ,-1 , 0
  4365.6     .05       0  4411.1      .1       0  4940.7     .12       0
  5004.3     .07       0  5010.3     .12       0  5141.7      .1       0
Bank Sta=4979,5022
XS Rating Curve= 0 ,0
Exp/Cntr=0.3,0.1

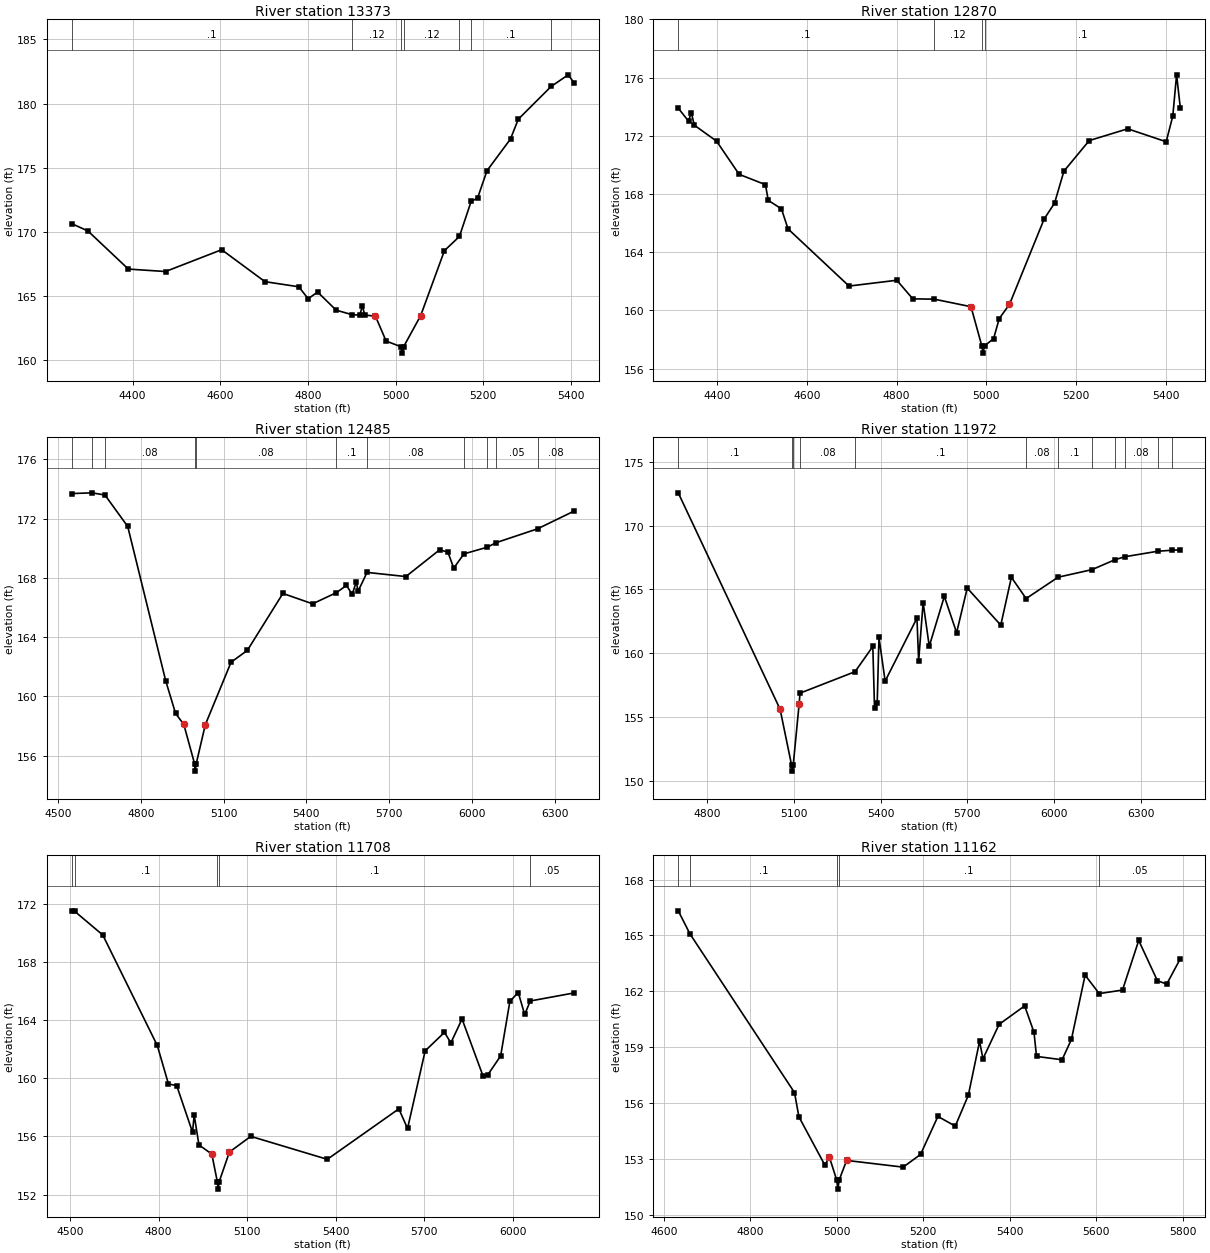
Type RM Length L Ch R = 1 ,13373   ,503,503,503
BEGIN DESCRIPTION:
UNT038 IN SPCR 24.0
END DESCRIPTION:
XS GIS Cut Line= 3
      2261387.28     13343074.45      2261084.91     13343427.23
      2260837.12     13344061.41
#Sta/Elev= 30
  4261.1  170.64    4298  170.07  4390.2   167.1    4475  166.91  4603.1  168.61
  4701.9  166.12    4779  165.72  4800.5  164.79    4822  165.31  4864.3   163.9
  4900.2  163.55  4918.6  163.51    4924  164.26  4929.4  163.52  4953.9  163.43
  4978.3  161.49  5012.2  161.05    5015  160.55  5018.2  161.05  5057.1  163.47
  5111.4  168.54  5145.5  169.64  5172.2  172.37    5187  172.64  5208.5  174.77
  5262.1  177.24  5279.8  178.78    5355  181.34  5393.8  182.24  5406.6  181.64
#Mann= 7 ,-1 , 0
  4261.1      .1       0  4900.2     .12       0  5012.2     .07       0
  5018.2     .12       0  5145.5     .05       0  5172.2      .1       0
    5355     .05       0
Bank Sta=4953.9,5057.1
XS Rating Curve= 0 ,0
Exp/Cntr=0.3,0.1

Type RM Length L Ch R = 1 ,12870   ,385,385,385
BEGIN DESCRIPTION:
Mapping XS f887d3f6
END DESCRIPTION:
XS GIS Cut Line= 2
      2260929.53     13342977.86      2260271.32     13343883.42
#Sta/Elev= 30
  4313.1   173.9    4336  173.01  4342.2   173.6  4348.9  172.73  4398.6  171.63
  4448.9  169.35  4507.6  168.64  4513.8  167.56  4543.2  166.98  4557.9   165.6
  4693.9  161.67  4800.5  162.07  4836.1  160.79  4883.9  160.77  4965.9  160.25
    4990  157.56  4992.7  157.06    4996  157.56  5016.2  158.05  5028.9  159.44
  5051.7  160.41    5129  166.28  5152.2  167.37  5173.1  169.57  5229.5  171.67
  5315.3  172.48  5401.1  171.59  5415.8  173.35  5424.3  176.19  5432.6  173.92
#Mann= 4 ,-1 , 0
  4313.1      .1       0  4883.9     .12       0    4990     .07       0
    4996      .1       0
Bank Sta=4965.9,5051.7
XS Rating Curve= 0 ,0
Exp/Cntr=0.3,0.1

Type RM Length L Ch R = 1 ,12485   ,513,513,513
BEGIN DESCRIPTION:
Mapping XS 6435e6df
END DESCRIPTION:
XS GIS Cut Line= 2
      2260683.82     13342809.74      2259658.82     13344313.42
#Sta/Elev= 30
  4549.6  173.69  4623.1  173.74    4670  173.59  4752.4  171.47    4890  161.06
  4925.9  158.85  4955.7  158.11  4994.7  155.46  4997.4  154.96  5000.7  155.46
  5033.6  158.09    5127  162.31  5186.1  163.11  5314.8  166.95  5422.5  166.25
  5508.4     167  5545.2  167.49  5566.1  166.89  5581.1  167.75  5587.1  167.09
  5619.8  168.37  5760.6  168.09  5883.3   169.9  5913.1  169.73  5934.1  168.66
  5971.1  169.62  6055.4  170.07  6088.1  170.38  6237.7  171.31  6369.4   172.5
#Mann= 11 ,-1 , 0
  4549.6     .08       0  4623.1      .1       0    4670     .08       0
  4994.7     .07       0  5000.7     .08       0  5508.4      .1       0
  5619.8     .08       0  5971.1     .05       0  6055.4     .08       0
  6088.1     .05       0  6237.7     .08       0
Bank Sta=4955.7,5033.6
XS Rating Curve= 0 ,0
Exp/Cntr=0.3,0.1

Type RM Length L Ch R = 1 ,11972   ,264,264,264
BEGIN DESCRIPTION:
Mapping XS ba13c2d0
END DESCRIPTION:
XS GIS Cut Line= 2
      2260136.56     13342750.64       2259226.8     13344229.87
#Sta/Elev= 30
  4699.9  172.56  5052.2  155.63  5091.7  151.29  5094.5  150.79  5097.7  151.29
  5118.1  156.05  5121.1  156.89  5311.6  158.57  5372.9  160.54  5378.8  155.76
  5388.1  156.11  5394.2  161.25  5415.5  157.83  5525.6  162.76  5531.4   159.4
  5546.9  163.98  5568.1  160.56  5620.3  164.46  5662.8  161.62  5699.5  165.11
  5815.5  162.21  5852.2  165.95  5903.2  164.29  6013.8  165.96  6130.8  166.55
  6210.8  167.33  6244.5  167.56  6358.3  167.99  6407.8  168.07  6436.5   168.1
#Mann= 12 ,-1 , 0
  4699.9      .1       0  5091.7     .07       0  5097.7      .1       0
  5121.1     .08       0  5311.6      .1       0  5903.2     .08       0
  6013.8      .1       0  6130.8     .08       0  6210.8      .1       0
  6244.5     .08       0  6358.3      .1       0  6407.8     .05       0
Bank Sta=5052.2,5118.1
XS Rating Curve= 0 ,0
Exp/Cntr=0.3,0.1

Type RM Length L Ch R = 1 ,11708   ,546,546,546
BEGIN DESCRIPTION:
UNT038 IN SPCR 21.0
END DESCRIPTION:
XS GIS Cut Line= 2
       2259990.7     13342695.12        2259172.     13344186.82
#Sta/Elev= 30
  4505.5  171.51  4515.7  171.47  4610.5  169.85  4795.3  162.25  4833.2   159.6
  4861.1  159.49  4914.7  156.29  4920.4  157.46  4936.5  155.41  4980.1  154.78
  4998.9  152.87  5001.7  152.37  5004.9  152.87  5039.8  154.92  5112.1     156
  5371.5  154.42    5614  157.89  5643.5  156.54  5703.2  161.88  5768.6  163.15
  5790.3  162.43  5828.2  164.07  5899.3  160.15  5915.4  160.23    5959  161.53
  5990.4  165.29  6018.7  165.89  6040.5  164.38  6059.5  165.31  6207.1  165.86
#Mann= 5 ,-1 , 0
  4505.5     .08       0  4515.7      .1       0  4998.9     .07       0
  5004.9      .1       0  6059.5     .05       0
Bank Sta=4980.1,5039.8
XS Rating Curve= 0 ,0
Exp/Cntr=0.3,0.1

Type RM Length L Ch R = 1 ,11162   ,409,409,409
BEGIN DESCRIPTION:
UNT038 IN SPCR 20.0
END DESCRIPTION:
XS GIS Cut Line= 3
      2259275.43     13343049.28      2259344.87     13343743.74
      2259115.71     13344146.49
#Sta/Elev= 30
  4633.1  166.32  4660.3  165.08    4902  156.57  4912.2  155.27  4972.4  152.67
  4982.4  153.13  4999.5  151.89  5002.3  151.39  5005.5  151.89  5022.6  152.93
  5153.3  152.57  5193.5  153.25  5233.7  155.29  5273.9  154.77    5304  156.42
  5330.1  159.32  5337.9  158.38  5375.3  160.23  5434.4  161.22    5456   159.8
  5461.8  158.51  5520.9  158.33  5542.5  159.42  5574.2  162.87  5606.8  161.88
  5660.7  162.07  5698.2  164.73  5741.4  162.57    5763  162.39  5794.4  163.75
#Mann= 5 ,-1 , 0
  4633.1     .05       0  4660.3      .1       0  4999.5     .07       0
  5005.5      .1       0  5606.8     .05       0
Bank Sta=4982.4,5022.6
XS Rating Curve= 0 ,0
Exp/Cntr=0.3,0.1