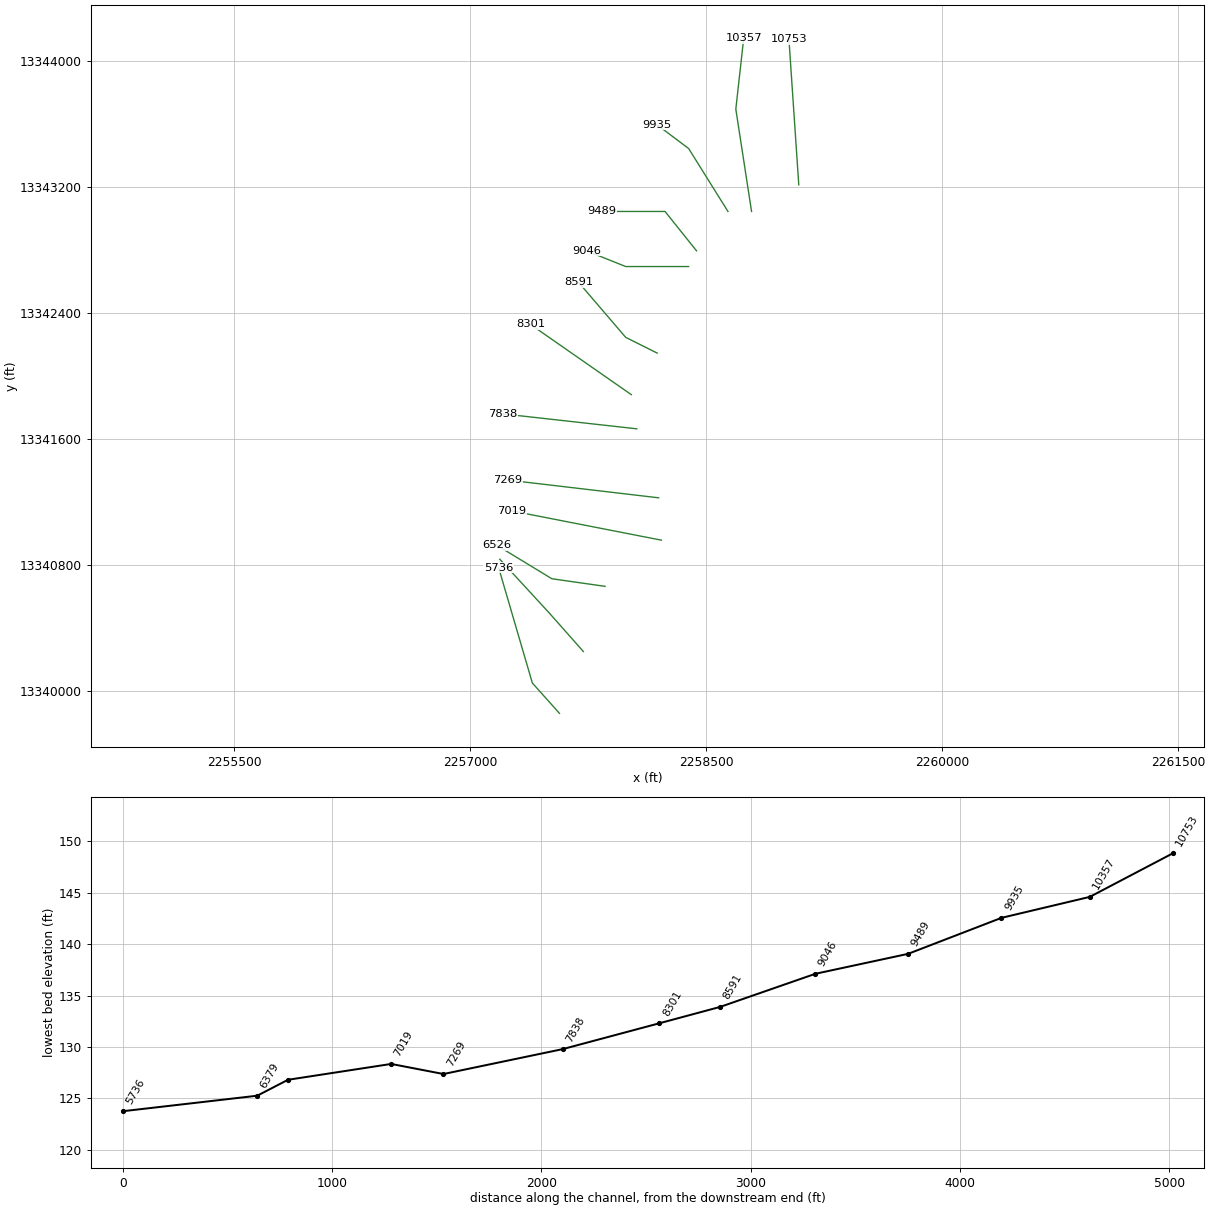
HEC-RAS study UNT038 IN SPCR.prj: UNT038 IN SPCR Base Level Engineering

--- UNT038 IN SPCR.g01 (geometry) --- (continued)

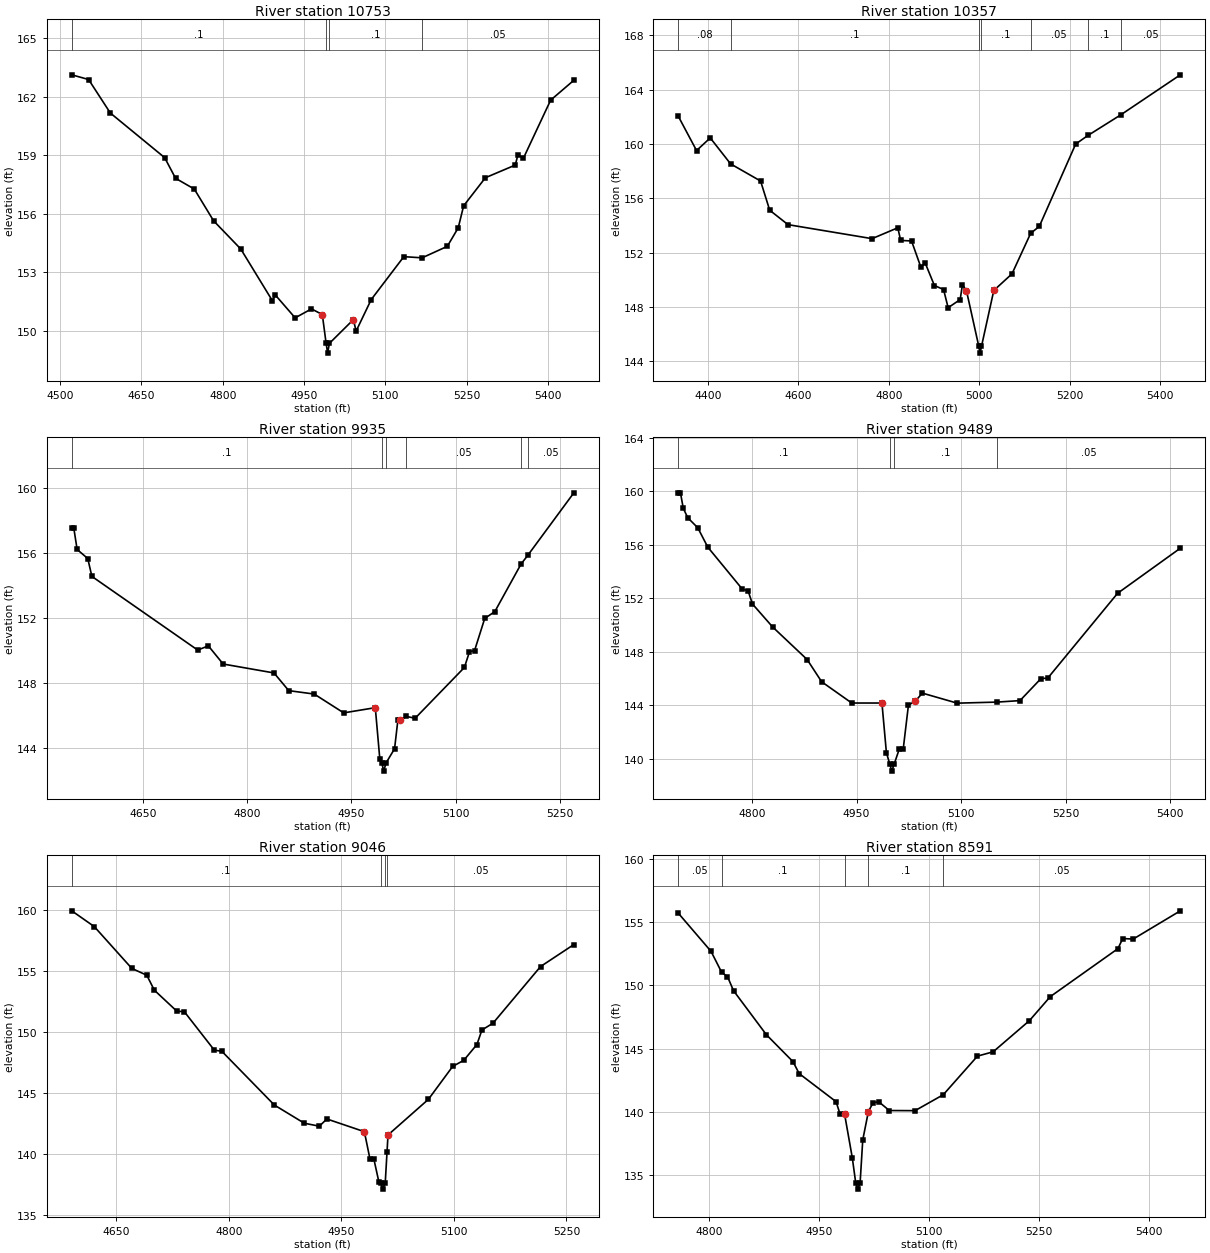
Type RM Length L Ch R = 1 ,10753   ,396,396,396
BEGIN DESCRIPTION:
UNT038 IN SPCR 19.0
END DESCRIPTION:
XS GIS Cut Line= 2
      2259087.93     13343215.91      2259025.42      13344139.6
#Sta/Elev= 30
  4521.7  163.12  4552.7  162.88  4592.8  161.16    4693  158.87  4713.1  157.81
  4747.6  157.26  4783.2  155.63  4833.4  154.18  4891.8  151.52  4896.8  151.83
  4933.6  150.65  4963.7  151.11  4983.7  150.82  4990.7  149.34  4993.5  148.84
  4996.7  149.34    5041  150.56    5046  149.97  5073.9  151.59    5134  153.79
  5167.7  153.73  5214.2  154.32  5234.3  155.27  5244.3   156.4  5284.4  157.84
  5339.5  158.49  5344.5  159.03  5354.5  158.84  5404.7  161.82  5447.5  162.84
#Mann= 4 ,-1 , 0
  4521.7      .1       0  4990.7     .07       0  4996.7      .1       0
  5167.7     .05       0
Bank Sta=4983.7,5041
XS Rating Curve= 0 ,0
Exp/Cntr=0.3,0.1

Type RM Length L Ch R = 1 ,10357   ,422,422,422
BEGIN DESCRIPTION:
UNT038 IN SPCR 18.0
END DESCRIPTION:
XS GIS Cut Line= 3
      2258787.72     13343046.88      2258687.72     13343696.85
      2258737.72     13344146.86
#Sta/Elev= 30
  4334.1  162.04  4374.6  159.51  4404.9  160.44  4449.9  158.53  4516.2  157.27
  4536.4  155.12  4576.9  154.06  4762.8  153.03  4819.7  153.83    4826   152.9
  4850.1  152.86  4870.3  150.97  4880.4  151.23  4900.7  149.58  4920.9  149.29
    4931  147.95  4957.6  148.55  4962.6  149.63  4971.5  149.21  4998.8  145.11
  5001.5  144.61  5004.8  145.11    5032  149.22  5072.2  150.44  5113.5  153.42
  5132.6  153.93  5213.1  159.99  5240.2  160.62    5313  162.14  5444.5  165.08
#Mann= 7 ,-1 , 0
  4334.1     .08       0  4449.9      .1       0  4998.8     .07       0
  5004.8      .1       0  5113.5     .05       0  5240.2      .1       0
    5313     .05       0
Bank Sta=4971.5,5032
XS Rating Curve= 0 ,0
Exp/Cntr=0.3,0.1

Type RM Length L Ch R = 1 ,9935    ,446,446,446
BEGIN DESCRIPTION:
UNT038 IN SPCR 17.0
END DESCRIPTION:
XS GIS Cut Line= 3
      2258637.72     13343046.86      2258387.72     13343446.85
      2258187.71     13343596.86
#Sta/Elev= 30
    4548  157.55  4550.9  157.55  4555.7  156.23    4571  155.67  4576.9  154.57
    4729  150.03  4744.3  150.29  4765.6  149.17  4838.7  148.62  4859.9  147.53
  4896.5  147.32  4938.9  146.16  4984.3  146.48  4990.8  143.31  4993.7  143.07
  4996.4  142.57  4999.7  143.07    5012  143.95  5016.7  145.69  5019.7  145.69
  5029.1  145.94  5041.6  145.83  5112.4  148.96  5119.7  149.93    5127     150
  5141.6  151.98  5156.1   152.4  5193.8  155.33  5203.7  155.88  5269.7  159.72
#Mann= 6 ,-1 , 0
    4548      .1       0  4993.7     .07       0  4999.7      .1       0
  5029.1     .05       0  5193.8      .1       0  5203.7     .05       0
Bank Sta=4984.3,5019.7
XS Rating Curve= 0 ,0
Exp/Cntr=0.3,0.1

Type RM Length L Ch R = 1 ,9489    ,443,443,443
BEGIN DESCRIPTION:
UNT038 IN SPCR 16.0
END DESCRIPTION:
XS GIS Cut Line= 3
      2258437.73     13342796.84      2258237.72     13343046.85
       2257837.7     13343046.85
#Sta/Elev= 30
  4694.2  159.87  4697.4  159.87  4701.4  158.72  4707.8  158.01  4722.2  157.26
  4736.6  155.81  4786.3  152.66  4794.3  152.56  4800.7  151.56  4829.5  149.85
  4879.1  147.41  4899.9  145.75  4943.1  144.16  4986.4  144.16  4992.8  140.45
  4997.8  139.57  5000.5  139.07  5003.8  139.57  5011.2  140.71  5016.9  140.71
  5024.4     144  5034.4  144.31  5044.4   144.9  5094.4  144.15  5151.7  144.23
  5184.4  144.34  5214.4  145.98  5224.4  146.03  5324.4  152.36  5414.4  155.73
#Mann= 4 ,-1 , 0
  4694.2      .1       0  4997.8     .07       0  5003.8      .1       0
  5151.7     .05       0
Bank Sta=4986.4,5034.4
XS Rating Curve= 0 ,0
Exp/Cntr=0.3,0.1

Type RM Length L Ch R = 1 ,9046    ,455,455,455
BEGIN DESCRIPTION:
UNT038 IN SPCR 15.0
END DESCRIPTION:
XS GIS Cut Line= 3
      2258387.69     13342696.85      2257987.72     13342696.85
      2257737.75     13342796.85
#Sta/Elev= 30
  4590.7   159.9  4620.7  158.61  4670.7  155.19  4690.7  154.63  4700.7  153.41
  4730.7  151.69  4740.7  151.65  4780.7   148.5  4790.7  148.41  4860.7  144.01
  4900.7  142.52  4920.7  142.28  4930.7  142.87  4980.7  141.83  4988.2  139.58
  4993.4  139.58  5000.1   137.7  5002.5  137.63  5005.2  137.13  5008.5  137.63
  5010.9  140.18  5012.2  141.56  5066.1  144.48  5098.4  147.17  5113.2  147.67
  5130.7  148.96  5137.4  150.15  5152.2  150.71  5215.5  155.34  5259.9  157.14
#Mann= 4 ,-1 , 0
  4590.7      .1       0  5002.5     .07       0  5008.5      .1       0
  5010.9     .05       0
Bank Sta=4980.7,5012.2
XS Rating Curve= 0 ,0
Exp/Cntr=0.3,0.1

Type RM Length L Ch R = 1 ,8591    ,290,290,290
BEGIN DESCRIPTION:
UNT038 IN SPCR 14.0
END DESCRIPTION:
XS GIS Cut Line= 3
       2258187.7     13342146.86      2257987.72     13342246.85
       2257687.7     13342596.88
#Sta/Elev= 30
  4758.1  155.72  4802.8   152.7  4817.4  151.03  4825.2  150.71  4833.5  149.59
  4878.3  146.11  4914.6  143.98    4923  143.04  4973.3  140.82  4978.9  139.81
    4985  139.81  4995.4   136.4  5000.1  134.41  5002.8  133.91  5006.1  134.41
  5009.7   137.8  5017.4  140.04  5023.9  140.75  5031.6  140.81  5045.9  140.12
    5081  140.11  5119.5  141.37  5166.1  144.42  5187.5  144.76  5236.9  147.22
  5265.4  149.12  5357.6  152.91  5364.2  153.71  5378.5  153.67  5442.7   155.9
#Mann= 5 ,-1 , 0
  4758.1     .05       0  4817.4      .1       0    4985     .07       0
  5017.4      .1       0  5119.5     .05       0
Bank Sta=4985,5017.4
XS Rating Curve= 0 ,0
Exp/Cntr=0.3,0.1

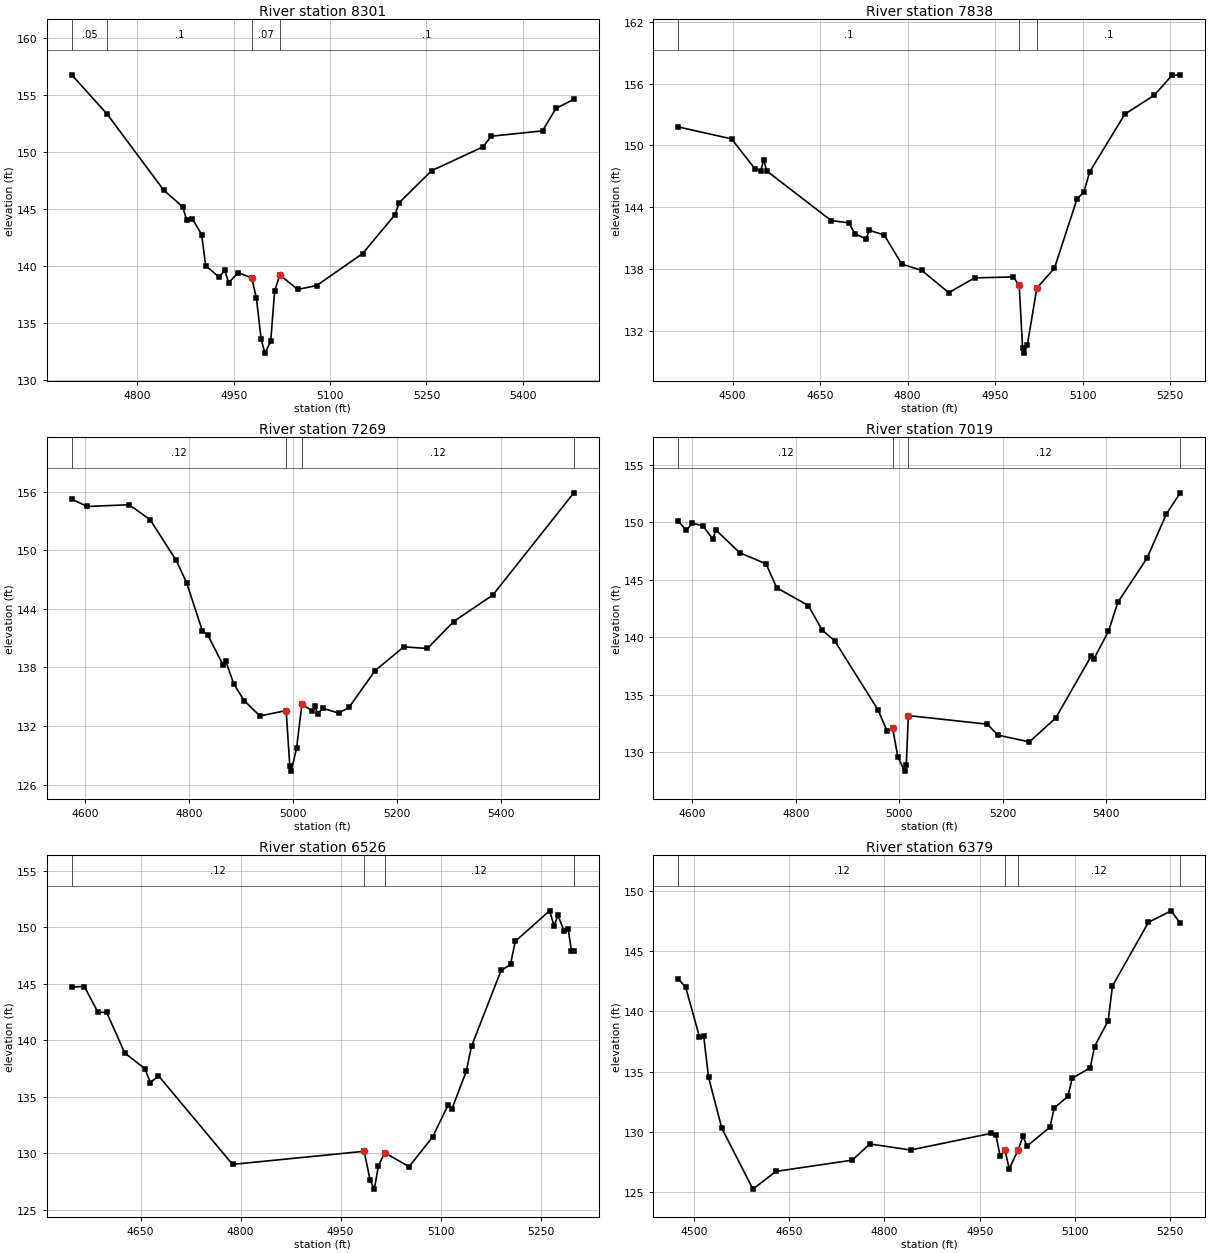
Type RM Length L Ch R = 1 ,8301    ,463,463,463
BEGIN DESCRIPTION:
UNT038 IN SPCR 13.0
END DESCRIPTION:
XS GIS Cut Line= 2
      2258023.69     13341882.63      2257381.99     13342329.21
#Sta/Elev= 30
  4697.8  156.75  4753.3  153.27  4840.8  146.64  4870.5  145.16  4876.6  144.04
  4885.4  144.13    4900  142.73  4906.3  139.99  4927.2     139    4936  139.58
  4942.1  138.51  4956.9  139.38  4977.9  138.93  4985.3  137.17  4992.7  133.53
  4998.6  132.32  5007.6  133.36  5013.7  137.77  5021.8  139.19  5049.4  137.91
  5079.1  138.25  5150.7  141.06  5201.3  144.48  5207.4  145.51    5258  148.33
  5338.3  150.43  5350.8  151.36  5430.8  151.83  5451.8  153.81  5479.6   154.6
#Mann= 4 ,-1 , 0
  4697.8     .05       0  4753.3      .1       0  4977.9     .07       0
  5021.8      .1       0
Bank Sta=4977.9,5021.8
XS Rating Curve= 0 ,0
Exp/Cntr=0.3,0.1

Type RM Length L Ch R = 1 ,7838    ,569,569,569
BEGIN DESCRIPTION:
UNT038 IN SPCR 12.0
END DESCRIPTION:
XS GIS Cut Line= 2
      2258058.43     13341665.61      2257203.34      13341761.1
#Sta/Elev= 30
  4406.8   151.8  4498.1  150.64  4538.3  147.73  4548.3  147.54  4553.3  148.63
  4558.4  147.52  4669.1  142.69  4699.3  142.47  4709.4  141.42  4728.9  140.89
    4734  141.75  4759.7  141.29  4789.9  138.46  4824.3  137.84  4870.4  135.68
  4914.6  137.12  4981.1  137.21  4991.1  136.38  4996.9   130.3  4999.7   129.8
    5005  130.59  5021.3  136.12  5051.5  138.06  5090.3  144.82  5101.8  145.45
  5111.9  147.43  5172.2  153.05  5222.5  154.88  5252.7  156.81  5267.2  156.87
#Mann= 3 , 0 , 0
  4406.8      .1       0  4991.1     .07       0  5021.3      .1       0
Bank Sta=4991.1,5021.3
XS Rating Curve= 0 ,0
Exp/Cntr=0.3,0.1

Type RM Length L Ch R = 1 ,7269    ,250,250,250
BEGIN DESCRIPTION:
UNT038 IN SPCR 11.0
END DESCRIPTION:
XS GIS Cut Line= 2
      2258197.27     13341227.25      2257238.09     13341340.09
#Sta/Elev= 30
  4573.7  155.23  4603.5  154.48    4684  154.66  4724.3  153.14  4774.6  148.96
  4794.8  146.65    4825  141.73    4835  141.35  4865.1  138.21  4870.1  138.61
  4885.4   136.3  4905.5  134.59  4935.7  133.03  4986.1  133.58  4993.1  127.88
  4995.9  127.38  5006.2  129.75  5016.3  134.21  5036.2  133.57  5041.3  134.08
  5046.5  133.26  5056.6  133.81  5086.8  133.33  5106.9   133.9  5157.2  137.67
  5212.4  140.11  5257.9  139.94  5308.3   142.7  5383.6  145.41  5539.5  155.88
#Mann= 4 ,-1 , 0
  4573.7     .12       0  4986.1     .07       0  5016.3     .12       0
  5539.5      .1       0
Bank Sta=4986.1,5016.3
XS Rating Curve= 0 ,0
Exp/Cntr=0.3,0.1

Type RM Length L Ch R = 1 ,7019    ,493,493,493
BEGIN DESCRIPTION:
UNT038 IN SPCR 10.0
END DESCRIPTION:
XS GIS Cut Line= 2
      2258214.65     13340958.15      2257261.29     13341144.49
#Sta/Elev= 30
  4572.6  150.11  4588.3  149.28    4600  149.92  4620.4  149.68  4639.9  148.51
    4645  149.34  4691.4  147.35  4742.7  146.37  4763.1   144.3  4824.2  142.75
  4851.1  140.62  4875.1   139.7  4959.3  133.67    4977  131.81  4987.2  132.14
  4997.4  129.61  5010.6  128.36  5013.8  128.86  5017.8  133.19  5170.6  132.44
    5191  131.49  5252.1   130.9  5303.1  132.99  5371.6  138.36  5376.7  138.11
    5405  140.51  5423.1  143.03  5479.8  146.89  5517.1  150.72    5544  152.55
#Mann= 4 ,-1 , 0
  4572.6     .12       0  4987.2     .07       0  5017.8     .12       0
    5544      .1       0
Bank Sta=4987.2,5017.8
XS Rating Curve= 0 ,0
Exp/Cntr=0.3,0.1

Type RM Length L Ch R = 1 ,6526    ,147,147,147
BEGIN DESCRIPTION:
UNT038 IN SPCR 9.0
END DESCRIPTION:
XS GIS Cut Line= 3
      2257856.45     13340664.71      2257518.41       13340713.
      2257166.58     13340926.86
#Sta/Elev= 30
  4546.8  144.72  4565.7  144.76  4585.9  142.49  4599.2  142.46  4626.3  138.87
  4656.6  137.48  4664.8  136.24  4676.8  136.86    4788  129.01  4985.4  130.17
  4994.4  127.61  5000.7  126.82  5006.8  128.89  5016.4  130.03  5052.9  128.81
    5088  131.43  5111.3  134.25  5117.2  133.93  5138.5  137.24  5146.5  139.47
  5190.8  146.18    5205  146.71  5212.1  148.76  5263.6  151.46  5270.3  150.13
  5276.1  151.06  5285.7  149.64  5291.6  149.81  5296.4  147.89    5300  147.89
#Mann= 4 ,-1 , 0
  4546.8     .12       0  4985.4     .07       0  5016.4     .12       0
    5300      .1       0
Bank Sta=4985.4,5016.4
XS Rating Curve= 0 ,0
Exp/Cntr=0.3,0.1

Type RM Length L Ch R = 1 ,6379    ,643,643,643
BEGIN DESCRIPTION:
Mapping XS 2f98196a
END DESCRIPTION:
XS GIS Cut Line= 3
      2257718.46     13340250.83      2257504.61     13340492.26
      2257187.29     13340837.18
#Sta/Elev= 30
    4475  142.69  4486.7     142  4508.5  137.87  4515.1  137.96  4522.7  134.55
  4543.6  130.32  4592.7  125.27  4628.9  126.74  4749.3  127.67  4776.9  129.01
  4841.2  128.51  4968.2  129.89  4975.6  129.73  4982.4  127.99  4989.8  128.51
  4996.6  126.95  5010.7  128.53  5018.1  129.63  5024.9  128.84  5060.7   130.4
  5067.5  131.99    5089  132.95  5095.8  134.45  5124.2  135.32    5131  137.08
  5152.5  139.22  5159.3   142.1    5216  147.37  5251.8  148.32  5266.2  147.28
#Mann= 4 ,-1 , 0
    4475     .12       0  4989.8     .07       0  5010.7     .12       0
  5266.2      .1       0
Bank Sta=4989.8,5010.7
XS Rating Curve= 0 ,0
Exp/Cntr=0.3,0.1

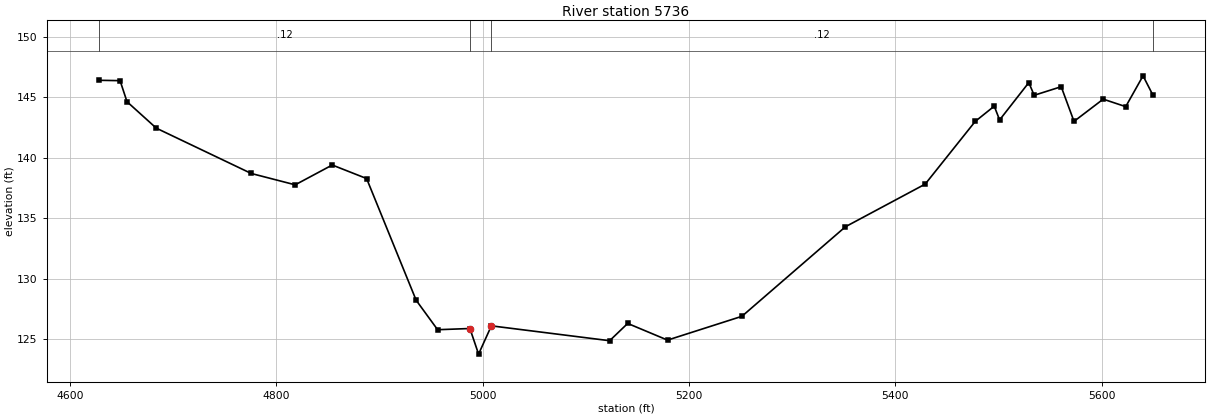
Type RM Length L Ch R = 1 ,5736    ,549,549,549
BEGIN DESCRIPTION:
UNT038 IN SPCR 8.0
END DESCRIPTION:
XS GIS Cut Line= 3
      2257566.73     13339857.59      2257394.24     13340050.78
      2257180.41     13340781.97
#Sta/Elev= 30
  4628.6  146.42  4648.7  146.39  4655.4  144.65  4683.8  142.46  4775.8  138.71
  4818.4  137.77  4854.3  139.41  4887.6  138.29  4935.6  128.22  4956.4  125.78
  4987.7  125.88  4996.1  123.76  5008.5   126.1  5123.1  124.87  5140.6   126.3
  5179.2  124.92  5251.3  126.89  5351.6   134.3  5428.9  137.83  5477.4  143.02
  5495.8  144.28    5501  143.14  5529.3  146.23  5534.5  145.18  5560.7  145.89
  5573.1  143.02  5601.4  144.86  5623.2  144.24    5640  146.79  5649.4  145.22
#Mann= 4 ,-1 , 0
  4628.6     .12       0  4987.7     .07       0  5008.5     .12       0
  5649.4      .1       0
Bank Sta=4987.7,5008.5
XS Rating Curve= 0 ,0
Exp/Cntr=0.3,0.1

Chan Stop Cuts=-1
Use User Specified Reach Order=0
Composite Channel Slope=5