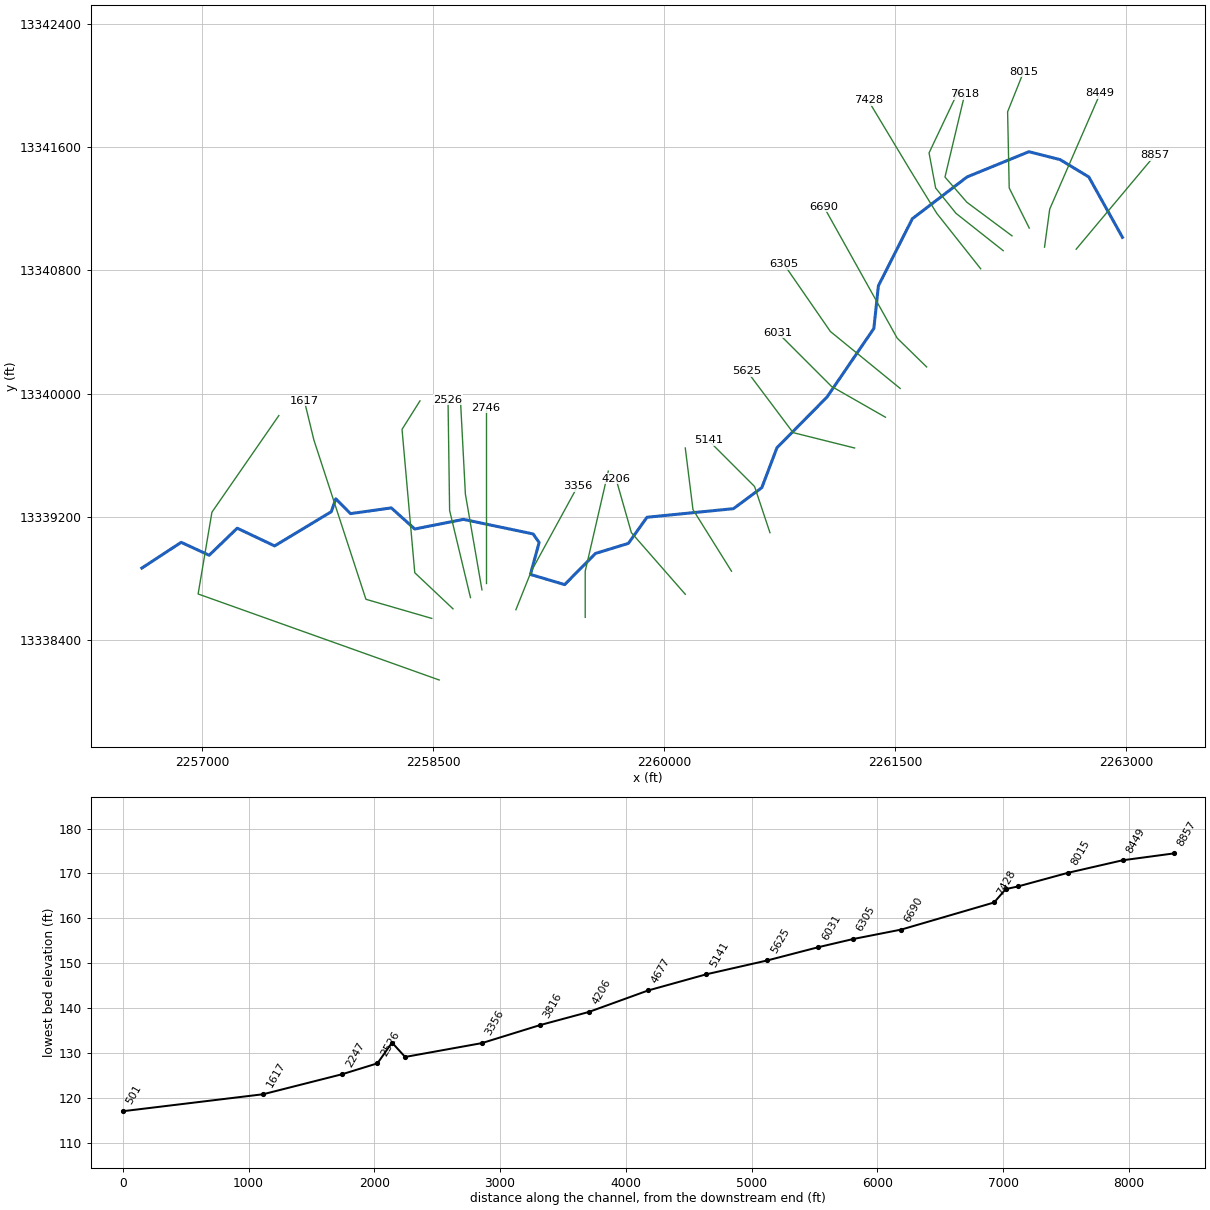
--- UNT039 IN SPCR.prj (project) ---

Proj Title=UNT039 IN SPCR Base Level Engineering
Current Plan=p01
Default Exp/Contr=0.3,0.1
English Units
Geom File=g01
Flow File=f01
Plan File=p01
BEGIN DESCRIPTION:
UNT039 IN SPCR
END DESCRIPTION:

--- UNT039 IN SPCR.p01 (plan) ---

Plan Title=Multiple Run
Short Identifier=Multiple
Geom File=g01
Flow File=f01
Subcritical Flow
K Sum by GR= 0
Std Step Tol= 0.01
Critical Tol= 0.01
Num of Std Step Trials= 20
Max Error Tol= 0.3
Flow Tol Ratio= 0.001
Split Flow NTrial= 30
Split Flow Tol= 0.02
Split Flow Ratio= 0.02
Log Output Level= 0
Friction Slope Method= 1
Unsteady Friction Slope Method= 2
Unsteady Bridges Friction Slope Method= 1
Parabolic Critical Depth
Global Vel Dist=  1 , 1 , 1
Global Log Level= 0
CheckData=True
Encroach Param= -1, 0, 0, 0
BEGIN DESCRIPTION:
Multiple Run
END DESCRIPTION:

--- UNT039 IN SPCR.f01 (steady flow) ---

Flow Title=Multiple
Number of Profiles=7
Profile Names=10-year,25-year,50-year,1pct_min,100-year,1pct_plu,500-year
River Rch & RM= UNT039 IN SPCR,Reach-1,8857
     165     222     268     238     323     436     473
River Rch & RM= UNT039 IN SPCR,Reach-1,6690
     278     387     478     434     588     795     901
Boundary for River Rch & Prof#=UNT039 IN SPCR,Reach-1,1
Up Type=0
Dn Type=3
Dn Slope=0.005
Boundary for River Rch & Prof#=UNT039 IN SPCR,Reach-1,2
Up Type=0
Dn Type=3
Dn Slope=0.005
Boundary for River Rch & Prof#=UNT039 IN SPCR,Reach-1,3
Up Type=0
Dn Type=3
Dn Slope=0.005
Boundary for River Rch & Prof#=UNT039 IN SPCR,Reach-1,4
Up Type=0
Dn Type=3
Dn Slope=0.005
Boundary for River Rch & Prof#=UNT039 IN SPCR,Reach-1,5
Up Type=0
Dn Type=3
Dn Slope=0.005
Boundary for River Rch & Prof#=UNT039 IN SPCR,Reach-1,6
Up Type=0
Dn Type=3
Dn Slope=0.005
Boundary for River Rch & Prof#=UNT039 IN SPCR,Reach-1,7
Up Type=0
Dn Type=3
Dn Slope=0.005

--- UNT039 IN SPCR.g01 (geometry) ---

Geom Title=Existing Conditions

River Reach=UNT039 IN SPCR,Reach-1
Reach XY= 30
      2262977.24     13341015.36      2262758.67     13341407.50
      2262572.24     13341520.00      2262369.74     13341571.43
      2261967.95     13341407.50      2261612.58     13341136.06
      2261392.05     13340700.31      2261362.58     13340423.38
      2261057.89     13339977.20      2260733.27     13339648.87
      2260634.68     13339389.20      2260450.63     13339252.89
      2259888.82     13339196.94      2259767.89     13339027.22
      2259554.71     13338962.11      2259354.23     13338759.61
      2259132.00     13338825.58      2259188.43     13339033.05
      2259149.36     13339088.60      2258696.76     13339183.37
      2258380.35     13339120.87      2258228.40     13339257.76
      2257962.68     13339220.63      2257867.72     13339316.86
      2257838.37     13339233.01      2257470.37     13339010.96
      2257227.47     13339125.99      2257045.19     13338950.42
      2256863.37     13339034.13      2256607.72     13338866.85

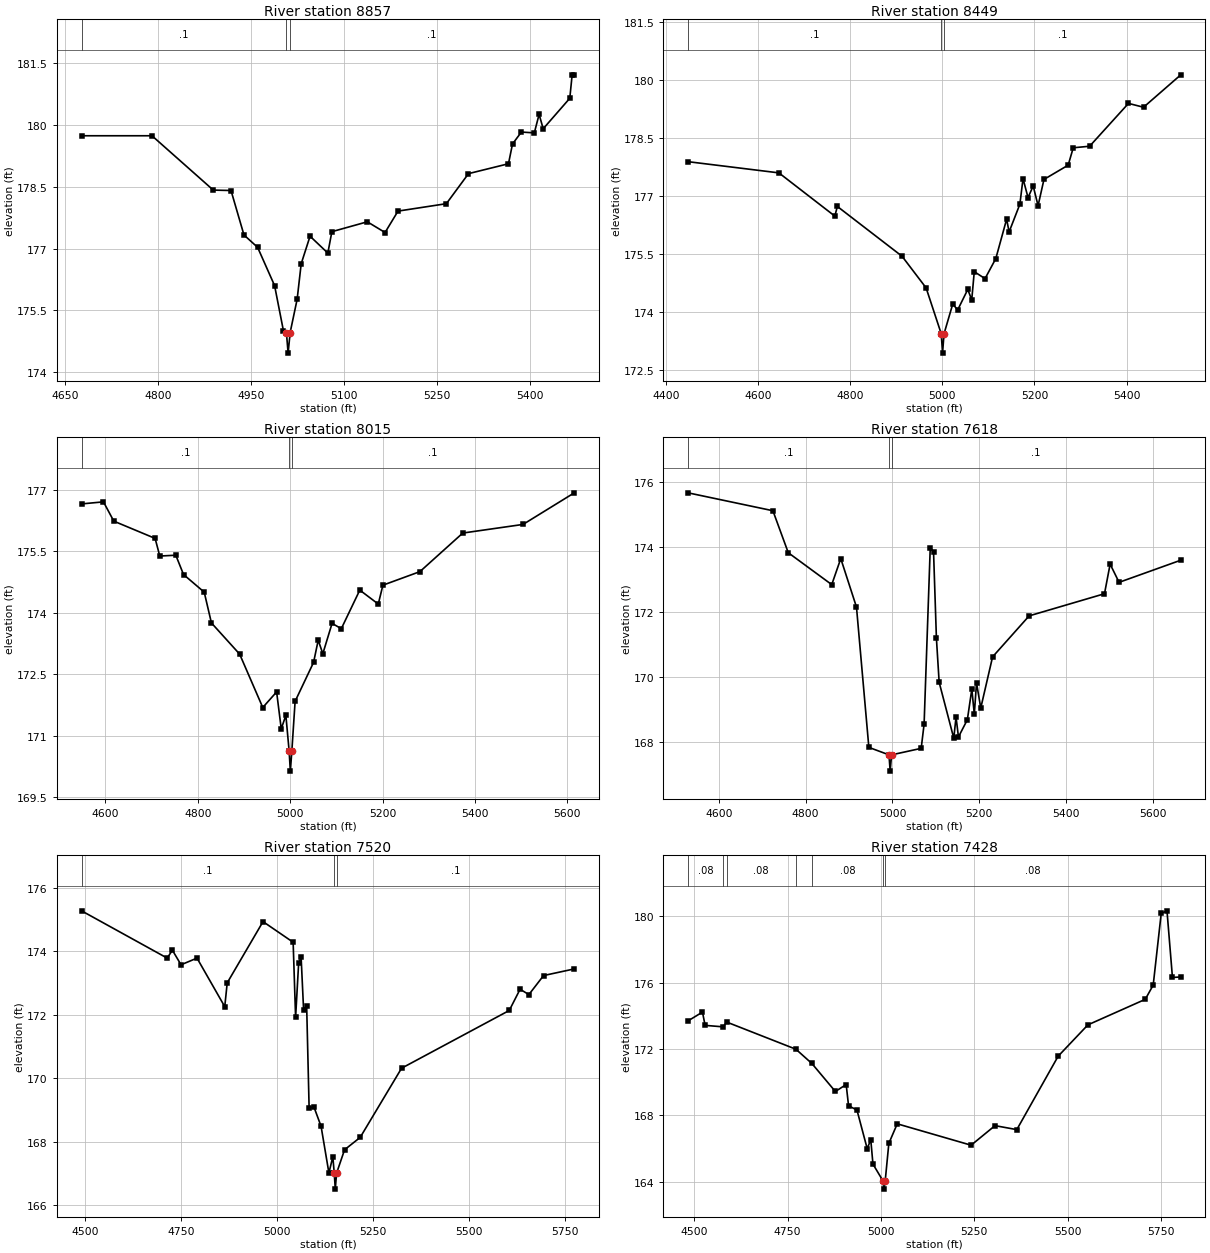
Type RM Length L Ch R = 1,8857,408,408,408
BEGIN DESCRIPTION:
UNT039 IN SPCR 29.0
END DESCRIPTION:
XS GIS Cut Line= 2
      2262676.79     13340938.33      2263187.20     13341547.71
#Sta/Elev= 30
  4677.0  179.74  4790.6  179.74  4889.5  178.42  4918.1  178.41  4939.0  177.33
  4961.0  177.03  4988.4  176.10  5002.7  175.00  5007.5  174.96  5010.2  174.46
  5013.5  174.96  5024.8  175.77  5031.3  176.63  5045.6  177.30  5074.3  176.89
  5080.8  177.41  5138.0  177.65  5166.6  177.39  5187.5  177.91  5265.5  178.09
  5301.2  178.82  5365.7  179.06  5372.2  179.54  5386.5  179.83  5407.4  179.81
  5415.1  180.26  5421.7  179.91  5464.6  180.65  5468.4  181.22  5471.9  181.22
#Mann=3,-1,0
  4677.0     0.1       0  5007.5    0.07       0  5013.5     0.1       0
Bank Sta=5007.5,5013.5
Exp/Cntr=0.3,0.1

Type RM Length L Ch R = 1,8449,434,434,434
BEGIN DESCRIPTION:
UNT039 IN SPCR 13.0
END DESCRIPTION:
XS GIS Cut Line= 3
      2262471.06     13340951.33      2262504.92     13341198.76
      2262832.90     13341951.03
#Sta/Elev= 30
  4447.5  177.89  4644.9  177.60  4766.4  176.48  4771.9  176.73  4912.4  175.44
  4964.7  174.62  4997.6  173.43  5000.4  172.93  5003.6  173.43  5022.5  174.20
  5033.3  174.05  5055.2  174.58  5063.8  174.31  5069.3  175.04  5092.7  174.86
  5116.1  175.38  5139.6  176.40  5145.0  176.07  5168.4  176.79  5175.2  177.45
  5186.1  176.96  5197.3  177.26  5207.9  176.75  5220.7  177.43  5273.3  177.80
  5284.3  178.25  5319.9  178.29  5404.3  179.40  5437.0  179.30  5517.9  180.14
#Mann=3,-1,0
  4447.5     0.1       0  4997.6    0.07       0  5003.6     0.1       0
Bank Sta=4997.6,5003.6
Exp/Cntr=0.3,0.1

Type RM Length L Ch R = 1,8015,397,397,397
BEGIN DESCRIPTION:
Mapping XS 84a860ff
END DESCRIPTION:
XS GIS Cut Line= 4
      2262371.94     13341075.43      2262241.75     13341335.81
      2262231.33     13341830.60      2262335.50     13342091.02
#Sta/Elev= 30
  4548.5  176.65  4595.9  176.70  4618.3  176.23  4707.7  175.81  4717.8  175.38
  4752.5  175.40  4769.2  174.93  4814.0  174.50  4829.6  173.75  4890.7  172.99
  4940.7  171.69  4970.7  172.07  4980.7  171.17  4990.7  171.50  4997.7  170.64
  5000.4  170.14  5003.7  170.64  5010.7  171.84  5050.7  172.79  5060.7  173.33
  5070.7  173.00  5090.7  173.74  5110.7  173.61  5150.7  174.55  5190.7  174.21
  5200.7  174.67  5280.8  175.00  5373.6  175.94  5504.0  176.15  5615.0  176.92
#Mann=3,-1,0
  4548.5     0.1       0  4997.7    0.07       0  5003.7     0.1       0
Bank Sta=4997.7,5003.7
Exp/Cntr=0.3,0.1

Type RM Length L Ch R = 1,7618,98,98,98
BEGIN DESCRIPTION:
Mapping XS 91c71d03
END DESCRIPTION:
XS GIS Cut Line= 4
      2262259.62     13341025.08      2261967.19     13341242.62
      2261824.54     13341406.67      2261952.94     13341945.21
#Sta/Elev= 30
  4528.9  175.66  4724.5  175.11  4759.9  173.82  4860.1  172.84  4880.9  173.64
  4917.1  172.15  4945.6  167.84  4992.0  167.61  4994.7  167.11  4998.0  167.61
  5066.2  167.81  5072.9  168.55  5087.1  173.98  5094.7  173.84  5101.3  171.19
  5107.6  169.84  5141.3  168.12  5146.5  168.77  5152.1  168.16  5172.6  168.69
  5182.9  169.63  5188.6  168.86  5193.7  169.82  5203.5  169.05  5230.7  170.62
  5315.0  171.88  5488.6  172.56  5501.6  173.47  5522.2  172.91  5664.4  173.59
#Mann=3,-1,0
  4528.9     0.1       0  4992.0    0.07       0  4998.0     0.1       0
Bank Sta=4992,4998
Exp/Cntr=0.3,0.1

Type RM Length L Ch R = 1,7520,92,92,92
BEGIN DESCRIPTION:
Mapping XS 6c3b4768
END DESCRIPTION:
XS GIS Cut Line= 5
      2262202.60     13340928.76      2261895.87     13341171.29
      2261763.92     13341335.34      2261721.12     13341563.59
      2261913.21     13341969.11
#Sta/Elev= 30
  4490.8  175.28  4713.7  173.79  4727.2  174.04  4749.7  173.58  4791.3  173.79
  4863.5  172.26  4869.9  173.01  4963.1  174.94  5041.5  174.29  5047.9  171.92
  5055.8  173.63  5062.3  173.81  5068.7  172.16  5076.7  172.28  5083.1  169.06
  5095.6  169.10  5114.2  168.49  5134.6  167.02  5144.8  167.53  5148.5  167.01
  5151.2  166.51  5154.5  167.01  5175.3  167.75  5216.0  168.14  5323.7  170.32
  5604.0  172.14  5632.2  172.81  5655.0  172.64  5693.3  173.24  5773.3  173.45
#Mann=3,-1,0
  4490.8     0.1       0  5148.5    0.07       0  5154.5     0.1       0
Bank Sta=5148.5,5154.5
Exp/Cntr=0.3,0.1

Type RM Length L Ch R = 1,7428,738,738,738
BEGIN DESCRIPTION:
Mapping XS e1cb62f2
END DESCRIPTION:
XS GIS Cut Line= 4
      2262056.38     13340811.07      2261771.05     13341171.29
      2261599.86     13341449.47      2261325.25     13341905.97
#Sta/Elev= 30
  4483.6  173.69  4522.3  174.22  4529.3  173.42  4577.8  173.33  4587.0  173.62
  4772.4  171.98  4815.1  171.12  4878.0  169.43  4906.9  169.85  4913.3  168.57
  4935.8  168.31  4963.2  165.98  4972.7  166.53  4978.6  165.05  5005.4  164.04
  5008.1  163.54  5011.4  164.04  5021.1  166.30  5043.6  167.48  5241.3  166.19
  5305.3  167.37  5363.6  167.13  5474.3  171.56  5553.9  173.45  5707.4  174.99
  5728.7  175.85  5750.1  180.17  5765.6  180.33  5780.2  176.31  5802.5  176.34
#Mann=7,-1,0
  4483.6    0.08       0  4577.8     0.1       0  4587.0    0.08       0
  4772.4     0.1       0  4815.1    0.08       0  5005.4    0.07       0
  5011.4    0.08       0
Bank Sta=5005.4,5011.4
Exp/Cntr=0.3,0.1

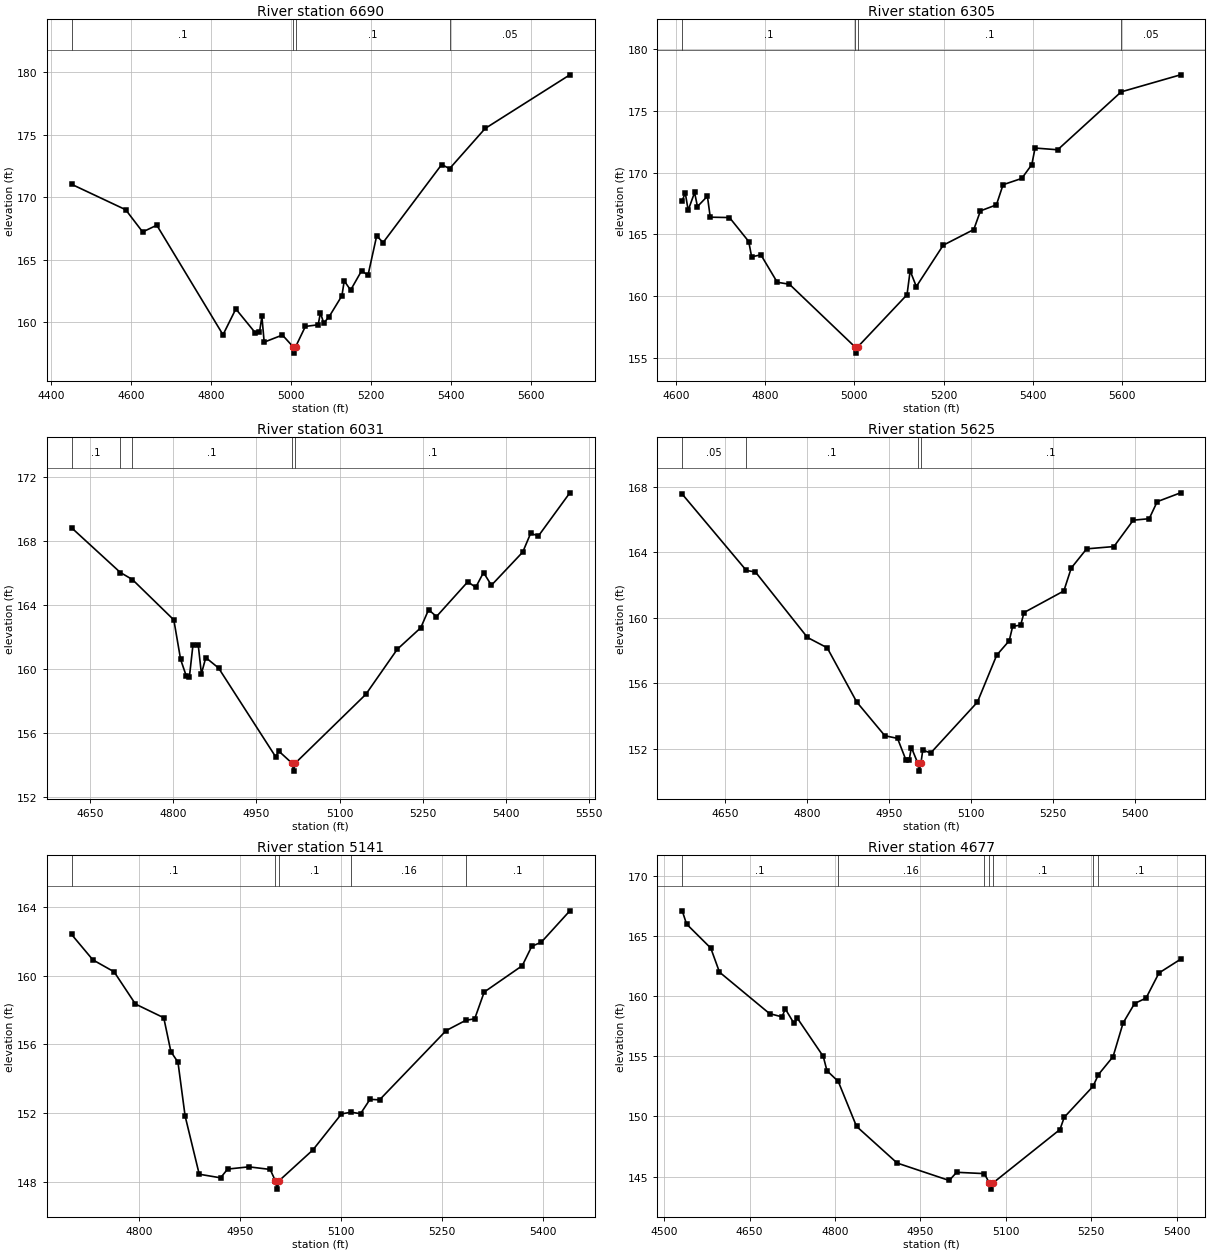
Type RM Length L Ch R = 1,6690,385,385,385
BEGIN DESCRIPTION:
UNT039 IN SPCR 12.0
END DESCRIPTION:
XS GIS Cut Line= 3
      2261705.34     13340173.58      2261514.36     13340360.22
      2261037.87     13341213.57
#Sta/Elev= 30
  4452.1  171.04  4587.2  169.00  4629.6  167.22  4664.9  167.76  4830.3  158.98
  4862.3  161.05  4911.4  159.12  4921.4  159.18  4927.4  160.45  4933.1  158.39
  4978.7  158.96  5005.5  158.01  5008.3  157.51  5011.5  158.01  5036.0  159.65
  5067.9  159.78  5073.6  160.74  5081.8  159.92  5095.3  160.43  5127.3  162.11
  5133.0  163.30  5149.0  162.56  5176.4  164.11  5192.4  163.75  5214.1  166.91
  5230.1  166.37  5376.4  172.62  5396.1  172.29  5484.9  175.51  5696.5  179.81
#Mann=4,-1,0
  4452.1     0.1       0  5005.5    0.07       0  5011.5     0.1       0
  5396.1    0.05       0
Bank Sta=5005.5,5011.5
Exp/Cntr=0.3,0.1

Type RM Length L Ch R = 1,6305,274,274,274
BEGIN DESCRIPTION:
Mapping XS a035cd32
END DESCRIPTION:
XS GIS Cut Line= 3
      2261533.38     13340033.75      2261080.29     13340403.51
      2260778.20     13340841.03
#Sta/Elev= 30
  4614.3  167.74  4621.1  168.37  4627.6  166.96  4642.0  168.40  4648.4  167.26
  4670.7  168.10  4677.1  166.40  4720.2  166.37  4763.3  164.43  4769.8  163.19
  4790.6  163.35  4827.2  161.13  4854.5  160.97  5001.5  155.89  5004.3  155.39
  5007.5  155.89  5118.0  160.12  5125.0  162.06  5138.8  160.78  5199.1  164.13
  5267.6  165.40  5282.5  166.91  5318.3  167.40  5333.2  169.03  5375.1  169.54
  5397.6  170.66  5404.9  172.00  5455.6  171.86  5597.9  176.55  5730.8  177.93
#Mann=4,-1,0
  4614.3     0.1       0  5001.5    0.07       0  5007.5     0.1       0
  5597.9    0.05       0
Bank Sta=5001.5,5007.5
Exp/Cntr=0.3,0.1

Type RM Length L Ch R = 1,6031,406,406,406
BEGIN DESCRIPTION:
UNT039 IN SPCR 11.0
END DESCRIPTION:
XS GIS Cut Line= 3
      2261437.73     13339846.85      2261087.72     13340046.85
      2260737.72     13340396.86
#Sta/Elev= 30
  4616.7  168.83  4704.6  166.03  4726.3  165.59  4801.0  163.06  4813.2  160.59
  4823.3  159.56  4829.1  159.50  4835.5  161.50  4844.9  161.52  4850.7  159.69
  4858.6  160.70  4881.6  160.05  4984.5  154.49  4990.3  154.84  5013.9  154.09
  5016.7  153.59  5019.9  154.09  5147.1  158.40  5203.7  161.22  5246.1  162.57
  5260.2  163.70  5274.4  163.27  5330.9  165.45  5345.1  165.10  5359.2  166.03
  5373.4  165.23  5429.9  167.31  5444.1  168.48  5458.2  168.32  5514.8  171.02
#Mann=5,-1,0
  4616.7     0.1       0  4704.6    0.05       0  4726.3     0.1       0
  5013.9    0.07       0  5019.9     0.1       0
Bank Sta=5013.9,5019.9
Exp/Cntr=0.3,0.1

Type RM Length L Ch R = 1,5625,484,484,484
BEGIN DESCRIPTION:
UNT039 IN SPCR 10.0
END DESCRIPTION:
XS GIS Cut Line= 3
      2261237.68     13339646.86      2260837.72     13339746.85
      2260537.70     13340146.88
#Sta/Elev= 30
  4571.6  167.55  4689.0  162.89  4705.6  162.80  4800.9  158.80  4837.0  158.17
  4891.1  154.86  4942.6  152.80  4965.8  152.64  4981.3  151.31  4987.0  151.31
  4991.2  152.08  5002.7  151.14  5005.5  150.64  5008.7  151.14  5012.0  151.92
  5026.6  151.75  5112.0  154.85  5147.4  157.72  5170.3  158.60  5176.6  159.48
  5191.2  159.55  5197.4  160.32  5270.3  161.64  5283.9  163.04  5312.0  164.21
  5362.0  164.35  5397.4  165.96  5426.6  166.05  5441.2  167.09  5483.9  167.63
#Mann=4,-1,0
  4571.6    0.05       0  4689.0     0.1       0  5002.7    0.07       0
  5008.7     0.1       0
Bank Sta=5002.7,5008.7
Exp/Cntr=0.3,0.1

Type RM Length L Ch R = 1,5141,464,464,464
BEGIN DESCRIPTION:
UNT039 IN SPCR 9.0
END DESCRIPTION:
XS GIS Cut Line= 3
      2260687.72     13339096.85      2260587.72     13339396.85
      2260287.72     13339696.86
#Sta/Elev= 30
  4699.2  162.42  4730.8  160.94  4762.4  160.24  4794.1  158.36  4836.2  157.56
  4846.8  155.58  4857.3  154.97  4867.9  151.83  4888.9  148.43  4920.6  148.22
  4931.1  148.73  4962.7  148.86  4994.3  148.71  5001.9  148.06  5004.6  147.56
  5007.9  148.06  5057.9  149.85  5100.3  151.95  5114.7  152.05  5128.6  151.96
  5142.7  152.80  5156.9  152.77  5255.8  156.81  5285.0  157.41  5298.3  157.50
  5312.4  159.06  5369.0  160.60  5383.1  161.73  5397.3  161.97  5439.7  163.80
#Mann=5,-1,0
  4699.2     0.1       0  5001.9    0.07       0  5007.9     0.1       0
  5114.7    0.16       0  5285.0     0.1       0
Bank Sta=5001.9,5007.9
Exp/Cntr=0.3,0.1

Type RM Length L Ch R = 1,4677,471,471,471
BEGIN DESCRIPTION:
UNT039 IN SPCR 8.0
END DESCRIPTION:
XS GIS Cut Line= 3
      2260437.71     13338846.87      2260187.72     13339246.85
      2260137.72     13339646.86
#Sta/Elev= 30
  4531.7  167.10  4539.3  166.00  4581.8  164.00  4597.1  162.00  4685.0  158.55
  4706.8  158.28  4712.7  158.94  4728.0  157.73  4733.9  158.16  4779.3  154.99
  4785.8  153.80  4805.6  152.91  4837.7  149.17  4909.0  146.12  5000.4  144.67
  5013.5  145.35  5062.2  145.24  5070.9  144.45  5073.7  143.95  5076.9  144.45
  5194.9  148.91  5202.4  149.93  5252.9  152.50  5262.4  153.48  5288.1  154.97
  5305.7  157.77  5325.9  159.39  5346.0  159.84  5368.7  161.93  5406.5  163.07
#Mann=7,-1,0
  4531.7     0.1       0  4805.6    0.16       0  5062.2     0.1       0
  5070.9    0.07       0  5076.9     0.1       0  5252.9    0.16       0
  5262.4     0.1       0
Bank Sta=5070.9,5076.9
Exp/Cntr=0.3,0.1

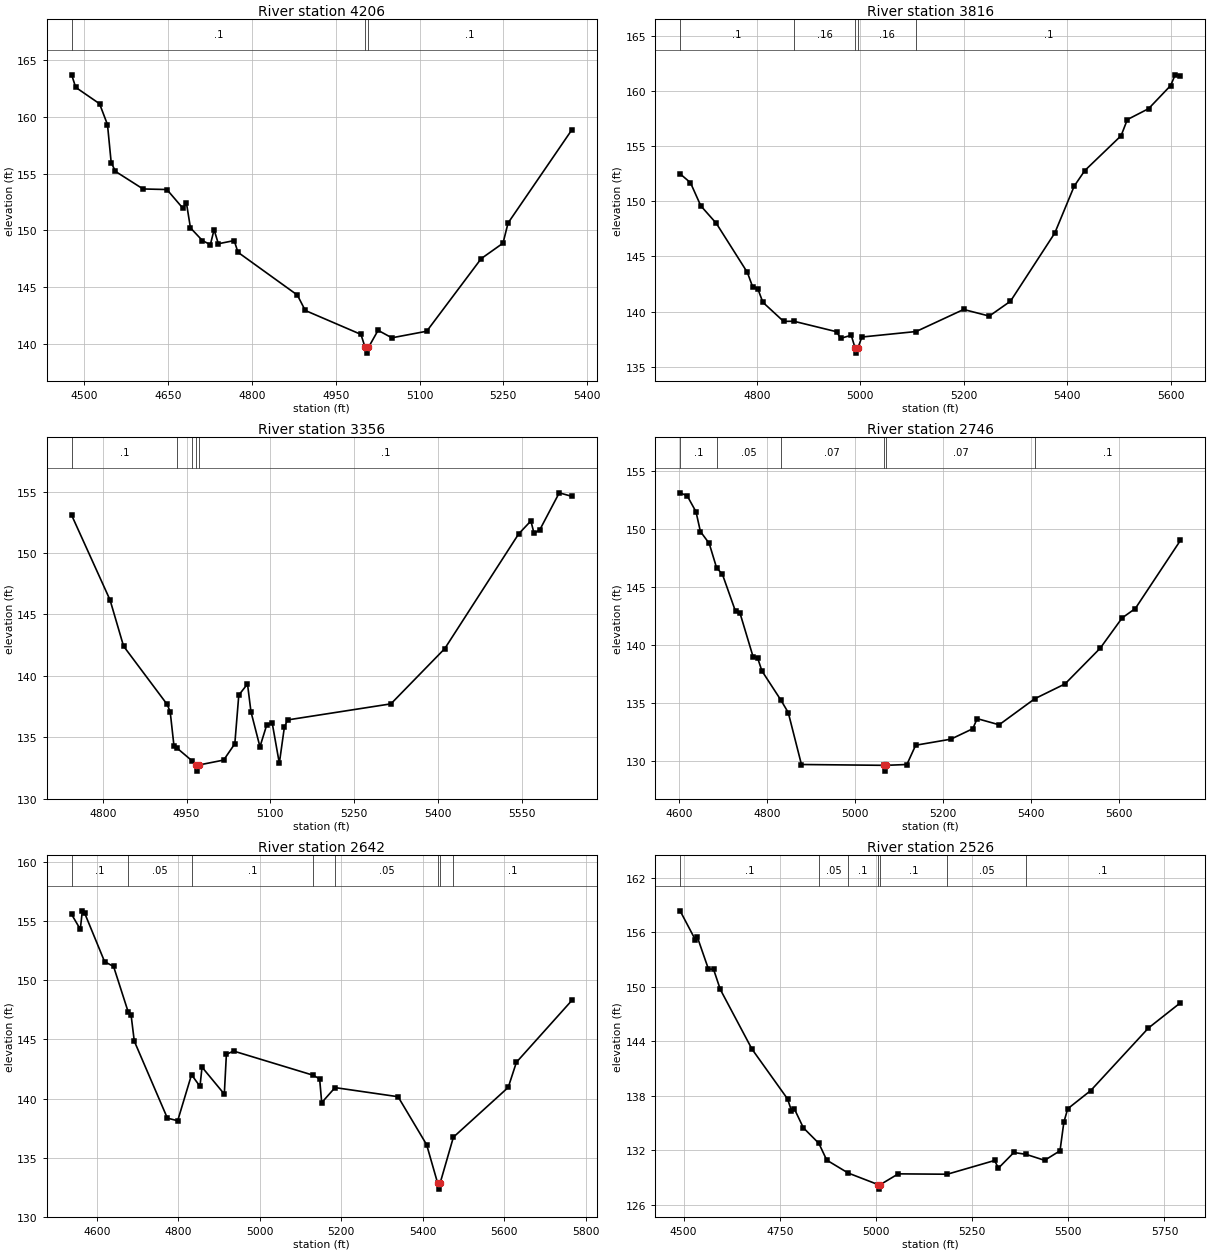
Type RM Length L Ch R = 1,4206,390,390,390
BEGIN DESCRIPTION:
UNT039 IN SPCR 7.0
END DESCRIPTION:
XS GIS Cut Line= 3
      2260137.74     13338696.84      2259787.72     13339096.85
      2259687.73     13339446.82
#Sta/Elev= 30
  4477.4  163.70  4484.5  162.60  4527.3  161.15  4541.5  159.31  4548.1  155.97
  4555.7  155.19  4605.1  153.64  4647.8  153.59  4676.3  151.95  4682.9  152.37
  4690.0  150.21  4711.4  149.09  4725.6  148.73  4732.3  150.05  4739.9  148.81
  4768.3  149.09  4775.0  148.06  4881.3  144.29  4895.5  142.93  4995.2  140.82
  5002.6  139.67  5005.4  139.17  5008.6  139.67  5025.8  141.18  5050.5  140.52
  5112.9  141.10  5210.4  147.50  5249.4  148.86  5258.5  150.64  5372.9  158.87
#Mann=3,-1,0
  4477.4     0.1       0  5002.6    0.07       0  5008.6     0.1       0
Bank Sta=5002.6,5008.6
Exp/Cntr=0.3,0.1

Type RM Length L Ch R = 1,3816,460,460,460
BEGIN DESCRIPTION:
UNT039 IN SPCR 6.0
END DESCRIPTION:
XS GIS Cut Line= 3
      2259487.72     13338546.89      2259487.72     13338846.85
      2259637.71     13339496.81
#Sta/Elev= 30
  4651.5  152.49  4671.5  151.69  4691.5  149.59  4721.5  148.00  4781.5  143.55
  4791.5  142.27  4801.5  142.09  4811.5  140.84  4851.5  139.11  4871.5  139.12
  4954.0  138.17  4961.7  137.57  4982.3  137.85  4989.5  136.73  4992.3  136.23
  4995.5  136.73  5002.8  137.69  5107.8  138.19  5199.5  140.19  5249.1  139.59
  5290.1  140.94  5375.7  147.12  5413.3  151.38  5433.8  152.79  5503.9  155.95
  5515.9  157.41  5557.0  158.40  5599.7  160.50  5608.3  161.47  5618.5  161.38
#Mann=5,-1,0
  4651.5     0.1       0  4871.5    0.16       0  4989.5    0.07       0
  4995.5    0.16       0  5107.8     0.1       0
Bank Sta=4989.5,4995.5
Exp/Cntr=0.3,0.1

Type RM Length L Ch R = 1,3356,610,610,610
BEGIN DESCRIPTION:
UNT039 IN SPCR 5.0
END DESCRIPTION:
XS GIS Cut Line= 3
      2259037.72     13338596.84      2259137.72     13338846.85
      2259437.74     13339396.88
#Sta/Elev= 30
  4744.3  153.08  4813.0  146.18  4837.2  142.42  4915.3  137.67  4920.7  137.07
  4927.4  134.31  4932.8  134.12  4960.6  133.05  4966.1  132.74  4968.9  132.24
  4972.1  132.74  5016.4  133.14  5036.4  134.47  5043.5  138.43  5059.1  139.34
  5065.3  137.08  5081.4  134.22  5093.3  135.97  5103.3  136.17  5116.1  132.88
  5125.1  135.81  5130.8  136.41  5315.9  137.72  5412.3  142.22  5544.7  151.57
  5566.5  152.62  5572.2  151.60  5582.6  151.91  5617.3  154.91  5640.1  154.62
#Mann=5,-1,0
  4744.3     0.1       0  4932.8    0.05       0  4960.6     0.1       0
  4966.1    0.07       0  4972.1     0.1       0
Bank Sta=4966.1,4972.1
Exp/Cntr=0.3,0.1

Type RM Length L Ch R = 1,2746,104,104,104
BEGIN DESCRIPTION:
Mapping XS 6f691e86
END DESCRIPTION:
XS GIS Cut Line= 2
      2258841.40     13338770.69      2258841.40     13339909.49
#Sta/Elev= 30
  4601.8  153.12  4618.0  152.86  4638.0  151.49  4648.0  149.79  4668.0  148.77
  4684.9  146.66  4698.0  146.12  4728.0  142.91  4738.0  142.78  4768.0  139.00
  4778.0  138.93  4788.0  137.79  4831.3  135.27  4848.0  134.20  4878.0  129.73
  5065.0  129.66  5067.7  129.16  5071.0  129.66  5118.0  129.73  5138.0  131.39
  5218.0  131.91  5268.0  132.81  5278.0  133.68  5328.0  133.15  5409.0  135.39
  5478.0  136.67  5558.0  139.74  5608.0  142.35  5638.0  143.16  5740.6  149.02
#Mann=6,-1,0
  4601.8     0.1       0  4684.9    0.05       0  4831.3    0.07       0
  5065.0    0.07       0  5071.0    0.07       0  5409.0     0.1       0
Bank Sta=5065,5071
Exp/Cntr=0.3,0.1

Type RM Length L Ch R = 1,2642,116,116,116
BEGIN DESCRIPTION:
Mapping XS c2d6c4ea
END DESCRIPTION:
XS GIS Cut Line= 3
      2258817.09     13338725.51      2258709.45     13339347.03
      2258678.27     13339943.05
#Sta/Elev= 30
  4538.4  155.56  4559.5  154.31  4564.6  155.87  4570.2  155.68  4619.2  151.57
  4641.2  151.17  4677.0  147.33  4684.1  147.08  4692.0  144.86  4773.2  138.35
  4798.5  138.13  4832.5  142.02  4853.2  141.03  4858.2  142.66  4912.9  140.38
  4918.0  143.74  4935.6  144.02  5131.5  141.97  5146.8  141.66  5151.9  139.66
  5184.6  140.93  5339.2  140.16  5409.3  136.11  5436.4  132.85  5439.1  132.35
  5442.4  132.85  5475.0  136.74  5609.6  140.95  5629.6  143.07  5766.0  148.31
#Mann=8,-1,0
  4538.4     0.1       0  4677.0    0.05       0  4832.5     0.1       0
  5131.5    0.07       0  5184.6    0.05       0  5436.4    0.07       0
  5442.4    0.05       0  5475.0     0.1       0
Bank Sta=5436.4,5442.4
Exp/Cntr=0.3,0.1

Type RM Length L Ch R = 1,2526,279,279,279
BEGIN DESCRIPTION:
UNT039 IN SPCR 3.0
END DESCRIPTION:
XS GIS Cut Line= 3
      2258742.43     13338675.21      2258607.02     13339241.13
      2258596.61     13339959.86
#Sta/Elev= 30
  4490.7  158.36  4530.4  155.17  4535.5  155.48  4564.4  151.95  4577.6  151.94
  4595.2  149.71  4677.5  143.15  4770.0  137.67  4780.3  136.37  4787.9  136.56
  4811.1  134.49  4851.4  132.78  4872.0  130.93  4927.7  129.51  5005.4  128.24
  5008.1  127.74  5011.4  128.24  5057.9  129.42  5185.3  129.38  5308.3  130.89
  5318.3  130.05  5358.4  131.77  5389.8  131.57  5438.4  130.91  5478.4  131.96
  5488.4  135.10  5498.4  136.58  5558.4  138.59  5708.4  145.47  5791.4  148.24
#Mann=7,-1,0
  4490.7     0.1       0  4851.4    0.05       0  4927.7     0.1       0
  5005.4    0.07       0  5011.4     0.1       0  5185.3    0.05       0
  5389.8     0.1       0
Bank Sta=5005.4,5011.4
Exp/Cntr=0.3,0.1

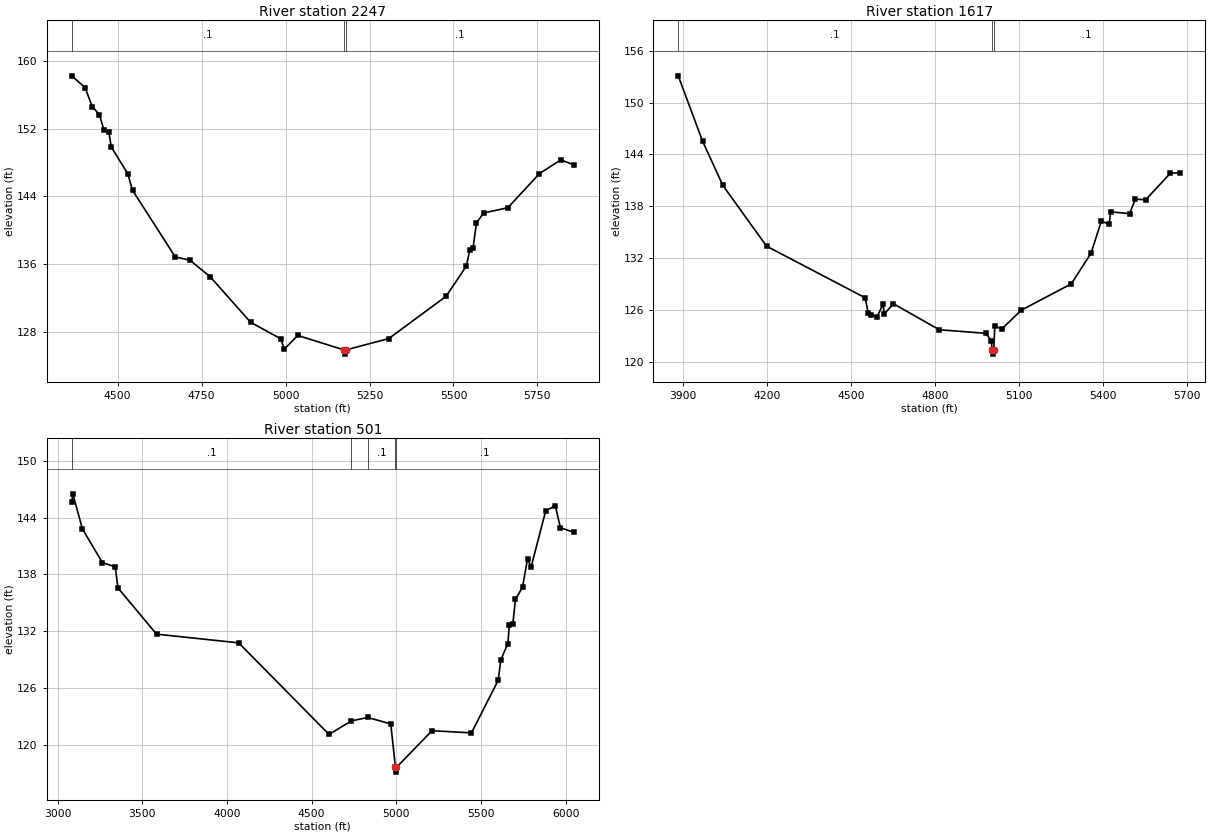
Type RM Length L Ch R = 1,2247,630,630,630
BEGIN DESCRIPTION:
UNT039 IN SPCR 2.0
END DESCRIPTION:
XS GIS Cut Line= 4
      2258629.01     13338602.17      2258380.69     13338836.70
      2258297.91     13339767.95      2258414.44     13339953.03
#Sta/Elev= 30
  4363.3  158.24  4403.0  156.85  4424.0  154.61  4445.5  153.66  4459.6  151.78
  4473.8  151.61  4480.7  149.84  4530.1  146.66  4544.2  144.71  4671.6  136.82
  4715.1  136.44  4775.3  134.49  4895.8  129.10  4986.1  127.13  4996.2  125.91
  5036.3  127.54  5173.9  125.83  5176.6  125.33  5179.9  125.83  5307.4  127.17
  5478.1  132.17  5538.3  135.73  5548.3  137.60  5558.4  137.90  5568.4  140.83
  5589.5  142.02  5661.9  142.64  5756.1  146.68  5819.7  148.30  5858.5  147.72
#Mann=3,-1,0
  4363.3     0.1       0  5173.9    0.07       0  5179.9     0.1       0
Bank Sta=5173.9,5179.9
Exp/Cntr=0.3,0.1

Type RM Length L Ch R = 1,1617,1116,1116,1116
BEGIN DESCRIPTION:
Mapping XS 56e76175
END DESCRIPTION:
XS GIS Cut Line= 4
      2258491.04     13338540.08      2258063.37     13338664.24
      2257725.36     13339698.97      2257663.57     13339952.99
#Sta/Elev= 30
  3882.2  153.10  3969.0  145.55  4041.8  140.40  4198.0  133.37  4550.5  127.39
  4561.7  125.60  4572.2  125.39  4593.3  125.18  4614.3  126.65  4619.5  125.52
  4651.4  126.70  4816.1  123.68  4982.5  123.27  5002.1  122.37  5004.4  121.36
  5007.1  120.86  5010.4  121.36  5014.1  124.11  5039.2  123.77  5108.8  125.95
  5287.6  129.00  5358.1  132.54  5395.2  136.27  5423.1  135.90  5428.3  137.34
  5496.2  137.14  5516.9  138.82  5553.5  138.74  5642.1  141.82  5677.5  141.86
#Mann=3,-1,0
  3882.2     0.1       0  5004.4    0.07       0  5010.4     0.1       0
Bank Sta=5004.4,5010.4
Exp/Cntr=0.3,0.1

Type RM Length L Ch R = 1,501,0,0,0
BEGIN DESCRIPTION:
UNT039 IN SPCR 1.0
END DESCRIPTION:
XS GIS Cut Line= 4
      2258539.38     13338139.97      2256973.45     13338698.73
      2257063.13     13339229.89      2257497.72     13339857.63
#Sta/Elev= 30
  3083.4  145.65  3089.7  146.51  3146.0  142.81  3264.0  139.24  3340.0  138.79
  3356.4  136.55  3584.2  131.67  4069.1  130.75  4602.4  121.07  4734.9  122.50
  4831.1  122.86  4967.2  122.18  4994.7  117.58  4997.4  117.08  5000.7  117.58
  5210.6  121.46  5443.7  121.23  5601.8  126.80  5616.6  128.93  5658.5  130.68
  5667.3  132.61  5688.3  132.79  5703.1  135.34  5745.0  136.63  5774.7  139.64
  5795.7  138.76  5882.2  144.73  5938.9  145.25  5968.7  142.93  6048.2  142.44
#Mann=5,-1,0
  3083.4     0.1       0  4734.9    0.16       0  4831.1     0.1       0
  4994.7    0.07       0  5000.7     0.1       0
Bank Sta=4994.7,5000.7
Exp/Cntr=0.3,0.1

Chan Stop Cuts=-1