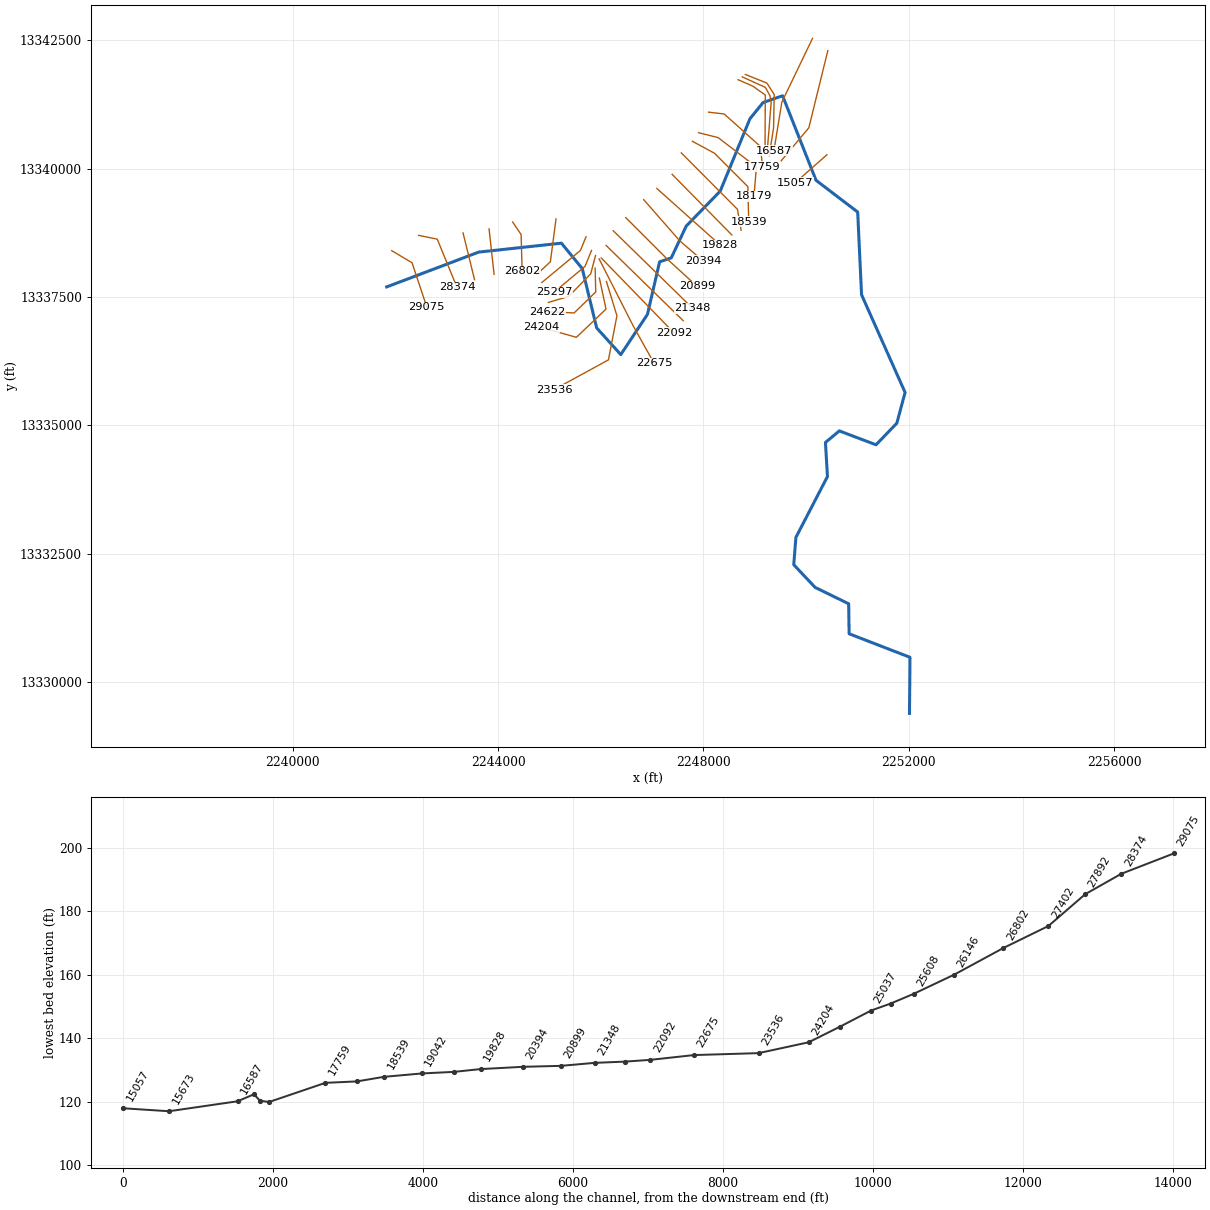
--- UNT040 IN SPCR.prj (project) ---

Proj Title=UNT040 IN SPCR Base Level Engineering
Current Plan=p01
Default Exp/Contr=0.3,0.1
English Units
Geom File=g01
Flow File=f01
Plan File=p01
BEGIN DESCRIPTION:
UNT040 IN SPCR
END DESCRIPTION:

--- UNT040 IN SPCR.p01 (plan) ---

Plan Title=Multiple Run
Short Identifier=Multiple
Geom File=g01
Flow File=f01
Subcritical Flow
K Sum by GR= 0
Std Step Tol= 0.01
Critical Tol= 0.01
Num of Std Step Trials= 20
Max Error Tol= 0.3
Flow Tol Ratio= 0.001
Split Flow NTrial= 30
Split Flow Tol= 0.02
Split Flow Ratio= 0.02
Log Output Level= 0
Friction Slope Method= 1
Unsteady Friction Slope Method= 2
Unsteady Bridges Friction Slope Method= 1
Parabolic Critical Depth
Global Vel Dist=  1 , 1 , 1
Global Log Level= 0
CheckData=True
Encroach Param= -1, 0, 0, 0
BEGIN DESCRIPTION:
Multiple Run
END DESCRIPTION:

--- UNT040 IN SPCR.f01 (steady flow) ---

Flow Title=Multiple
Number of Profiles=7
Profile Names=10-year,25-year,50-year,1pct_min,100-year,1pct_plu,500-year
River Rch & RM= UNT040 IN SPCR,Reach-1,29075
     207     286     352     318     431     582     655
River Rch & RM= UNT040 IN SPCR,Reach-1,20899
     235     326     401     363     491     664     748
River Rch & RM= UNT040 IN SPCR,Reach-1,16587
     380     539     675     620     839    1134    1317
River Rch & RM= UNT040 IN SPCR,Reach-1,14200
     448     637     798     733     991    1341    1556
Boundary for River Rch & Prof#=UNT040 IN SPCR,Reach-1,1
Up Type=0
Dn Type=3
Dn Slope=0.005
Boundary for River Rch & Prof#=UNT040 IN SPCR,Reach-1,2
Up Type=0
Dn Type=3
Dn Slope=0.005
Boundary for River Rch & Prof#=UNT040 IN SPCR,Reach-1,3
Up Type=0
Dn Type=3
Dn Slope=0.005
Boundary for River Rch & Prof#=UNT040 IN SPCR,Reach-1,4
Up Type=0
Dn Type=3
Dn Slope=0.005
Boundary for River Rch & Prof#=UNT040 IN SPCR,Reach-1,5
Up Type=0
Dn Type=3
Dn Slope=0.005
Boundary for River Rch & Prof#=UNT040 IN SPCR,Reach-1,6
Up Type=0
Dn Type=3
Dn Slope=0.005
Boundary for River Rch & Prof#=UNT040 IN SPCR,Reach-1,7
Up Type=0
Dn Type=3
Dn Slope=0.005

--- UNT040 IN SPCR.g01 (geometry) ---

Geom Title=Existing Conditions

River Reach=UNT040 IN SPCR,Reach-1
Reach XY= 30
      2241832.72     13337696.85      2243623.53     13338374.91
      2245235.18     13338549.24      2245640.59     13338054.15
      2245921.18     13336897.88      2246391.04     13336377.50
      2246911.40     13337164.17      2247147.03     13338186.33
      2247374.39     13338263.03      2247665.45     13338882.53
      2248327.36     13339563.08      2248905.97     13340972.98
      2249161.49     13341288.79      2249541.79     13341422.03
      2250193.36     13339774.27      2251004.23     13339155.49
      2251079.72     13337543.62      2251927.40     13335640.26
      2251766.34     13335040.99      2251361.28     13334620.30
      2250646.74     13334891.00      2250376.81     13334665.76
      2250415.51     13334001.26      2249800.91     13332815.53
      2249759.57     13332283.28      2250175.11     13331841.64
      2250828.80     13331522.45      2250837.62     13330937.82
      2252022.99     13330479.52      2252012.96     13329386.74

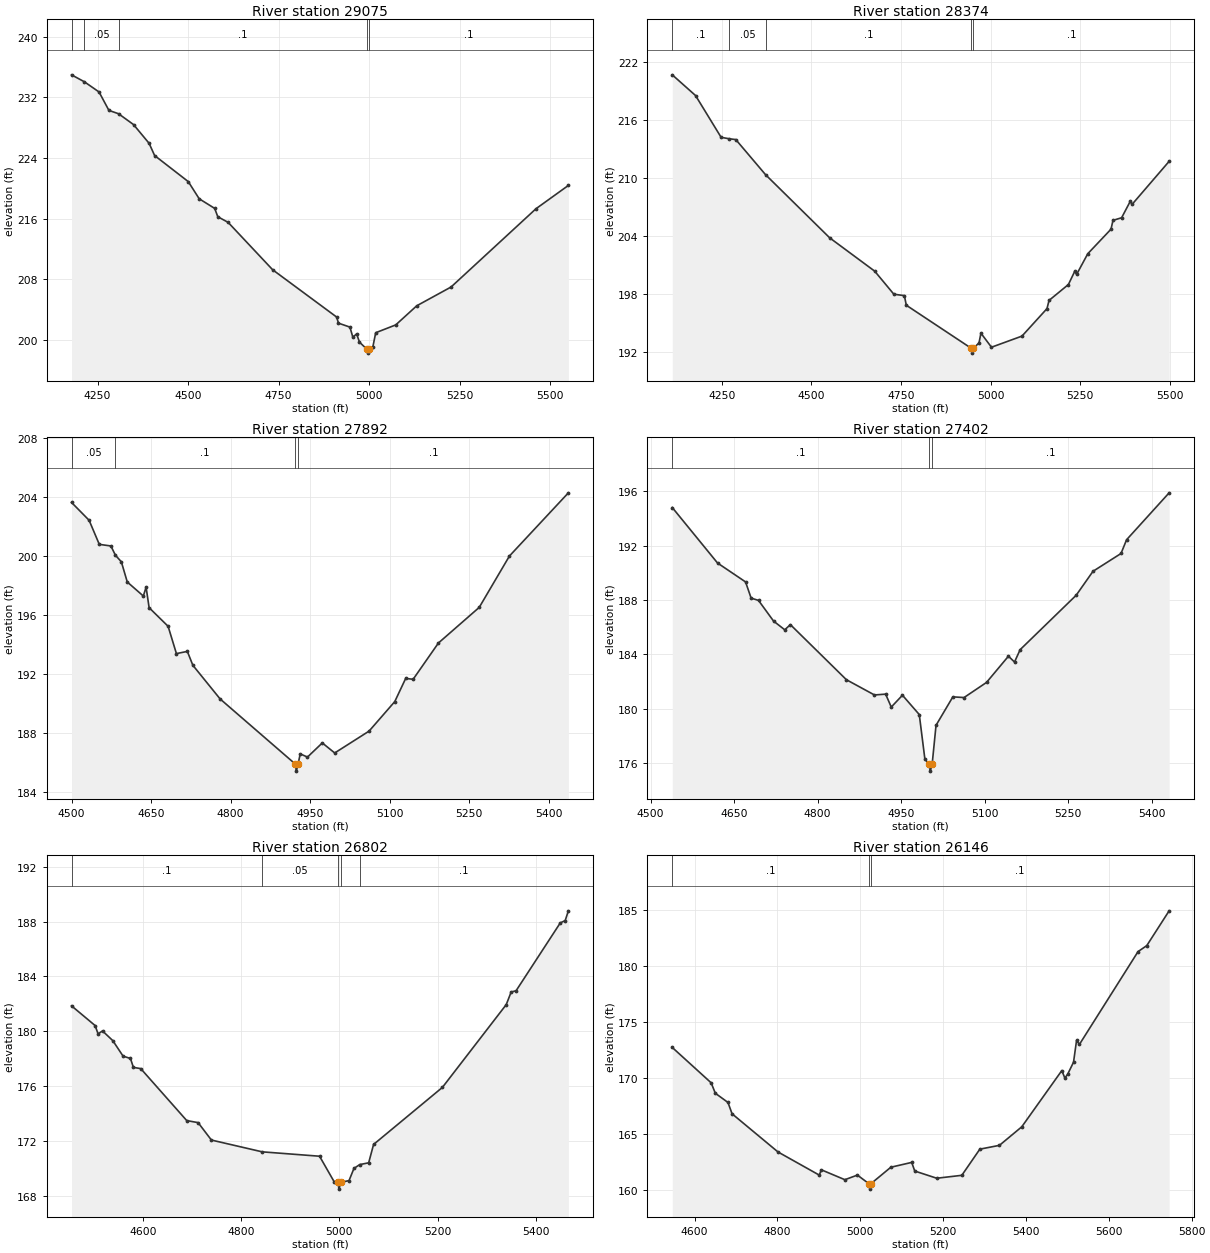
Type RM Length L Ch R = 1,29075,701,701,701
BEGIN DESCRIPTION:
UNT040 IN SPCR 44.0
END DESCRIPTION:
XS GIS Cut Line= 3
      2241930.48     13338402.56      2242325.85     13338167.48
      2242614.32     13337302.07
#Sta/Elev= 30
  4178.0  234.98  4213.6  234.06  4254.0  232.72  4281.3  230.29  4307.9  229.85
  4349.3  228.42  4392.3  225.95  4407.5  224.34  4500.5  220.90  4530.6  218.64
  4573.4  217.37  4582.0  216.27  4610.5  215.53  4733.5  209.28  4910.1  203.05
  4915.3  202.24  4946.9  201.72  4954.9  200.40  4965.4  200.82  4973.3  199.74
  4994.0  198.79  4996.8  198.29  5000.0  198.79  5010.2  199.11  5018.1  200.98
  5073.4  202.01  5131.4  204.53  5226.3  207.01  5460.8  217.33  5550.2  220.40
#Mann=5,-1,0
  4178.0     0.1       0  4213.6    0.05       0  4307.9     0.1       0
  4994.0    0.07       0  5000.0     0.1       0
Bank Sta=4994,5000
Exp/Cntr=0.3,0.1

Type RM Length L Ch R = 1,28374,482,482,482
BEGIN DESCRIPTION:
Mapping XS bbc486c1
END DESCRIPTION:
XS GIS Cut Line= 3
      2242454.10     13338701.69      2242817.34     13338626.91
      2243201.97     13337686.70
#Sta/Elev= 30
  4111.6  220.63  4176.6  218.49  4248.0  214.17  4271.1  214.02  4288.9  213.94
  4372.0  210.31  4551.1  203.78  4676.6  200.34  4730.0  197.96  4759.4  197.81
  4764.8  196.82  4946.1  192.37  4948.8  191.87  4952.1  192.37  4967.7  192.93
  4973.1  193.93  5002.5  192.48  5087.6  193.63  5157.4  196.47  5163.2  197.32
  5217.2  198.96  5234.8  200.32  5240.2  200.01  5271.2  202.14  5336.1  204.68
  5341.6  205.59  5365.7  205.86  5389.7  207.55  5395.1  207.25  5498.3  211.69
#Mann=5,-1,0
  4111.6     0.1       0  4271.1    0.05       0  4372.0     0.1       0
  4946.1    0.07       0  4952.1     0.1       0
Bank Sta=4946.1,4952.1
Exp/Cntr=0.3,0.1

Type RM Length L Ch R = 1,27892,490,490,490
BEGIN DESCRIPTION:
Mapping XS ddddede7
END DESCRIPTION:
XS GIS Cut Line= 2
      2243319.30     13338749.05      2243542.93     13337838.82
#Sta/Elev= 30
  4500.0  203.63  4533.2  202.42  4552.4  200.79  4574.3  200.68  4582.9  200.05
  4594.0  199.61  4605.2  198.24  4635.5  197.29  4640.7  197.89  4646.4  196.50
  4682.2  195.24  4697.9  193.39  4718.5  193.54  4728.9  192.60  4780.3  190.32
  4921.5  185.93  4924.2  185.43  4927.5  185.93  4931.5  186.60  4945.1  186.38
  4973.1  187.34  4996.5  186.66  5061.3  188.14  5109.8  190.14  5130.4  191.71
  5144.4  191.65  5192.2  194.11  5269.1  196.52  5326.1  200.00  5437.3  204.28
#Mann=4,-1,0
  4500.0    0.05       0  4582.9     0.1       0  4921.5    0.07       0
  4927.5     0.1       0
Bank Sta=4921.5,4927.5
Exp/Cntr=0.3,0.1

Type RM Length L Ch R = 1,27402,600,600,600
BEGIN DESCRIPTION:
Mapping XS 7e1aadb8
END DESCRIPTION:
XS GIS Cut Line= 2
      2243825.89     13338827.63      2243923.98     13337940.94
#Sta/Elev= 30
  4539.0  194.80  4620.3  190.72  4670.6  189.33  4680.6  188.14  4693.9  187.97
  4720.9  186.45  4741.0  185.81  4751.1  186.19  4851.7  182.14  4902.0  181.02
  4922.1  181.08  4932.2  180.13  4952.3  181.00  4982.5  179.58  4992.5  176.33
  4999.6  175.92  5002.3  175.42  5005.6  175.92  5012.6  178.79  5042.8  180.88
  5062.9  180.83  5103.2  181.94  5142.6  183.87  5153.5  183.44  5163.6  184.35
  5264.2  188.35  5294.4  190.11  5344.7  191.42  5354.7  192.43  5431.1  195.88
#Mann=3,-1,0
  4539.0     0.1       0  4999.6    0.07       0  5005.6     0.1       0
Bank Sta=4999.6,5005.6
Exp/Cntr=0.3,0.1

Type RM Length L Ch R = 1,26802,656,656,656
BEGIN DESCRIPTION:
Mapping XS 24b813eb
END DESCRIPTION:
XS GIS Cut Line= 3
      2244285.36     13338961.13      2244450.31     13338717.63
      2244469.90     13338000.40
#Sta/Elev= 30
  4454.8  181.86  4502.9  180.42  4508.9  179.81  4517.9  180.03  4538.9  179.32
  4559.8  178.19  4574.8  178.02  4580.8  177.37  4595.8  177.28  4689.4  173.49
  4712.6  173.34  4739.6  172.07  4843.0  171.21  4959.8  170.89  4989.8  169.01
  4996.8  168.99  4999.5  168.49  5002.8  168.99  5019.8  169.11  5029.8  170.00
  5041.6  170.28  5059.8  170.41  5069.8  171.75  5209.9  175.91  5339.9  181.95
  5349.9  182.87  5359.9  182.96  5449.9  187.91  5459.9  188.08  5466.4  188.79
#Mann=5,-1,0
  4454.8     0.1       0  4843.0    0.05       0  4996.8   0.035       0
  5002.8    0.05       0  5041.6     0.1       0
Bank Sta=4996.8,5002.8
Exp/Cntr=0.3,0.1

Type RM Length L Ch R = 1,26146,538,538,538
BEGIN DESCRIPTION:
Mapping XS 6c5349a7
END DESCRIPTION:
XS GIS Cut Line= 3
      2245129.69     13339019.97      2245019.74     13338187.47
      2244757.57     13337940.95
#Sta/Elev= 30
  4546.0  172.72  4639.9  169.57  4650.0  168.64  4680.5  167.82  4690.4  166.81
  4801.3  163.41  4900.9  161.35  4906.0  161.82  4962.7  160.94  4993.0  161.35
  5020.2  160.60  5023.0  160.10  5026.2  160.60  5073.7  162.05  5124.1  162.48
  5131.5  161.71  5184.6  161.07  5245.1  161.33  5288.6  163.66  5335.9  164.00
  5389.8  165.65  5486.5  170.66  5493.8  170.00  5500.6  170.33  5514.8  171.41
  5522.1  173.34  5529.0  172.99  5670.6  181.26  5691.6  181.79  5745.6  184.89
#Mann=3,-1,0
  4546.0     0.1       0  5020.2    0.07       0  5026.2     0.1       0
Bank Sta=5020.2,5026.2
Exp/Cntr=0.3,0.1

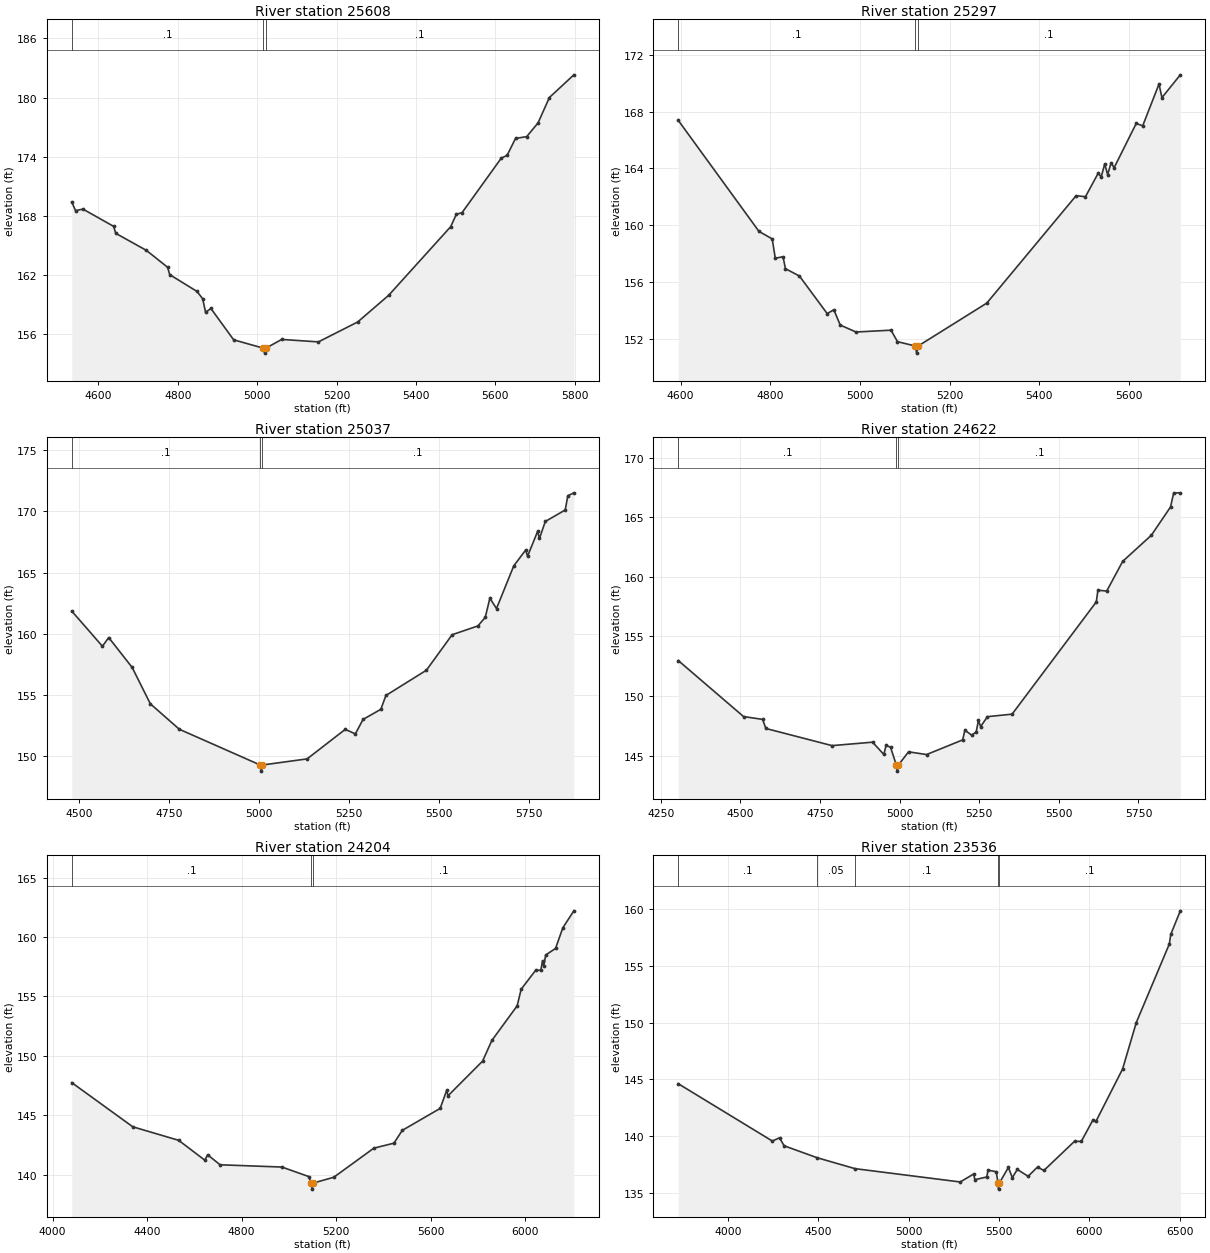
Type RM Length L Ch R = 1,25608,311,311,311
BEGIN DESCRIPTION:
Mapping XS 83d63ea5
END DESCRIPTION:
XS GIS Cut Line= 3
      2245714.86     13338674.47      2245604.88     13338407.39
      2244854.80     13337782.98
#Sta/Elev= 30
  4532.9  169.40  4542.5  168.52  4561.1  168.68  4638.3  166.93  4643.7  166.22
  4721.0  164.49  4774.3  162.78  4779.7  162.03  4848.3  160.33  4862.6  159.59
  4870.1  158.21  4883.4  158.60  4940.7  155.42  5015.8  154.57  5018.6  154.07
  5021.8  154.57  5061.8  155.46  5154.2  155.21  5253.2  157.23  5331.3  159.94
  5487.5  166.90  5501.8  168.16  5516.1  168.32  5615.1  173.86  5629.4  174.12
  5650.8  175.85  5678.9  176.03  5707.5  177.42  5736.1  180.00  5797.7  182.30
#Mann=3,-1,0
  4532.9     0.1       0  5015.8    0.07       0  5021.8     0.1       0
Bank Sta=5015.8,5021.8
Exp/Cntr=0.3,0.1

Type RM Length L Ch R = 1,25297,260,260,260
BEGIN DESCRIPTION:
Mapping XS 19612e8c
END DESCRIPTION:
XS GIS Cut Line= 3
      2245820.88     13338407.40      2245695.21     13338097.15
      2245091.54     13337595.40
#Sta/Elev= 30
  4594.7  167.40  4774.8  159.56  4804.3  159.03  4811.1  157.67  4828.4  157.77
  4833.8  156.93  4865.0  156.41  4926.9  153.76  4941.7  154.03  4956.0  152.95
  4991.2  152.46  5069.3  152.59  5083.6  151.78  5123.6  151.47  5126.3  150.97
  5129.6  151.47  5282.8  154.50  5482.0  162.08  5502.9  162.01  5531.5  163.68
  5538.0  163.40  5545.8  164.32  5552.3  163.57  5560.2  164.41  5566.7  164.05
  5616.1  167.18  5630.5  167.01  5666.9  169.96  5673.4  169.00  5714.4  170.61
#Mann=3,-1,0
  4594.7     0.1       0  5123.6    0.07       0  5129.6     0.1       0
Bank Sta=5123.6,5129.6
Exp/Cntr=0.3,0.1

Type RM Length L Ch R = 1,25037,415,415,415
BEGIN DESCRIPTION:
Mapping XS 4adb45aa
END DESCRIPTION:
XS GIS Cut Line= 4
      2245899.42     13338309.21      2245805.17     13337951.84
      2245377.11     13337512.01      2244981.63     13337394.54
#Sta/Elev= 30
  4478.6  161.85  4563.8  158.98  4581.3  159.69  4646.5  157.25  4697.0  154.28
  4777.6  152.20  5002.5  149.28  5005.3  148.78  5008.5  149.28  5132.9  149.78
  5238.9  152.19  5267.1  151.82  5288.3  153.00  5337.9  153.83  5352.0  154.96
  5464.5  157.02  5536.1  159.92  5607.8  160.64  5628.2  161.34  5641.0  162.90
  5659.5  162.06  5707.4  165.54  5740.6  166.84  5745.8  166.33  5773.8  168.36
  5779.0  167.79  5795.1  169.17  5850.6  170.11  5857.7  171.27  5874.5  171.51
#Mann=3,-1,0
  4478.6     0.1       0  5002.5    0.07       0  5008.5     0.1       0
Bank Sta=5002.5,5008.5
Exp/Cntr=0.3,0.1

Type RM Length L Ch R = 1,24622,418,418,418
BEGIN DESCRIPTION:
Mapping XS 430e8905
END DESCRIPTION:
XS GIS Cut Line= 4
      2245891.56     13338061.76      2245903.34     13337598.40
      2245483.14     13337189.98      2244956.96     13337213.54
#Sta/Elev= 30
  4305.1  152.97  4510.1  148.27  4570.1  148.03  4580.1  147.27  4787.9  145.83
  4915.2  146.12  4950.5  145.09  4957.6  145.85  4971.7  145.69  4989.9  144.19
  4992.7  143.69  4995.9  144.19  5028.2  145.31  5084.8  145.08  5197.9  146.31
  5205.1  147.12  5226.2  146.71  5240.4  146.97  5247.5  147.94  5254.5  147.43
  5275.8  148.26  5353.2  148.47  5617.6  157.89  5622.6  158.87  5650.3  158.80
  5700.4  161.29  5790.4  163.48  5850.5  165.85  5860.5  167.03  5881.3  167.04
#Mann=3,-1,0
  4305.1     0.1       0  4989.9    0.07       0  4995.9     0.1       0
Bank Sta=4989.9,4995.9
Exp/Cntr=0.3,0.1

Type RM Length L Ch R = 1,24204,668,668,668
BEGIN DESCRIPTION:
Mapping XS e1c4061b
END DESCRIPTION:
XS GIS Cut Line= 4
      2245974.03     13337869.40      2246103.63     13337264.60
      2245526.34     13336714.80      2244843.05     13336907.22
#Sta/Elev= 30
  4080.9  147.74  4339.2  144.02  4533.5  142.88  4644.1  141.21  4656.2  141.66
  4708.9  140.82  4970.6  140.63  5083.9  139.83  5095.0  139.27  5097.8  138.77
  5101.0  139.27  5190.2  139.77  5359.7  142.22  5444.7  142.64  5480.2  143.72
  5640.6  145.57  5668.4  147.10  5673.6  146.63  5820.1  149.55  5859.3  151.29
  5966.6  154.21  5983.5  155.61  6045.8  157.23  6066.6  157.19  6073.9  158.01
  6079.1  157.56  6087.4  158.49  6128.9  159.04  6160.1  160.79  6206.5  162.21
#Mann=3,-1,0
  4080.9     0.1       0  5095.0    0.07       0  5101.0     0.1       0
Bank Sta=5095,5101
Exp/Cntr=0.3,0.1

Type RM Length L Ch R = 1,23536,861,861,861
BEGIN DESCRIPTION:
Mapping XS 6c500910
END DESCRIPTION:
XS GIS Cut Line= 4
      2246111.48     13337802.62      2246315.69     13337135.00
      2246150.75     13336274.96      2245094.36     13335697.68
#Sta/Elev= 30
  3725.8  144.62  4246.2  139.58  4286.1  139.86  4311.7  139.16  4494.6  138.11
  4703.9  137.15  5285.8  135.98  5360.1  136.68  5367.2  136.18  5432.7  136.42
  5439.9  137.02  5485.4  136.88  5495.2  135.85  5497.9  135.35  5501.2  135.85
  5552.3  137.26  5574.1  136.36  5601.6  137.08  5661.4  136.48  5713.4  137.29
  5748.7  136.99  5918.5  139.56  5955.5  139.54  6021.0  141.46  6037.1  141.32
  6184.1  145.91  6260.0  150.00  6442.7  156.90  6450.7  157.75  6503.5  159.82
#Mann=5,-1,0
  3725.8     0.1       0  4494.6    0.05       0  4703.9     0.1       0
  5495.2    0.07       0  5501.2     0.1       0
Bank Sta=5495.2,5501.2
Exp/Cntr=0.3,0.1

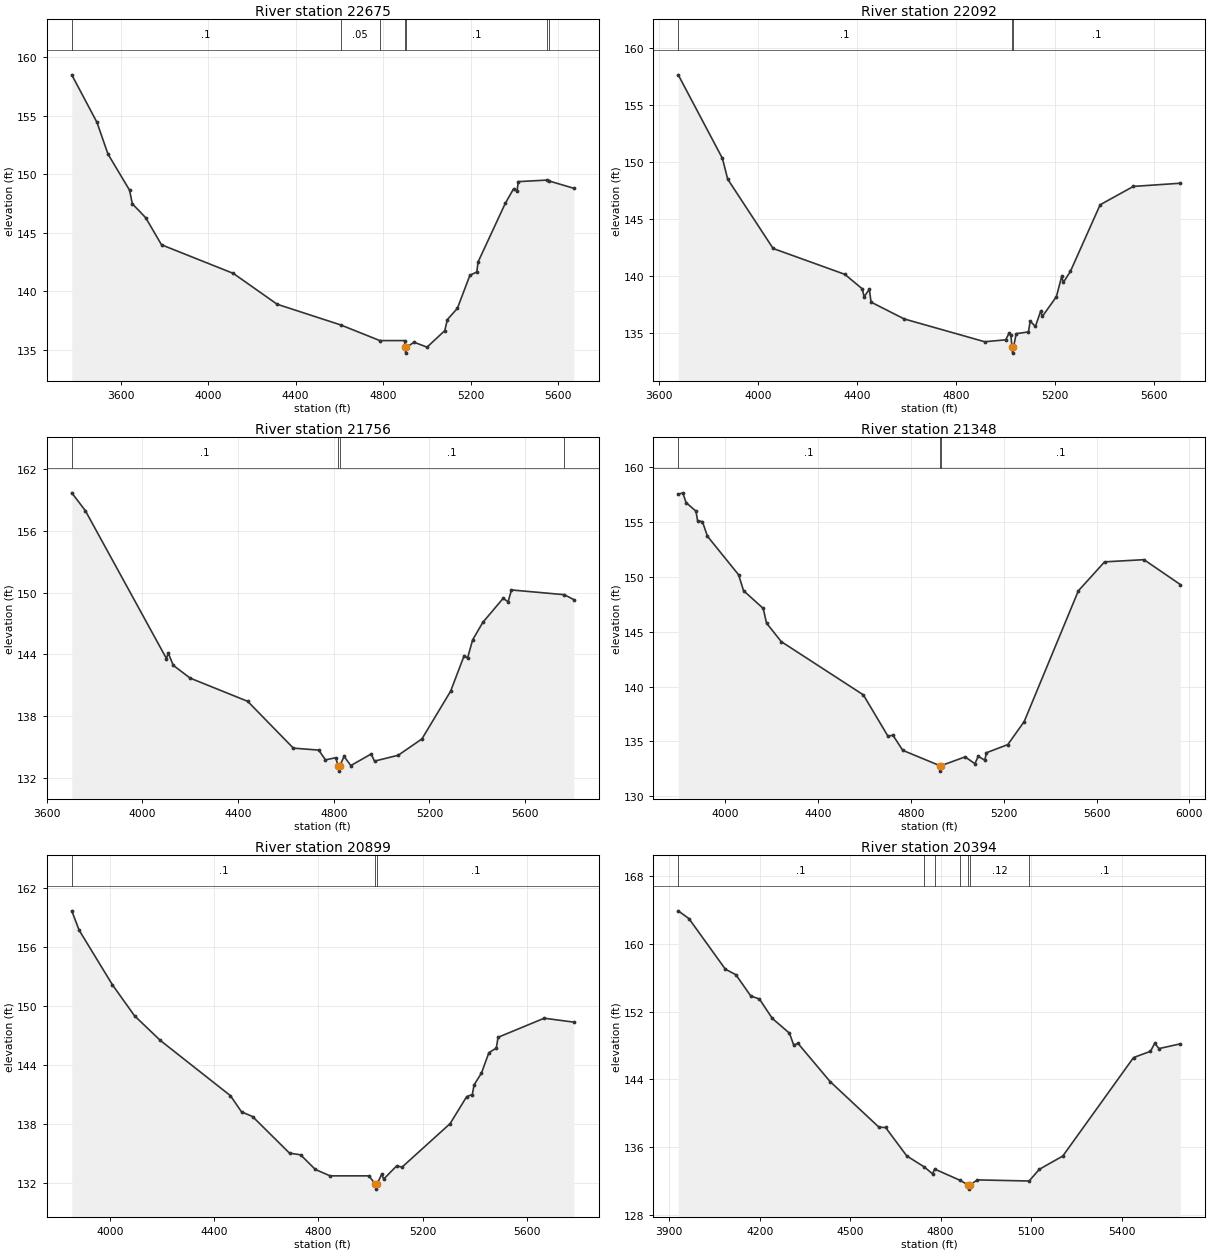
Type RM Length L Ch R = 1,22675,583,583,583
BEGIN DESCRIPTION:
Mapping XS 18f52b45
END DESCRIPTION:
XS GIS Cut Line= 3
      2245969.26     13338242.30      2246631.71     13336938.75
      2247037.72     13336212.21
#Sta/Elev= 30
  3377.0  158.48  3492.3  154.42  3542.5  151.72  3641.1  148.64  3653.7  147.48
  3714.9  146.29  3787.2  143.98  4115.4  141.54  4315.7  138.91  4605.4  137.15
  4784.9  135.81  4897.9  135.81  4900.6  135.24  4903.3  134.74  4906.6  135.24
  4941.3  135.67  5000.7  135.25  5081.7  136.66  5093.4  137.60  5139.2  138.56
  5196.5  141.38  5228.0  141.66  5233.7  142.51  5358.2  147.52  5395.9  148.75
  5411.8  148.56  5417.6  149.37  5547.6  149.50  5555.8  149.44  5671.5  148.80
#Mann=7,-1,0
  3377.0     0.1       0  4605.4    0.05       0  4784.9     0.1       0
  4900.6    0.07       0  4906.6     0.1       0  5547.6    0.05       0
  5555.8     0.1       0
Bank Sta=4900.6,4906.6
Exp/Cntr=0.3,0.1

Type RM Length L Ch R = 1,22092,336,336,336
BEGIN DESCRIPTION:
UNT040 IN SPCR 43.0
END DESCRIPTION:
XS GIS Cut Line= 2
      2246009.86     13338261.71      2247423.80     13336804.40
#Sta/Elev= 30
  3677.9  157.67  3856.6  150.33  3877.9  148.51  4061.6  142.42  4351.7  140.15
  4422.5  138.87  4429.4  138.18  4450.8  138.83  4457.7  137.71  4592.0  136.23
  4917.4  134.23  5002.3  134.40  5016.4  135.01  5023.4  134.79  5027.6  133.73
  5030.3  133.23  5033.6  133.73  5044.7  134.94  5094.1  135.09  5101.3  136.04
  5122.4  135.57  5143.7  136.92  5150.7  136.46  5207.3  138.19  5228.6  139.96
  5235.6  139.45  5263.9  140.41  5384.2  146.26  5518.5  147.87  5708.4  148.15
#Mann=3,-1,0
  3677.9     0.1       0  5027.6    0.07       0  5033.6     0.1       0
Bank Sta=5027.6,5033.6
Exp/Cntr=0.3,0.1

Type RM Length L Ch R = 1,21756,408,408,408
BEGIN DESCRIPTION:
UNT040 IN SPCR 42.0
END DESCRIPTION:
XS GIS Cut Line= 2
      2246105.37     13338504.74      2247607.13     13337037.70
#Sta/Elev= 30
  3704.6  159.67  3761.4  157.94  4100.7  143.59  4107.9  144.14  4129.0  142.94
  4199.7  141.70  4440.2  139.45  4631.1  134.91  4737.2  134.72  4765.5  133.77
  4808.0  133.98  4819.1  133.18  4821.9  132.68  4825.1  133.18  4843.2  134.11
  4871.5  133.22  4956.4  134.34  4970.5  133.65  5069.6  134.22  5168.6  135.80
  5288.7  140.43  5345.3  143.88  5359.5  143.64  5380.8  145.41  5423.2  147.10
  5508.1  149.43  5529.2  149.12  5543.3  150.25  5764.5  149.79  5804.0  149.31
#Mann=4,-1,0
  3704.6     0.1       0  4819.1    0.07       0  4825.1     0.1       0
  5764.5    0.05       0
Bank Sta=4819.1,4825.1
Exp/Cntr=0.3,0.1

Type RM Length L Ch R = 1,21348,449,449,449
BEGIN DESCRIPTION:
UNT040 IN SPCR 41.0
END DESCRIPTION:
XS GIS Cut Line= 2
      2246244.26     13338791.20      2247791.01     13337278.91
#Sta/Elev= 30
  3797.5  157.54  3817.1  157.68  3831.2  156.79  3873.7  156.01  3880.8  155.15
  3902.0  155.04  3923.3  153.72  4057.6  150.20  4078.9  148.75  4163.7  147.13
  4177.9  145.79  4241.4  144.10  4595.1  139.24  4701.1  135.47  4722.4  135.56
  4764.8  134.18  4924.4  132.78  4927.1  132.28  4930.4  132.78  5033.4  133.58
  5075.8  132.96  5090.0  133.63  5118.3  133.28  5125.4  133.96  5217.3  134.70
  5288.0  136.80  5521.5  148.74  5634.5  151.38  5804.2  151.58  5960.7  149.31
#Mann=3,-1,0
  3797.5     0.1       0  4924.4    0.07       0  4930.4     0.1       0
Bank Sta=4924.4,4930.4
Exp/Cntr=0.3,0.1

Type RM Length L Ch R = 1,20899,505,505,505
BEGIN DESCRIPTION:
UNT040 IN SPCR 40.0
END DESCRIPTION:
XS GIS Cut Line= 3
      2246487.73     13339046.84      2247287.72     13338246.85
      2247872.20     13337711.43
#Sta/Elev= 30
  3854.6  159.64  3882.9  157.67  4010.1  152.13  4095.0  148.97  4194.0  146.46
  4462.7  140.84  4505.1  139.20  4547.5  138.72  4689.0  135.00  4731.4  134.83
  4788.0  133.34  4844.5  132.69  4993.0  132.69  5018.4  131.84  5021.2  131.34
  5024.4  131.84  5042.4  132.87  5049.8  132.36  5099.1  133.69  5120.7  133.59
  5304.4  138.00  5368.0  140.75  5389.5  140.96  5396.3  141.94  5424.7  143.15
  5453.1  145.22  5481.4  145.68  5488.2  146.78  5665.2  148.72  5778.6  148.32
#Mann=3,-1,0
  3854.6     0.1       0  5018.4    0.07       0  5024.4     0.1       0
Bank Sta=5018.4,5024.4
Exp/Cntr=0.3,0.1

Type RM Length L Ch R = 1,20394,566,566,566
BEGIN DESCRIPTION:
UNT040 IN SPCR 39.0
END DESCRIPTION:
XS GIS Cut Line= 3
      2246837.70     13339396.88      2247537.72     13338596.85
      2247992.47     13338202.46
#Sta/Elev= 30
  3930.0  163.91  3965.6  162.99  4086.2  157.02  4121.3  156.36  4170.6  153.85
  4199.1  153.50  4241.8  151.21  4298.8  149.46  4313.0  148.06  4327.2  148.25
  4433.5  143.75  4595.8  138.35  4617.7  138.32  4687.9  134.96  4745.6  133.67
  4773.3  132.85  4780.3  133.41  4865.9  132.06  4890.9  131.54  4893.6  131.04
  4896.9  131.54  4922.3  132.13  5093.6  132.00  5127.4  133.38  5205.3  134.95
  5439.9  146.58  5496.1  147.32  5510.1  148.26  5524.4  147.64  5595.0  148.20
#Mann=7,-1,0
  3930.0     0.1       0  4745.6    0.12       0  4780.3     0.1       0
  4865.9    0.12       0  4890.9    0.07       0  4896.9    0.12       0
  5093.6     0.1       0
Bank Sta=4890.9,4896.9
Exp/Cntr=0.3,0.1

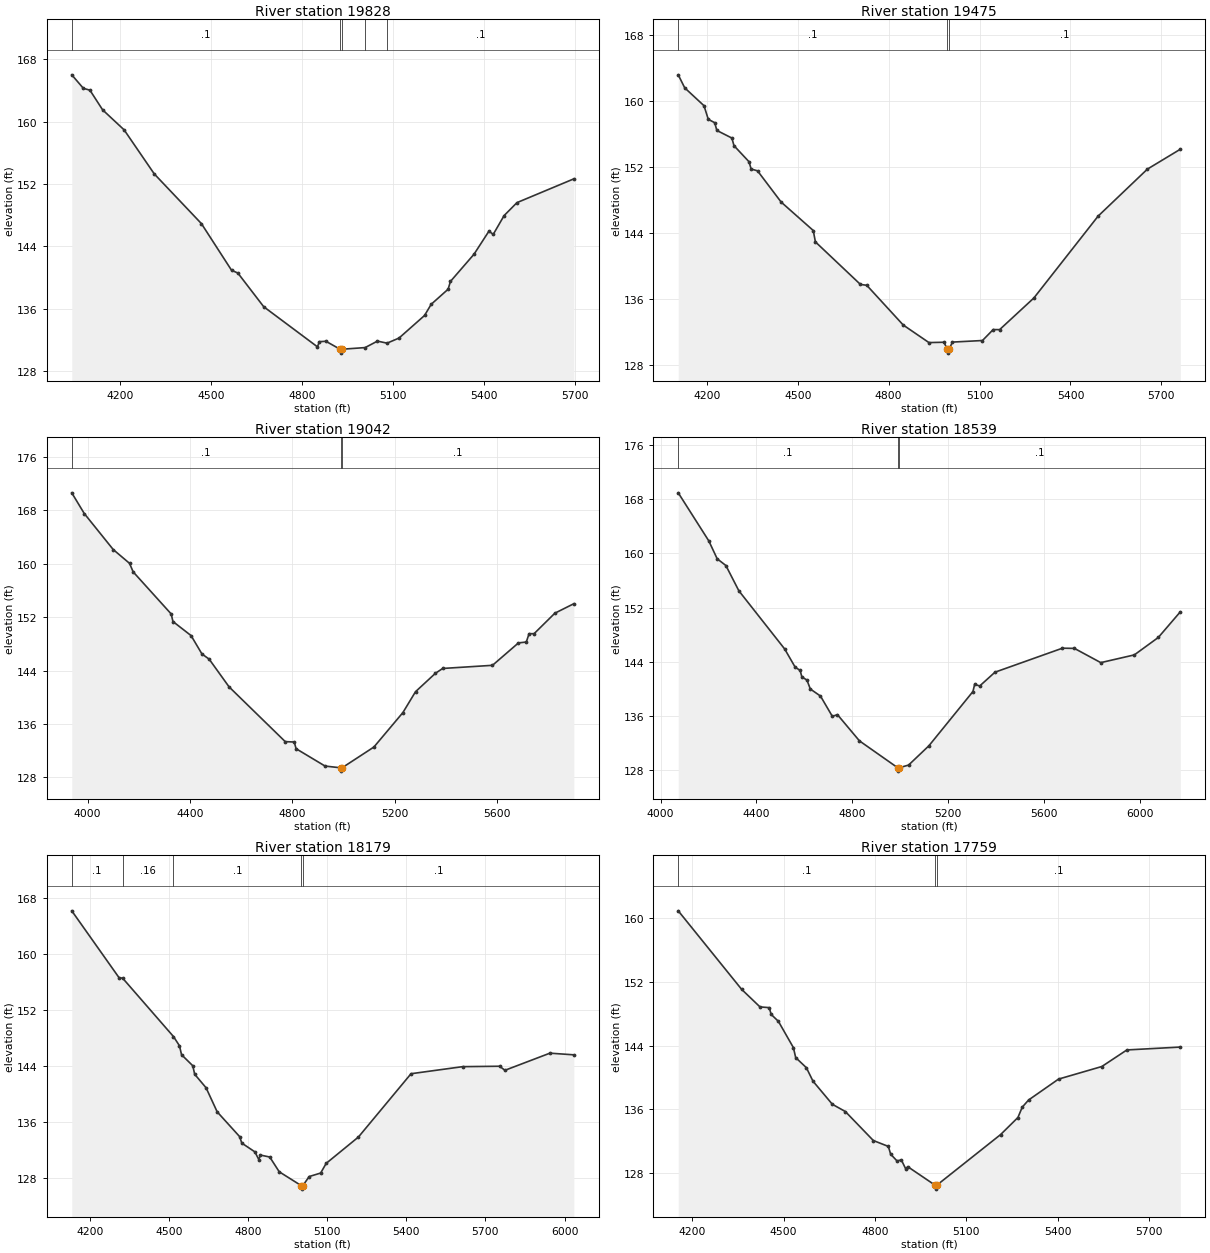
Type RM Length L Ch R = 1,19828,353,353,353
BEGIN DESCRIPTION:
UNT040 IN SPCR 38.0
END DESCRIPTION:
XS GIS Cut Line= 2
      2247092.36     13339615.64      2248327.70     13338511.60
#Sta/Elev= 30
  4039.3  166.01  4077.5  164.28  4099.2  164.04  4141.1  161.52  4212.1  158.95
  4311.6  153.30  4467.1  146.93  4566.5  140.95  4587.4  140.59  4672.7  136.27
  4849.9  131.13  4856.6  131.79  4878.0  131.84  4924.7  130.82  4927.4  130.32
  4930.7  130.82  5007.3  131.03  5048.0  131.86  5079.8  131.60  5119.1  132.25
  5203.5  135.15  5225.3  136.58  5281.3  138.52  5288.8  139.51  5366.6  143.00
  5415.9  145.96  5430.1  145.55  5466.0  147.96  5508.4  149.62  5696.1  152.67
#Mann=5,-1,0
  4039.3     0.1       0  4924.7    0.07       0  4930.7     0.1       0
  5007.3    0.12       0  5079.8     0.1       0
Bank Sta=4924.7,4930.7
Exp/Cntr=0.3,0.1

Type RM Length L Ch R = 1,19475,433,433,433
BEGIN DESCRIPTION:
UNT040 IN SPCR 37.0
END DESCRIPTION:
XS GIS Cut Line= 2
      2247390.80     13339890.24      2248553.78     13338709.36
#Sta/Elev= 30
  4105.3  163.22  4126.7  161.64  4190.4  159.47  4204.5  157.82  4225.7  157.41
  4232.8  156.47  4282.3  155.55  4289.4  154.62  4338.8  152.68  4346.0  151.79
  4367.1  151.57  4445.0  147.78  4551.0  144.33  4558.1  142.95  4706.6  137.79
  4727.7  137.68  4848.0  132.86  4932.9  130.73  4982.3  130.77  4993.5  129.95
  4996.2  129.45  4999.5  129.95  5010.6  130.79  5109.6  130.98  5145.0  132.31
  5166.2  132.30  5279.3  136.14  5491.5  146.08  5654.1  151.78  5762.7  154.19
#Mann=3,-1,0
  4105.3     0.1       0  4993.5    0.07       0  4999.5     0.1       0
Bank Sta=4993.5,4999.5
Exp/Cntr=0.3,0.1

Type RM Length L Ch R = 1,19042,503,503,503
BEGIN DESCRIPTION:
UNT040 IN SPCR 36.0
END DESCRIPTION:
XS GIS Cut Line= 3
      2247569.87     13340308.08      2248662.22     13339209.76
      2248733.85     13338803.87
#Sta/Elev= 30
  3937.9  170.63  3986.7  167.53  4099.9  162.13  4163.5  160.07  4177.7  158.79
  4326.1  152.49  4333.2  151.35  4404.0  149.24  4446.4  146.49  4474.7  145.71
  4552.4  141.56  4771.7  133.36  4807.0  133.30  4814.1  132.30  4927.2  129.70
  4987.8  129.44  4990.6  128.94  4993.8  129.44  5118.1  132.55  5231.3  137.71
  5280.7  140.84  5358.5  143.60  5386.8  144.32  5581.3  144.79  5682.8  148.15
  5713.3  148.28  5724.3  149.53  5743.8  149.53  5825.0  152.60  5899.1  154.02
#Mann=3,-1,0
  3937.9     0.1       0  4987.8    0.07       0  4993.8     0.1       0
Bank Sta=4987.8,4993.8
Exp/Cntr=0.3,0.1

Type RM Length L Ch R = 1,18539,360,360,360
BEGIN DESCRIPTION:
UNT040 IN SPCR 35.0
END DESCRIPTION:
XS GIS Cut Line= 4
      2247784.75     13340534.91      2248214.53     13340302.12
      2248865.17     13339651.48      2248883.08     13338965.03
#Sta/Elev= 30
  4073.5  168.92  4201.1  161.83  4236.1  159.19  4272.4  158.20  4326.6  154.47
  4517.8  145.89  4561.2  143.23  4582.4  142.72  4589.5  141.77  4610.7  141.31
  4624.8  139.99  4667.2  138.95  4716.7  135.96  4738.0  136.21  4829.9  132.34
  4989.5  128.38  4992.3  127.88  4995.5  128.38  5034.9  128.77  5119.8  131.62
  5303.6  139.62  5310.7  140.67  5331.9  140.44  5395.6  142.47  5677.1  146.01
  5727.1  145.98  5837.2  143.88  5977.2  145.02  6077.2  147.59  6169.1  151.37
#Mann=3,-1,0
  4073.5     0.1       0  4989.5    0.07       0  4995.5     0.1       0
Bank Sta=4989.5,4995.5
Exp/Cntr=0.3,0.1

Type RM Length L Ch R = 1,18179,420,420,420
BEGIN DESCRIPTION:
UNT040 IN SPCR 34.0
END DESCRIPTION:
XS GIS Cut Line= 4
      2247904.17     13340702.04      2248286.16     13340606.54
      2249032.31     13340033.51      2248984.55     13339466.46
#Sta/Elev= 30
  4131.6  166.23  4310.5  156.69  4324.8  156.59  4517.3  148.25  4539.9  146.94
  4547.8  145.66  4590.4  144.08  4597.7  142.86  4640.8  140.93  4682.9  137.49
  4768.0  133.95  4776.3  133.02  4826.1  131.76  4840.6  130.67  4846.9  131.31
  4882.2  131.03  4918.2  128.92  5001.7  126.94  5004.4  126.44  5007.7  126.94
  5031.8  128.24  5075.3  128.74  5096.1  130.12  5218.5  133.89  5417.9  142.94
  5613.3  143.95  5753.8  144.01  5773.9  143.43  5944.5  145.88  6035.2  145.64
#Mann=5,-1,0
  4131.6     0.1       0  4324.8    0.16       0  4517.3     0.1       0
  5001.7    0.07       0  5007.7     0.1       0
Bank Sta=5001.7,5007.7
Exp/Cntr=0.3,0.1

Type RM Length L Ch R = 1,17759,752,752,752
BEGIN DESCRIPTION:
UNT040 IN SPCR 33.0
END DESCRIPTION:
XS GIS Cut Line= 4
      2248101.11     13341101.99      2248405.55     13341066.17
      2249109.90     13340433.44      2249151.56     13340040.70
#Sta/Elev= 30
  4154.2  160.92  4362.2  151.07  4422.6  148.86  4452.9  148.77  4459.3  147.92
  4483.0  147.05  4532.3  143.75  4539.8  142.50  4574.9  141.23  4596.6  139.54
  4660.1  136.64  4702.8  135.73  4794.7  132.09  4844.0  131.35  4851.5  130.38
  4872.4  129.53  4886.6  129.66  4900.8  128.55  4907.6  128.81  4997.3  126.49
  5000.0  125.99  5003.3  126.49  5212.6  132.84  5269.4  134.98  5283.6  136.28
  5304.5  137.18  5402.7  139.80  5544.9  141.38  5627.1  143.46  5802.5  143.82
#Mann=3,-1,0
  4154.2     0.1       0  4997.3    0.07       0  5003.3     0.1       0
Bank Sta=4997.3,5003.3
Exp/Cntr=0.3,0.1

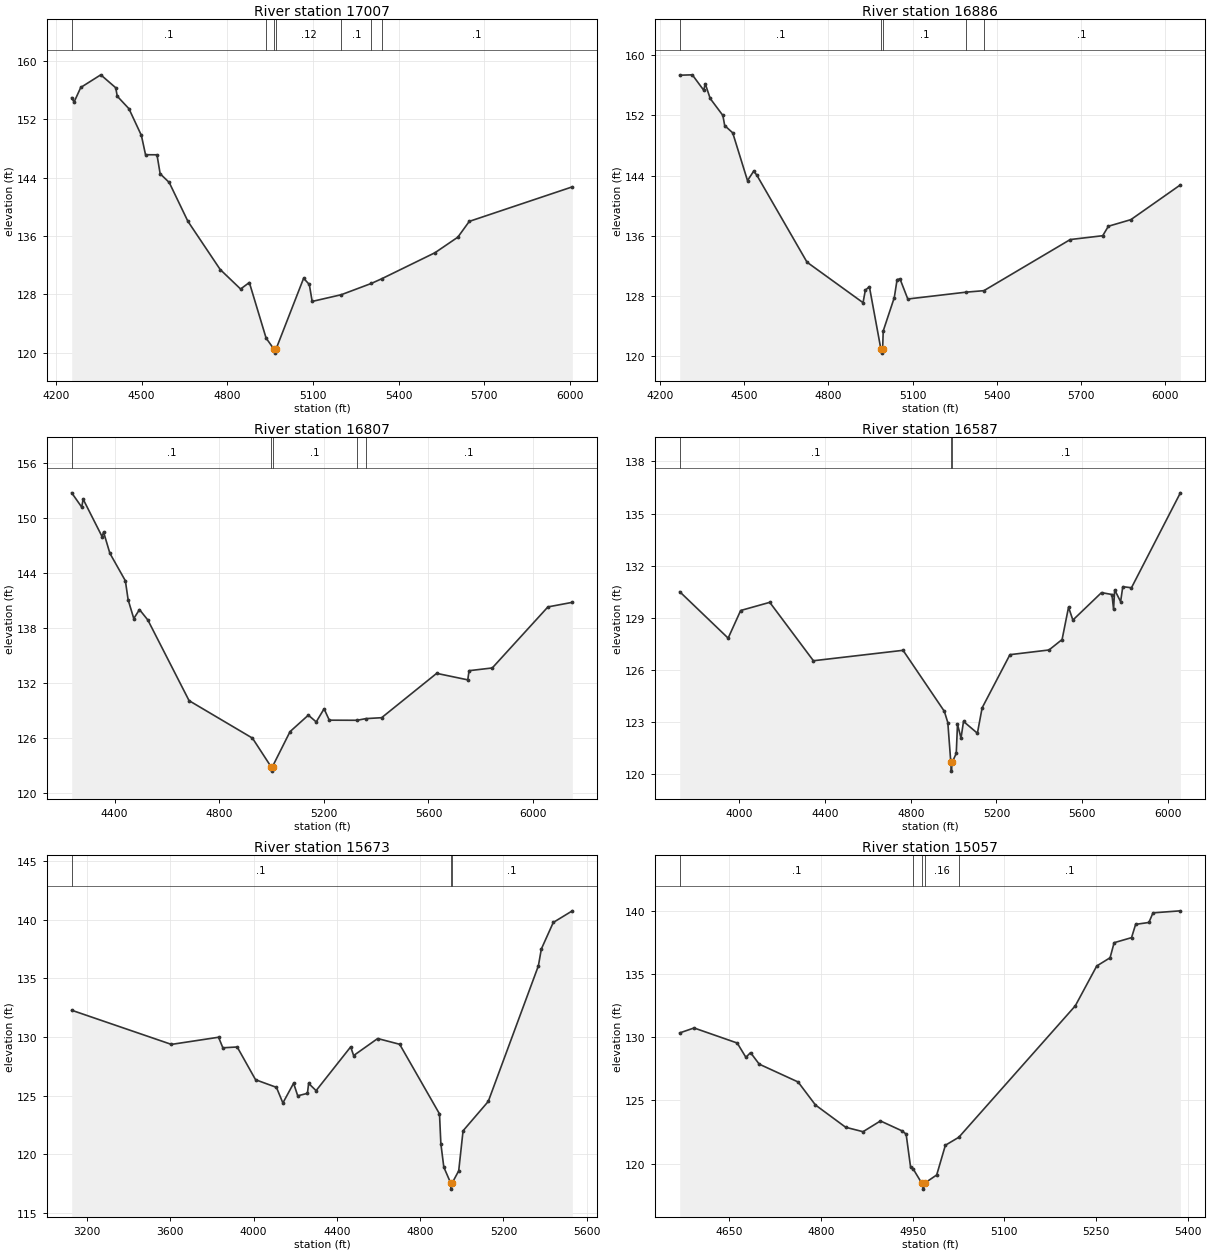
Type RM Length L Ch R = 1,17007,121,121,121
BEGIN DESCRIPTION:
Mapping XS adb4e2b6
END DESCRIPTION:
XS GIS Cut Line= 4
      2248674.13     13341734.72      2248960.68     13341609.36
      2249205.41     13341436.26      2249199.44     13340296.10
#Sta/Elev= 30
  4255.1  154.93  4263.4  154.33  4286.8  156.33  4356.9  158.06  4409.2  156.29
  4414.6  155.13  4455.5  153.42  4499.1  149.76  4513.6  147.12  4553.7  147.11
  4564.8  144.51  4596.5  143.32  4661.8  138.01  4775.0  131.40  4846.4  128.73
  4877.0  129.62  4935.7  122.01  4964.0  120.45  4966.8  119.95  4970.0  120.45
  5067.0  130.20  5087.0  129.35  5097.0  127.03  5199.0  127.95  5304.5  129.50
  5340.8  130.14  5527.0  133.70  5607.0  135.83  5647.0  137.99  6007.8  142.72
#Mann=7,-1,0
  4255.1     0.1       0  4935.7    0.12       0  4964.0    0.07       0
  4970.0    0.12       0  5199.0     0.1       0  5304.5    0.12       0
  5340.8     0.1       0
Bank Sta=4964,4970
Exp/Cntr=0.3,0.1

Type RM Length L Ch R = 1,16886,79,79,79
BEGIN DESCRIPTION:
Mapping XS f47b3f0d
END DESCRIPTION:
XS GIS Cut Line= 5
      2248757.75     13341788.42      2249205.41     13341585.48
      2249294.95     13341424.32      2249318.82     13341287.03
      2249241.30     13340320.96
#Sta/Elev= 30
  4270.1  157.36  4314.9  157.41  4355.5  155.36  4361.0  156.22  4378.6  154.26
  4423.8  152.00  4430.3  150.65  4458.9  149.68  4511.6  143.32  4533.6  144.58
  4544.6  144.06  4723.8  132.45  4923.4  127.06  4931.6  128.72  4946.0  129.19
  4987.2  120.84  4990.0  120.34  4993.2  120.84  4995.3  123.29  5034.8  127.74
  5044.8  130.14  5055.1  130.23  5082.9  127.55  5290.3  128.46  5354.2  128.66
  5662.0  135.47  5777.7  135.98  5797.8  137.24  5878.0  138.12  6054.5  142.75
#Mann=5,-1,0
  4270.1     0.1       0  4987.2    0.07       0  4993.2     0.1       0
  5290.3    0.12       0  5354.2     0.1       0
Bank Sta=4987.2,4993.2
Exp/Cntr=0.3,0.1

Type RM Length L Ch R = 1,16807,220,220,220
BEGIN DESCRIPTION:
Mapping XS 6655935e
END DESCRIPTION:
XS GIS Cut Line= 6
      2248817.42     13341836.19      2249235.26     13341669.05
      2249378.52     13341448.19      2249366.58     13340797.56
      2249288.98     13340308.09      2249283.00     13340254.32
#Sta/Elev= 30
  4236.3  152.76  4274.6  151.20  4280.0  152.07  4352.7  147.97  4358.1  148.48
  4382.3  146.16  4441.5  143.16  4452.0  141.09  4473.6  139.04  4495.4  140.02
  4527.4  138.88  4685.0  130.08  4927.3  125.99  4997.9  122.89  5000.7  122.39
  5003.9  122.89  5070.9  126.70  5140.9  128.50  5171.0  127.76  5201.0  129.19
  5221.0  127.95  5327.9  127.94  5360.6  128.12  5421.0  128.22  5631.4  133.06
  5750.3  132.35  5755.3  133.35  5844.0  133.65  6056.7  140.31  6150.0  140.81
#Mann=5,-1,0
  4236.3     0.1       0  4997.9    0.07       0  5003.9     0.1       0
  5327.9    0.12       0  5360.6     0.1       0
Bank Sta=4997.9,5003.9
Exp/Cntr=0.3,0.1

Type RM Length L Ch R = 1,16587,914,914,914
BEGIN DESCRIPTION:
Mapping XS 98664dc9
END DESCRIPTION:
XS GIS Cut Line= 4
      2250124.68     13342540.58      2249694.88     13341645.18
      2249527.74     13341298.97      2249372.80     13340351.41
#Sta/Elev= 30
  3721.0  130.50  3947.0  127.83  4005.4  129.42  4141.3  129.89  4345.1  126.53
  4763.8  127.13  4956.6  123.62  4972.8  122.97  4986.8  120.68  4989.6  120.18
  4992.8  120.68  5012.2  121.20  5018.0  122.88  5034.4  122.08  5046.1  123.04
  5110.9  122.36  5133.0  123.82  5262.9  126.88  5445.3  127.15  5506.4  127.75
  5536.5  129.61  5556.8  128.87  5690.5  130.45  5739.2  130.34  5746.8  129.49
  5751.9  130.61  5779.7  129.93  5789.8  130.79  5830.4  130.73  6058.8  136.19
#Mann=3,-1,0
  3721.0     0.1       0  4986.8    0.07       0  4992.8     0.1       0
Bank Sta=4986.8,4992.8
Exp/Cntr=0.3,0.1

Type RM Length L Ch R = 1,15673,616,616,616
BEGIN DESCRIPTION:
Mapping XS 3380664c
END DESCRIPTION:
XS GIS Cut Line= 3
      2250423.12     13342301.79      2250053.03     13340797.56
      2249504.24     13340141.39
#Sta/Elev= 30
  3126.2  132.28  3605.0  129.37  3831.6  129.98  3852.2  129.08  3921.1  129.15
  4009.3  126.36  4109.6  125.71  4140.5  124.38  4192.0  126.06  4211.8  124.99
  4258.5  125.20  4264.1  126.05  4300.0  125.43  4466.1  129.16  4480.3  128.42
  4595.8  129.87  4701.4  129.38  4892.7  123.45  4899.2  120.92  4913.5  118.91
  4946.9  117.54  4949.6  117.04  4952.9  117.54  4985.0  118.60  5005.9  122.01
  5126.9  124.51  5367.6  136.06  5381.9  137.50  5439.2  139.76  5530.7  140.75
#Mann=3,-1,0
  3126.2     0.1       0  4946.9    0.07       0  4952.9     0.1       0
Bank Sta=4946.9,4952.9
Exp/Cntr=0.3,0.1

Type RM Length L Ch R = 1,15057,676,676,676
BEGIN DESCRIPTION:
Mapping XS 63a26e80
END DESCRIPTION:
XS GIS Cut Line= 2
      2250405.23     13340272.30      2249791.54     13339730.10
#Sta/Elev= 30
  4569.0  130.33  4592.4  130.72  4663.0  129.53  4677.2  128.40  4684.8  128.77
  4699.0  127.86  4762.6  126.45  4791.0  124.63  4840.4  122.87  4868.8  122.52
  4897.3  123.37  4932.4  122.59  4939.3  122.33  4946.6  119.71  4950.4  119.61
  4964.5  118.48  4967.3  117.98  4970.5  118.48  4989.3  119.10  5003.5  121.45
  5025.5  122.08  5216.0  132.47  5251.1  135.62  5272.9  136.27  5279.5  137.46
  5308.0  137.86  5314.7  138.91  5336.4  139.06  5343.1  139.82  5387.9  139.98
#Mann=5,-1,0
  4569.0     0.1       0  4950.4    0.16       0  4964.5    0.07       0
  4970.5    0.16       0  5025.5     0.1       0
Bank Sta=4964.5,4970.5
Exp/Cntr=0.3,0.1