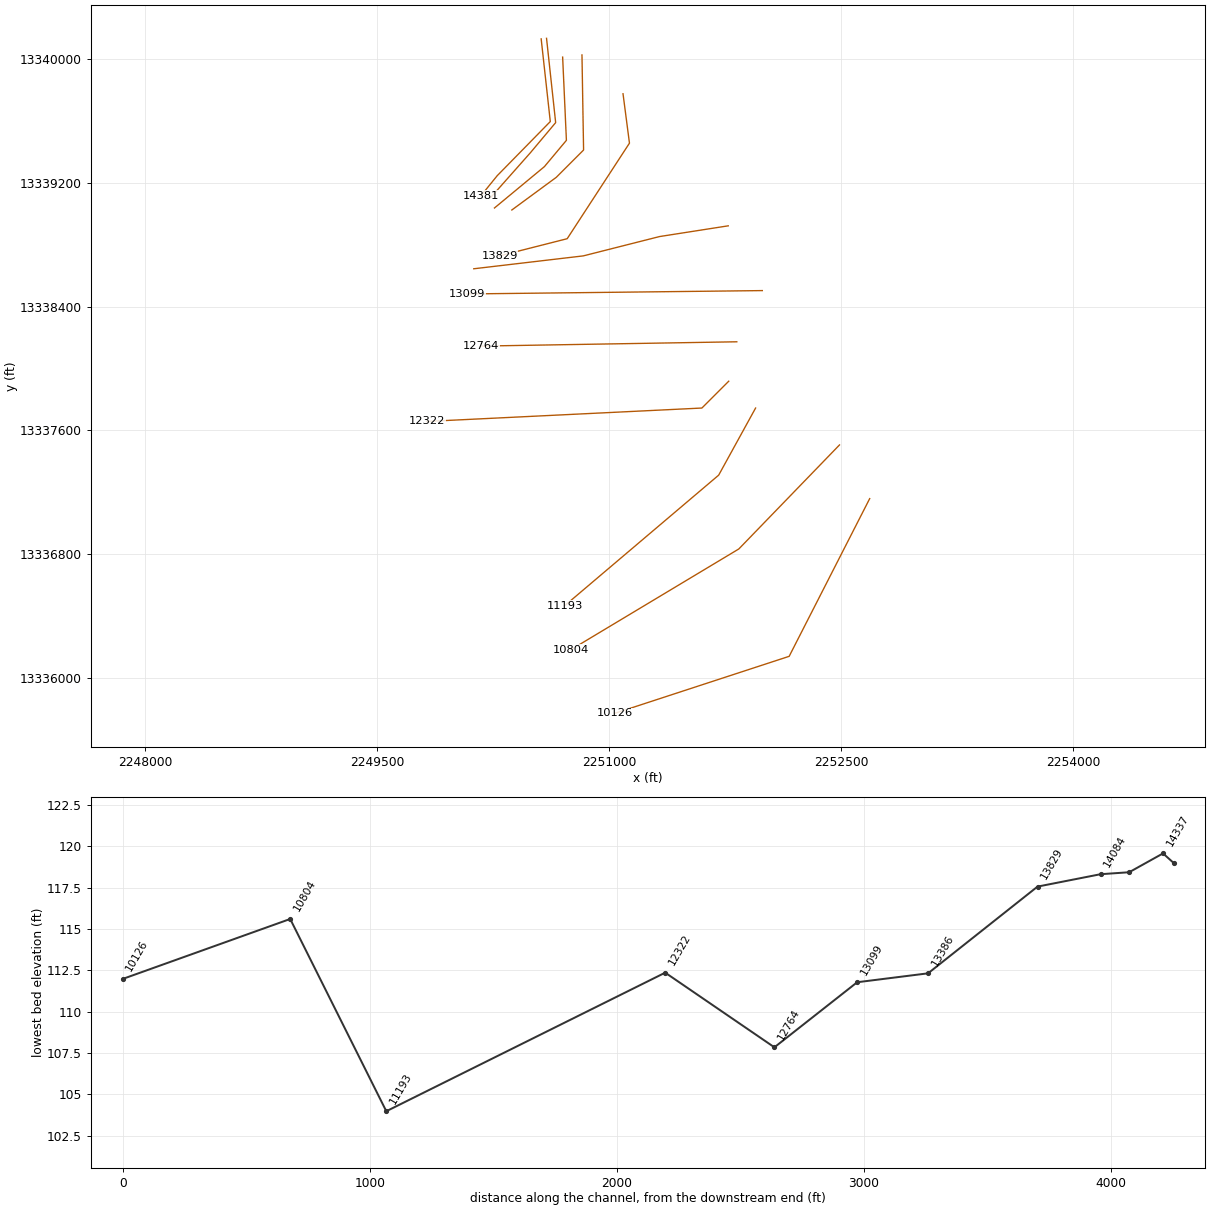
HEC-RAS study UNT040 IN SPCR.prj: UNT040 IN SPCR Base Level Engineering

--- UNT040 IN SPCR.g01 (geometry) --- (continued)

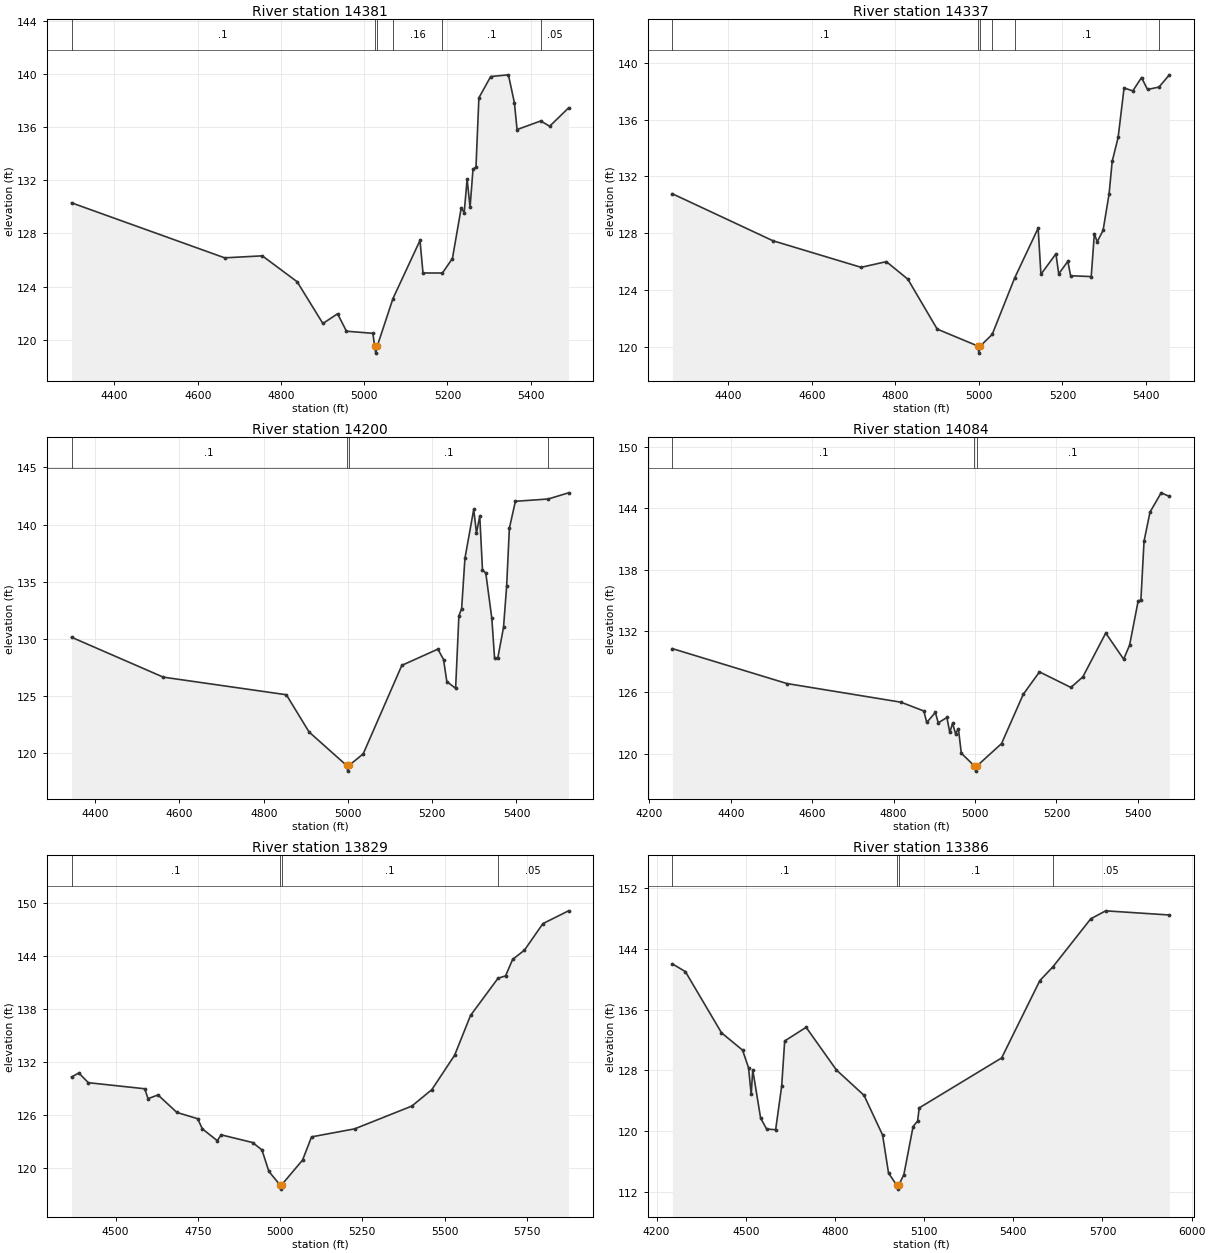
Type RM Length L Ch R = 1,14381,44,44,44
BEGIN DESCRIPTION:
Mapping XS 88464831
END DESCRIPTION:
XS GIS Cut Line= 4
      2250560.96     13340132.53      2250619.99     13339597.76
      2250276.24     13339247.07      2250172.38     13339118.97
#Sta/Elev= 30
  4296.8  130.30  4664.7  126.16  4755.2  126.31  4838.9  124.36  4900.7  121.22
  4936.0  121.95  4957.3  120.64  5020.9  120.48  5025.0  119.49  5027.8  118.99
  5031.0  119.49  5069.1  123.10  5134.0  127.47  5141.2  125.02  5187.9  125.02
  5211.9  126.11  5233.0  129.91  5240.2  129.57  5247.2  132.08  5254.3  129.96
  5261.3  132.82  5268.5  132.99  5275.5  138.20  5303.8  139.80  5346.4  139.93
  5360.8  137.83  5367.2  135.81  5424.1  136.46  5445.5  136.06  5490.8  137.44
#Mann=6,-1,0
  4296.8     0.1       0  5025.0    0.07       0  5031.0     0.1       0
  5069.1    0.16       0  5187.9     0.1       0  5424.1    0.05       0
Bank Sta=5025,5031
Exp/Cntr=0.3,0.1

Type RM Length L Ch R = 1,14337,137,137,137
BEGIN DESCRIPTION:
Mapping XS 18e2d382
END DESCRIPTION:
XS GIS Cut Line= 4
      2250595.69     13340135.95      2250654.71     13339590.82
      2250491.52     13339396.37      2250234.56     13339106.42
#Sta/Elev= 30
  4266.5  130.78  4507.0  127.48  4718.2  125.61  4778.6  126.01  4830.0  124.78
  4900.3  121.27  4997.4  120.08  5000.2  119.58  5003.4  120.08  5031.9  120.89
  5085.7  124.86  5141.9  128.36  5148.6  125.12  5184.5  126.56  5191.2  125.15
  5213.0  126.03  5219.7  125.02  5269.0  124.96  5276.5  127.98  5283.2  127.40
  5297.4  128.21  5311.7  130.76  5319.2  133.06  5333.4  134.74  5347.6  138.22
  5368.5  138.01  5389.4  138.95  5403.7  138.11  5431.1  138.28  5456.1  139.14
#Mann=6,-1,0
  4266.5     0.1       0  4997.4    0.07       0  5003.4     0.1       0
  5031.9    0.16       0  5085.7     0.1       0  5431.1    0.05       0
Bank Sta=4997.4,5003.4
Exp/Cntr=0.3,0.1

Type RM Length L Ch R = 1,14200,116,116,116
BEGIN DESCRIPTION:
Mapping XS 62b906d1
END DESCRIPTION:
XS GIS Cut Line= 4
      2250699.85     13340014.43      2250724.16     13339476.23
      2250581.80     13339306.09      2250258.90     13339038.75
#Sta/Elev= 30
  4343.8  130.15  4561.6  126.66  4853.8  125.12  4907.8  121.86  4996.7  118.94
  4999.5  118.44  5002.7  118.94  5036.2  119.95  5127.9  127.69  5213.5  129.11
  5226.9  128.20  5234.8  126.27  5255.6  125.68  5263.4  132.03  5269.9  132.65
  5277.7  137.05  5298.6  141.33  5305.1  139.27  5312.9  140.75  5319.4  136.03
  5327.2  135.77  5341.6  131.79  5348.1  128.30  5355.9  128.37  5369.3  131.01
  5376.7  134.60  5383.2  139.68  5397.5  142.04  5475.5  142.24  5523.6  142.78
#Mann=4,-1,0
  4343.8     0.1       0  4996.7    0.07       0  5002.7     0.1       0
  5475.5    0.05       0
Bank Sta=4996.7,5002.7
Exp/Cntr=0.3,0.1

Type RM Length L Ch R = 1,14084,255,255,255
BEGIN DESCRIPTION:
Mapping XS 6abc6c92
END DESCRIPTION:
XS GIS Cut Line= 4
      2250824.85     13340028.34      2250835.27     13339413.73
      2250658.19     13339236.65      2250371.35     13339025.84
#Sta/Elev= 30
  4256.5  130.28  4538.0  126.87  4818.1  125.05  4874.3  124.19  4881.4  123.07
  4902.6  124.05  4909.7  123.03  4930.9  123.56  4938.0  122.11  4945.0  122.99
  4952.1  121.98  4959.2  122.46  4966.3  120.07  4998.6  118.82  5001.4  118.32
  5004.6  118.82  5065.2  121.01  5118.4  125.81  5158.4  128.01  5235.6  126.49
  5264.9  127.52  5321.2  131.80  5365.2  129.25  5379.8  130.62  5400.7  134.90
  5407.6  135.04  5415.3  140.77  5430.0  143.61  5457.3  145.49  5477.6  145.14
#Mann=3,-1,0
  4256.5     0.1       0  4998.6    0.07       0  5004.6     0.1       0
Bank Sta=4998.6,5004.6
Exp/Cntr=0.3,0.1

Type RM Length L Ch R = 1,13829,443,443,443
BEGIN DESCRIPTION:
UNT040 IN SPCR 26.0
END DESCRIPTION:
XS GIS Cut Line= 4
      2251090.33     13339777.55      2251132.00     13339458.09
      2250729.22     13338840.04      2250292.17     13338729.04
#Sta/Elev= 30
  4365.9  130.27  4388.1  130.73  4417.0  129.63  4588.5  128.94  4598.5  127.82
  4628.8  128.24  4686.2  126.26  4749.2  125.55  4763.6  124.40  4808.9  123.06
  4820.9  123.72  4916.3  122.85  4944.7  122.02  4965.8  119.58  4999.0  118.07
  5001.7  117.57  5005.0  118.07  5068.4  120.87  5095.5  123.49  5226.7  124.40
  5400.4  126.98  5461.2  128.84  5530.5  132.74  5578.9  137.25  5662.4  141.46
  5685.3  141.73  5706.9  143.60  5742.7  144.64  5798.8  147.65  5876.7  149.10
#Mann=4,-1,0
  4365.9     0.1       0  4999.0    0.07       0  5005.0     0.1       0
  5662.4    0.05       0
Bank Sta=4999,5005
Exp/Cntr=0.3,0.1

Type RM Length L Ch R = 1,13386,287,287,287
BEGIN DESCRIPTION:
Mapping XS 62f324b3
END DESCRIPTION:
XS GIS Cut Line= 4
      2251770.87     13338923.37      2251326.44     13338853.93
      2250833.39     13338728.93      2250125.05     13338645.59
#Sta/Elev= 30
  4253.4  142.04  4297.1  141.02  4418.5  132.95  4489.4  130.66  4509.6  128.32
  4518.5  124.81  4523.6  128.08  4550.1  121.70  4570.3  120.25  4600.7  120.16
  4621.0  125.93  4631.1  131.87  4703.2  133.67  4805.1  128.04  4897.9  124.70
  4960.4  119.46  4980.4  114.44  5008.4  112.82  5011.1  112.32  5014.4  112.82
  5032.0  114.24  5063.0  120.58  5078.2  121.30  5083.6  123.04  5360.8  129.63
  5489.4  139.84  5533.7  141.67  5660.6  147.99  5711.0  149.04  5925.1  148.49
#Mann=4,-1,0
  4253.4     0.1       0  5008.4    0.07       0  5014.4     0.1       0
  5533.7    0.05       0
Bank Sta=5008.4,5014.4
Exp/Cntr=0.3,0.1

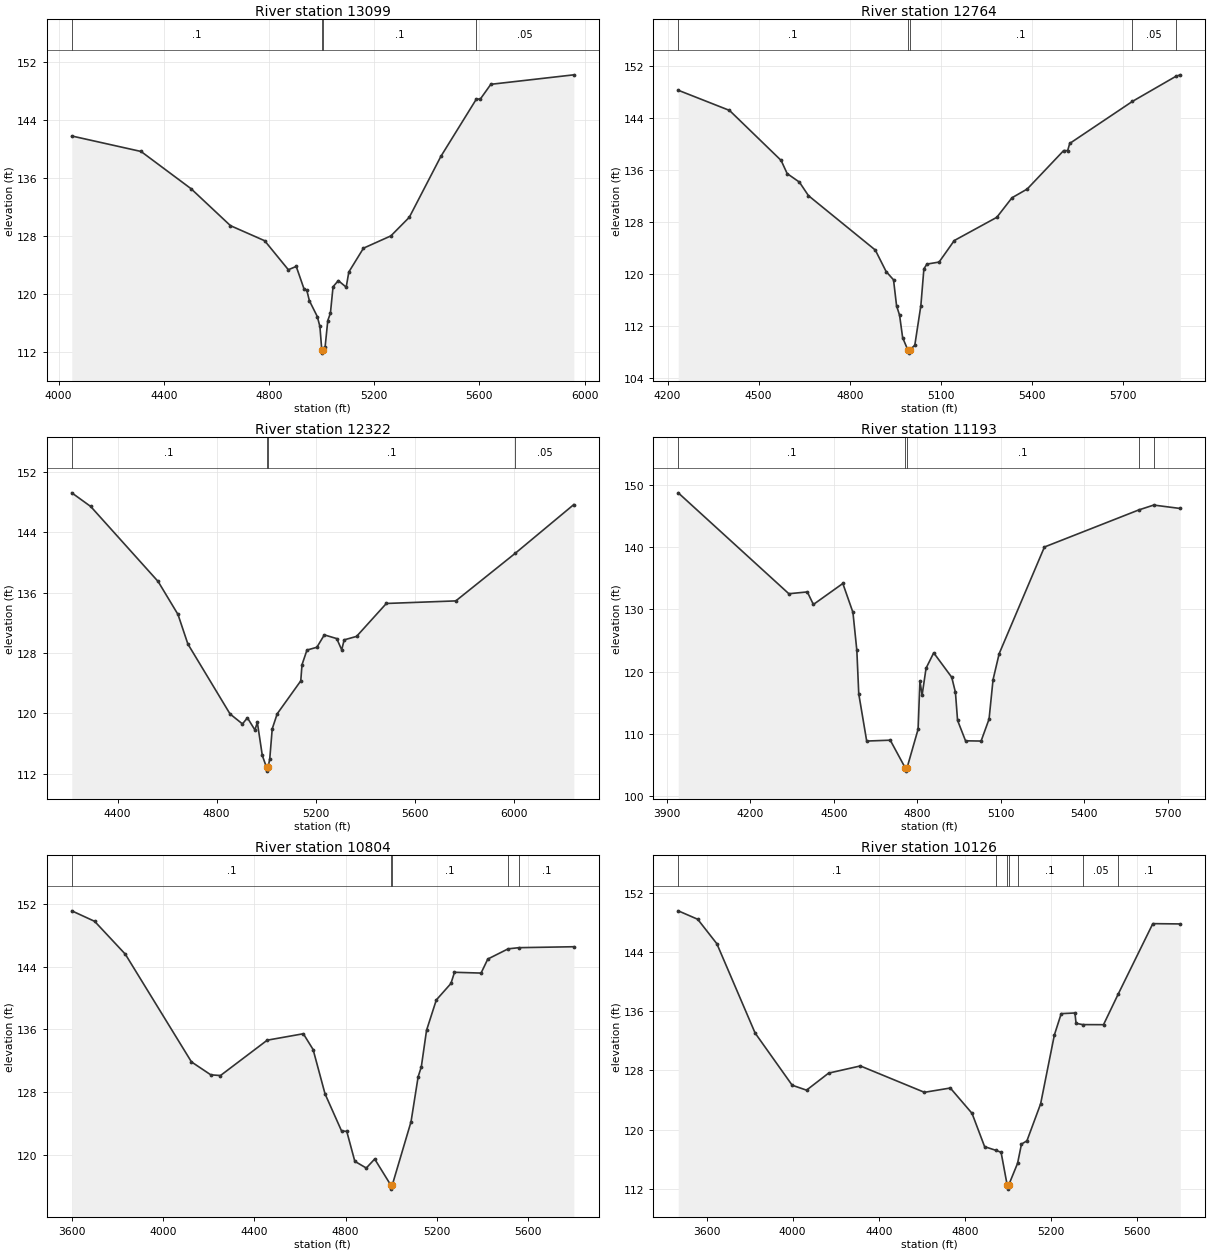
Type RM Length L Ch R = 1,13099,335,335,335
BEGIN DESCRIPTION:
UNT040 IN SPCR 25.0
END DESCRIPTION:
XS GIS Cut Line= 2
      2251991.22     13338504.47      2250082.04     13338482.77
#Sta/Elev= 30
  4049.8  141.78  4313.3  139.64  4503.3  134.50  4653.3  129.39  4783.3  127.31
  4873.4  123.30  4903.4  123.76  4933.4  120.61  4943.4  120.49  4953.4  119.02
  4983.4  116.84  4993.4  115.46  5000.4  112.28  5003.1  111.78  5006.4  112.28
  5013.4  112.69  5023.4  116.28  5033.4  117.30  5043.4  120.95  5063.4  121.80
  5093.4  120.89  5103.4  122.99  5159.1  126.28  5263.4  127.98  5333.4  130.55
  5453.4  138.96  5588.4  146.88  5603.4  146.88  5643.4  148.92  5959.1  150.23
#Mann=4,-1,0
  4049.8     0.1       0  5000.4    0.07       0  5006.4     0.1       0
  5588.4    0.05       0
Bank Sta=5000.4,5006.4
Exp/Cntr=0.3,0.1

Type RM Length L Ch R = 1,12764,442,442,442
BEGIN DESCRIPTION:
UNT040 IN SPCR 24.0
END DESCRIPTION:
XS GIS Cut Line= 2
      2251826.42     13338173.37      2250173.65     13338145.59
#Sta/Elev= 30
  4235.3  148.26  4404.0  145.16  4574.0  137.47  4594.0  135.44  4634.1  134.14
  4664.1  132.05  4884.1  123.69  4919.8  120.38  4944.1  119.11  4954.1  115.13
  4964.1  113.65  4974.1  110.22  4991.1  108.34  4993.9  107.84  4997.1  108.34
  5014.1  109.04  5034.1  115.15  5044.1  120.80  5054.1  121.53  5094.1  121.84
  5144.1  125.15  5284.1  128.72  5334.2  131.73  5384.2  133.07  5504.2  138.98
  5517.4  138.98  5524.2  140.08  5730.5  146.54  5873.0  150.38  5888.3  150.63
#Mann=5,-1,0
  4235.3     0.1       0  4991.1    0.07       0  4997.1     0.1       0
  5730.5    0.05       0  5873.0     0.1       0
Bank Sta=4991.1,4997.1
Exp/Cntr=0.3,0.1

Type RM Length L Ch R = 1,12322,1129,1129,1129
BEGIN DESCRIPTION:
UNT040 IN SPCR 23.0
END DESCRIPTION:
XS GIS Cut Line= 3
      2251774.17     13337918.53      2251600.56     13337744.92
      2249821.90     13337658.15
#Sta/Elev= 30
  4215.2  149.21  4291.7  147.40  4563.7  137.47  4643.8  133.11  4683.8  129.19
  4854.0  119.93  4904.1  118.61  4924.1  119.42  4954.2  117.82  4964.2  118.80
  4984.2  114.43  5001.2  112.86  5004.0  112.36  5007.2  112.86  5014.2  113.96
  5024.2  117.96  5044.3  119.95  5139.4  124.31  5144.4  126.45  5164.4  128.39
  5204.4  128.76  5234.5  130.40  5284.5  129.91  5304.6  128.42  5314.6  129.74
  5364.6  130.20  5484.8  134.56  5765.1  134.90  6004.5  141.19  6241.5  147.66
#Mann=4,-1,0
  4215.2     0.1       0  5001.2    0.07       0  5007.2     0.1       0
  6004.5    0.05       0
Bank Sta=5001.2,5007.2
Exp/Cntr=0.3,0.1

Type RM Length L Ch R = 1,11193,389,389,389
BEGIN DESCRIPTION:
UNT040 IN SPCR 22.0
END DESCRIPTION:
XS GIS Cut Line= 3
      2251947.77     13337744.90      2251709.06     13337310.89
      2250711.78     13336465.36
#Sta/Elev= 30
  3941.7  148.76  4338.9  132.52  4405.2  132.81  4427.0  130.79  4532.7  134.17
  4569.0  129.52  4583.0  123.40  4589.9  116.40  4618.4  108.81  4703.0  108.95
  4757.1  104.47  4759.9  103.97  4763.1  104.47  4803.0  110.72  4809.5  118.52
  4817.3  116.18  4831.6  120.54  4859.0  123.01  4923.8  119.07  4937.0  116.66
  4944.7  112.14  4973.3  108.85  5029.2  108.81  5057.8  112.35  5072.1  118.69
  5094.1  122.88  5256.6  140.04  5595.6  146.01  5649.0  146.79  5744.5  146.24
#Mann=5,-1,0
  3941.7     0.1       0  4757.1    0.07       0  4763.1     0.1       0
  5595.6    0.05       0  5649.0     0.1       0
Bank Sta=4757.1,4763.1
Exp/Cntr=0.3,0.1

Type RM Length L Ch R = 1,10804,678,678,678
BEGIN DESCRIPTION:
UNT040 IN SPCR 20.0
END DESCRIPTION:
XS GIS Cut Line= 3
      2252490.30     13337506.19      2251839.27     13336833.46
      2250754.17     13336182.40
#Sta/Elev= 30
  3599.2  151.11  3699.5  149.77  3834.0  145.58  4124.0  131.84  4208.8  130.19
  4251.3  130.10  4456.3  134.61  4614.6  135.43  4657.4  133.42  4709.8  127.76
  4782.1  123.04  4805.1  122.97  4840.4  119.16  4890.6  118.30  4927.5  119.45
  4998.4  116.11  5001.1  115.61  5004.4  116.11  5086.9  124.21  5118.0  129.94
  5131.9  131.20  5154.9  135.87  5197.7  139.74  5261.8  141.84  5277.4  143.27
  5394.0  143.17  5423.5  144.96  5512.6  146.26  5559.8  146.41  5800.8  146.53
#Mann=5,-1,0
  3599.2     0.1       0  4998.4    0.07       0  5004.4     0.1       0
  5512.6    0.05       0  5559.8     0.1       0
Bank Sta=4998.4,5004.4
Exp/Cntr=0.3,0.1

Type RM Length L Ch R = 1,10126,0,0,0
BEGIN DESCRIPTION:
UNT040 IN SPCR 1.0
END DESCRIPTION:
XS GIS Cut Line= 3
      2252685.64     13337159.01      2252164.79     13336139.02
      2251036.35     13335770.10
#Sta/Elev= 30
  3468.3  149.55  3558.8  148.41  3647.7  145.11  3825.5  133.05  3997.6  126.01
  4064.3  125.34  4166.9  127.64  4314.4  128.61  4612.0  125.05  4732.3  125.63
  4833.2  122.21  4891.7  117.71  4945.0  117.21  4968.2  116.95  4996.8  112.48
  4999.5  111.98  5002.8  112.48  5044.7  115.46  5062.9  118.06  5088.2  118.50
  5151.9  123.50  5215.7  132.79  5247.5  135.67  5311.3  135.76  5316.5  134.36
  5347.3  134.19  5444.0  134.18  5512.1  138.30  5673.1  147.82  5800.8  147.78
#Mann=7,-1,0
  3468.3     0.1       0  4945.0    0.07       0  4996.8    0.07       0
  5002.8    0.07       0  5044.7     0.1       0  5347.3    0.05       0
  5512.1     0.1       0
Bank Sta=4996.8,5002.8
Exp/Cntr=0.3,0.1

Chan Stop Cuts=-1