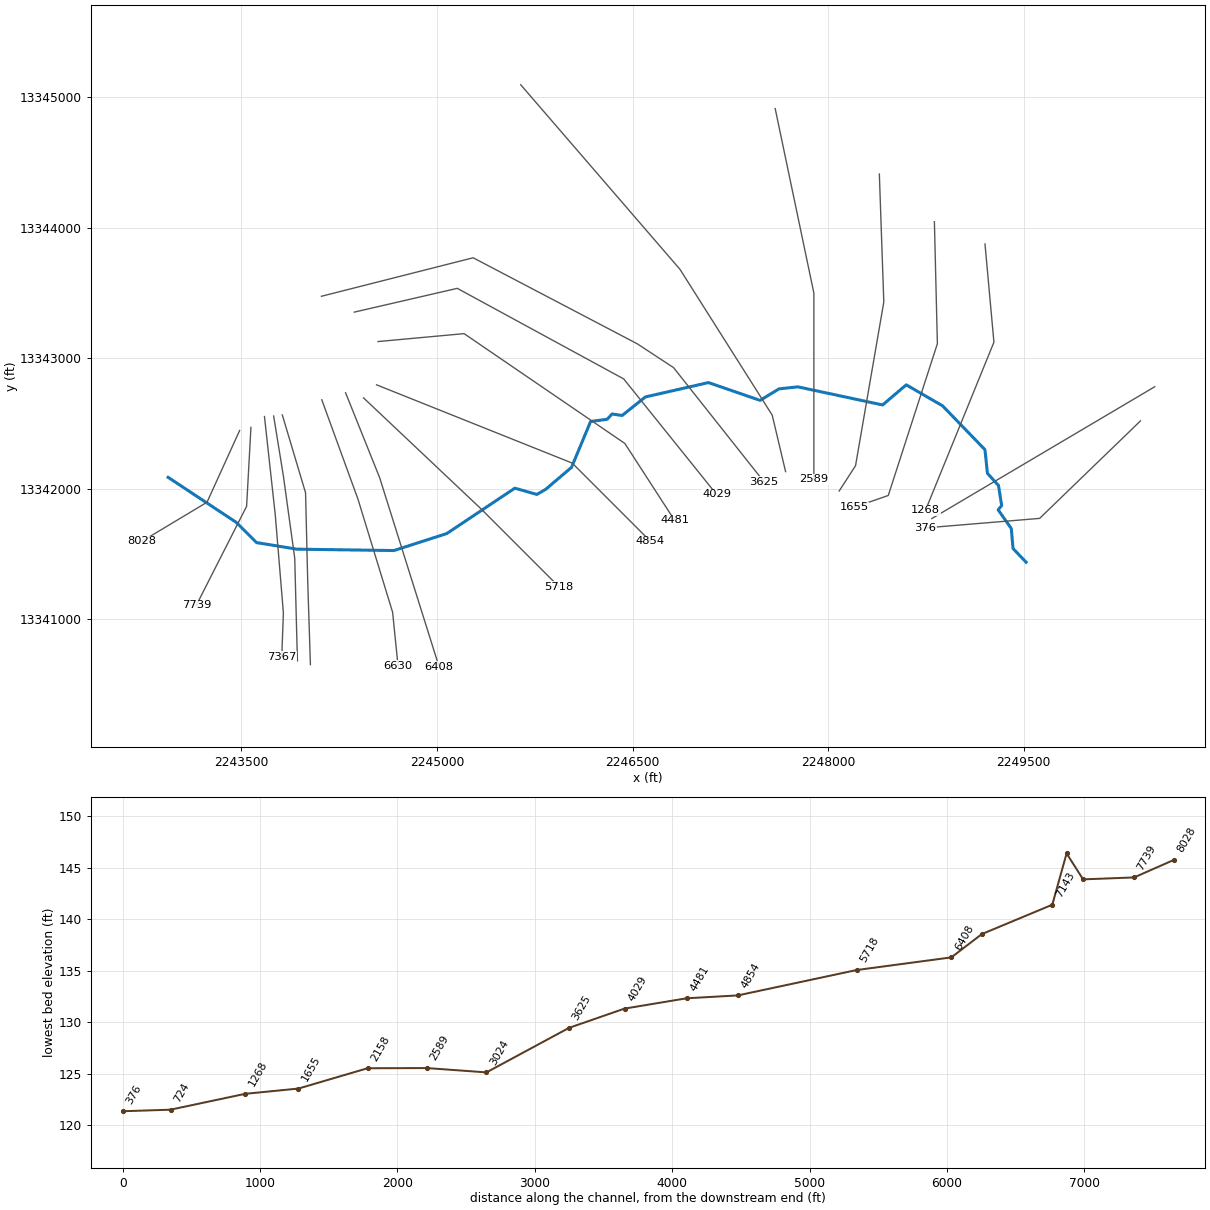
--- UNT041 IN SPCR.prj (project) ---

Proj Title=UNT041 IN SPCR Base Level Engineering
Current Plan=p01
Default Exp/Contr=0.3,0.1
English Units
Geom File=g01
Flow File=f01
Plan File=p01
BEGIN DESCRIPTION:
UNT041 IN SPCR
END DESCRIPTION:

--- UNT041 IN SPCR.p01 (plan) ---

Plan Title=Multiple Run
Short Identifier=Multiple
Geom File=g01
Flow File=f01
Subcritical Flow
K Sum by GR= 0
Std Step Tol= 0.01
Critical Tol= 0.01
Num of Std Step Trials= 20
Max Error Tol= 0.3
Flow Tol Ratio= 0.001
Split Flow NTrial= 30
Split Flow Tol= 0.02
Split Flow Ratio= 0.02
Log Output Level= 0
Friction Slope Method= 1
Unsteady Friction Slope Method= 2
Unsteady Bridges Friction Slope Method= 1
Parabolic Critical Depth
Global Vel Dist=  1 , 1 , 1
Global Log Level= 0
CheckData=True
Encroach Param= -1, 0, 0, 0
BEGIN DESCRIPTION:
Multiple Run
END DESCRIPTION:

--- UNT041 IN SPCR.f01 (steady flow) ---

Flow Title=Multiple
Number of Profiles=7
Profile Names=10-year,25-year,50-year,1pct_min,100-year,1pct_plu,500-year
River Rch & RM= UNT041 IN SPCR,Reach-1,8028
     185     252     306     274     371     502     553
River Rch & RM= UNT041 IN SPCR,Reach-1,1655
     200     274     334     300     406     549     609
Boundary for River Rch & Prof#=UNT041 IN SPCR,Reach-1,1
Up Type=0
Dn Type=3
Dn Slope=0.005
Boundary for River Rch & Prof#=UNT041 IN SPCR,Reach-1,2
Up Type=0
Dn Type=3
Dn Slope=0.005
Boundary for River Rch & Prof#=UNT041 IN SPCR,Reach-1,3
Up Type=0
Dn Type=3
Dn Slope=0.005
Boundary for River Rch & Prof#=UNT041 IN SPCR,Reach-1,4
Up Type=0
Dn Type=3
Dn Slope=0.005
Boundary for River Rch & Prof#=UNT041 IN SPCR,Reach-1,5
Up Type=0
Dn Type=3
Dn Slope=0.005
Boundary for River Rch & Prof#=UNT041 IN SPCR,Reach-1,6
Up Type=0
Dn Type=3
Dn Slope=0.005
Boundary for River Rch & Prof#=UNT041 IN SPCR,Reach-1,7
Up Type=0
Dn Type=3
Dn Slope=0.005

--- UNT041 IN SPCR.g01 (geometry) ---

Geom Title=Existing Conditions

River Reach=UNT041 IN SPCR,Reach-1
Reach XY= 30
      2242939.30     13342087.69      2243462.72     13341741.86
      2243617.21     13341587.35      2243927.38     13341536.85
      2244670.87     13341526.43      2245075.82     13341656.64
      2245597.71     13342004.65      2245766.51     13341956.53
      2245833.96     13341995.33      2246032.35     13342164.26
      2246178.79     13342515.83      2246305.68     13342532.89
      2246343.24     13342573.41      2246420.11     13342561.92
      2246598.95     13342704.04      2247082.23     13342814.26
      2247478.24     13342677.65      2247623.20     13342765.89
      2247767.69     13342781.52      2248417.64     13342642.62
      2248598.69     13342796.92      2248877.34     13342635.95
      2249202.29     13342299.61      2249221.28     13342118.32
      2249306.04     13342025.25      2249330.53     13341871.27
      2249303.46     13341838.41      2249404.06     13341695.40
      2249417.71     13341541.85      2249517.72     13341436.86

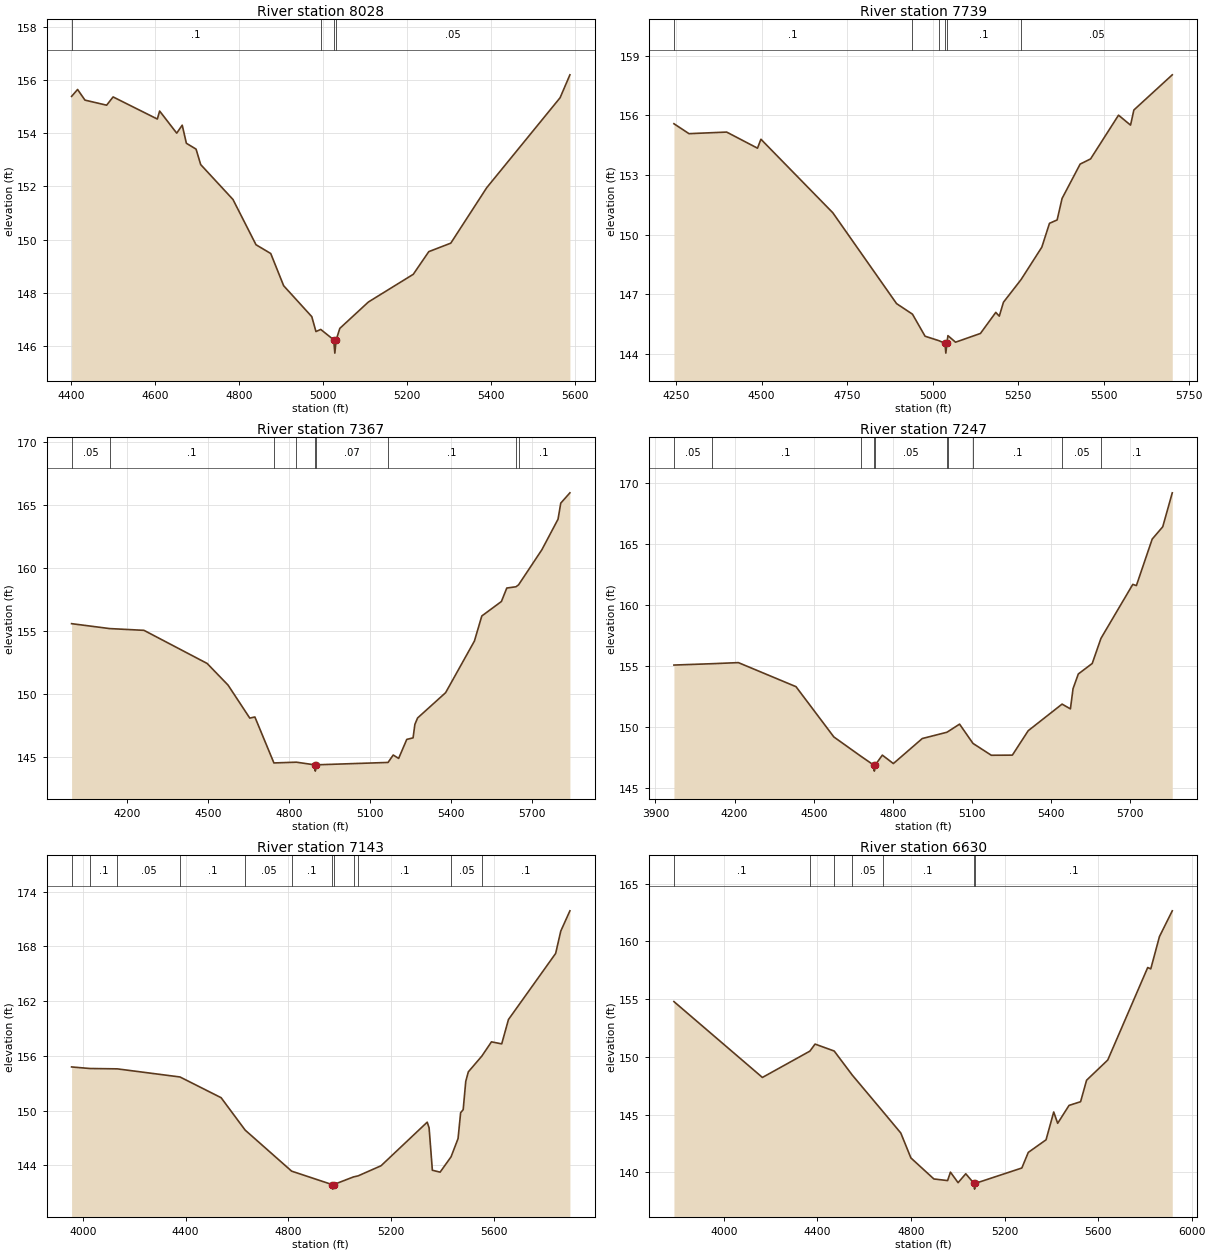
Type RM Length L Ch R = 1,8028,289,289,289
BEGIN DESCRIPTION:
UNT041 IN SPCR 17.0
END DESCRIPTION:
XS GIS Cut Line= 3
      2243487.72     13342446.86      2243237.72     13341896.85
      2242737.68     13341596.83
#Sta/Elev= 30
  4401.2  155.38  4415.5  155.64  4433.1  155.24  4484.7  155.05  4500.1  155.36
  4605.5  154.53  4611.0  154.83  4651.7  154.00  4664.8  154.30  4674.7  153.62
  4697.8  153.40  4708.8  152.82  4785.7  151.51  4840.6  149.81  4875.7  149.48
  4906.5  148.27  4973.5  147.11  4983.4  146.55  4994.8  146.63  5025.7  146.24
  5028.4  145.74  5031.7  146.24  5040.3  146.67  5108.4  147.66  5215.3  148.70
  5252.2  149.55  5304.7  149.87  5390.2  151.95  5565.1  155.33  5588.5  156.19
#Mann=4,-1,0
  4401.2     0.1       0  4994.8    0.05       0  5025.7    0.03       0
  5031.7    0.05       0
Bank Sta=5025.7,5031.7
Exp/Cntr=0.3,0.1

Type RM Length L Ch R = 1,7739,372,372,372
BEGIN DESCRIPTION:
Mapping XS 5fa198d8
END DESCRIPTION:
XS GIS Cut Line= 3
      2243574.38     13342470.86      2243541.21     13341865.52
      2243155.59     13341106.73
#Sta/Elev= 30
  4243.4  155.58  4287.5  155.08  4397.6  155.16  4487.8  154.35  4497.8  154.80
  4708.1  151.10  4894.5  146.53  4941.0  146.00  4977.9  144.89  5017.7  144.67
  5035.8  144.54  5038.6  144.04  5041.8  144.54  5044.7  144.92  5067.0  144.59
  5139.8  145.03  5184.7  146.09  5194.9  145.90  5207.1  146.60  5258.6  147.74
  5319.3  149.37  5341.7  150.57  5364.1  150.74  5378.5  151.82  5431.4  153.55
  5461.9  153.81  5543.6  156.01  5578.8  155.51  5588.5  156.27  5700.8  158.04
#Mann=6,-1,0
  4243.4     0.1       0  4941.0    0.05       0  5017.7     0.1       0
  5035.8    0.03       0  5041.8     0.1       0  5258.6    0.05       0
Bank Sta=5035.8,5041.8
Exp/Cntr=0.3,0.1

Type RM Length L Ch R = 1,7367,120,120,120
BEGIN DESCRIPTION:
Mapping XS 4ae60163
END DESCRIPTION:
XS GIS Cut Line= 4
      2243678.04     13342553.75      2243760.96     13341799.18
      2243823.15     13341048.71      2243810.72     13340712.90
#Sta/Elev= 30
  3993.6  155.56  4134.6  155.17  4262.1  155.03  4496.4  152.40  4574.0  150.68
  4654.5  148.06  4673.4  148.15  4744.0  144.50  4827.4  144.56  4894.8  144.35
  4897.6  143.85  4900.8  144.35  5167.3  144.54  5186.5  145.13  5206.6  144.86
  5236.7  146.37  5260.1  146.49  5266.8  147.56  5276.8  148.07  5380.8  150.08
  5487.6  154.18  5515.0  156.17  5587.7  157.32  5607.7  158.39  5641.6  158.49
  5651.2  158.64  5737.8  161.43  5797.8  163.86  5807.8  165.13  5841.8  165.95
#Mann=9,-1,0
  3993.6    0.05       0  4134.6     0.1       0  4744.0    0.05       0
  4827.4    0.07       0  4894.8    0.07       0  4900.8    0.07       0
  5167.3     0.1       0  5641.6    0.05       0  5651.2     0.1       0
Bank Sta=4894.8,4900.8
Exp/Cntr=0.3,0.1

Type RM Length L Ch R = 1,7247,104,104,104
BEGIN DESCRIPTION:
Mapping XS bc53d79f
END DESCRIPTION:
XS GIS Cut Line= 5
      2243748.51     13342557.99      2243823.15     13342097.71
      2243910.22     13341467.48      2243926.81     13340828.96
      2243930.93     13340680.77
#Sta/Elev= 30
  3970.0  155.06  4113.9  155.17  4214.3  155.26  4432.8  153.29  4576.4  149.17
  4677.6  147.61  4727.2  146.87  4729.9  146.37  4733.2  146.87  4760.2  147.68
  4802.0  146.99  4911.6  149.04  5004.2  149.55  5008.5  149.60  5053.0  150.22
  5103.9  148.64  5173.4  147.67  5253.2  147.68  5313.2  149.68  5441.7  151.86
  5473.3  151.47  5483.3  153.13  5503.3  154.33  5556.0  155.19  5589.2  157.25
  5709.8  161.67  5723.4  161.57  5783.4  165.38  5823.4  166.39  5859.5  169.17
#Mann=10,-1,0
  3970.0    0.05       0  4113.9     0.1       0  4677.6    0.05       0
  4727.2   0.035       0  4733.2    0.05       0  5004.2     0.1       0
  5008.5    0.05       0  5103.9     0.1       0  5441.7    0.05       0
  5589.2     0.1       0
Bank Sta=4727.2,4733.2
Exp/Cntr=0.3,0.1

Type RM Length L Ch R = 1,7143,513,513,513
BEGIN DESCRIPTION:
UNT041 IN SPCR 15.0
END DESCRIPTION:
XS GIS Cut Line= 4
      2243814.87     13342566.20      2243993.15     13341969.18
      2244009.74     13341289.19      2244030.45     13340651.28
#Sta/Elev= 30
  3955.5  154.78  4026.6  154.61  4133.5  154.57  4378.0  153.68  4538.1  151.41
  4631.7  147.86  4812.8  143.36  4970.5  141.89  4973.3  141.39  4976.5  141.89
  5054.0  142.73  5071.6  142.84  5161.1  143.95  5341.1  148.73  5348.4  148.10
  5361.1  143.46  5391.2  143.25  5433.9  144.93  5461.2  146.93  5471.2  149.76
  5481.2  150.10  5491.2  153.20  5501.2  154.24  5554.1  155.98  5591.3  157.53
  5631.3  157.31  5657.6  159.98  5841.4  167.22  5861.4  169.67  5897.0  171.89
#Mann=12,-1,0
  3955.5    0.05       0  4026.6     0.1       0  4133.5    0.05       0
  4378.0     0.1       0  4631.7    0.05       0  4812.8     0.1       0
  4970.5    0.07       0  4976.5     0.1       0  5054.0    0.05       0
  5071.6     0.1       0  5433.9    0.05       0  5554.1     0.1       0
Bank Sta=4970.5,4976.5
Exp/Cntr=0.3,0.1

Type RM Length L Ch R = 1,6630,222,222,222
BEGIN DESCRIPTION:
UNT041 IN SPCR 14.0
END DESCRIPTION:
XS GIS Cut Line= 4
      2244117.54     13342682.34      2244395.34     13341919.42
      2244660.70     13341052.86      2244702.16     13340642.36
#Sta/Elev= 30
  3786.3  154.78  4164.6  148.21  4367.6  150.49  4389.7  151.10  4471.5  150.50
  4548.7  148.42  4678.1  145.30  4756.3  143.40  4799.6  141.24  4897.8  139.42
  4956.5  139.28  4968.6  140.01  5001.3  139.10  5034.1  139.87  5069.1  139.04
  5071.8  138.54  5075.1  139.04  5273.9  140.37  5301.4  141.72  5377.4  142.81
  5410.2  145.22  5427.1  144.24  5475.7  145.79  5525.1  146.11  5550.7  147.97
  5641.2  149.72  5812.1  157.73  5825.1  157.61  5862.3  160.41  5917.1  162.64
#Mann=7,-1,0
  3786.3     0.1       0  4367.6    0.05       0  4471.5     0.1       0
  4548.7    0.05       0  4678.1     0.1       0  5069.1    0.07       0
  5075.1     0.1       0
Bank Sta=5069.1,5075.1
Exp/Cntr=0.3,0.1

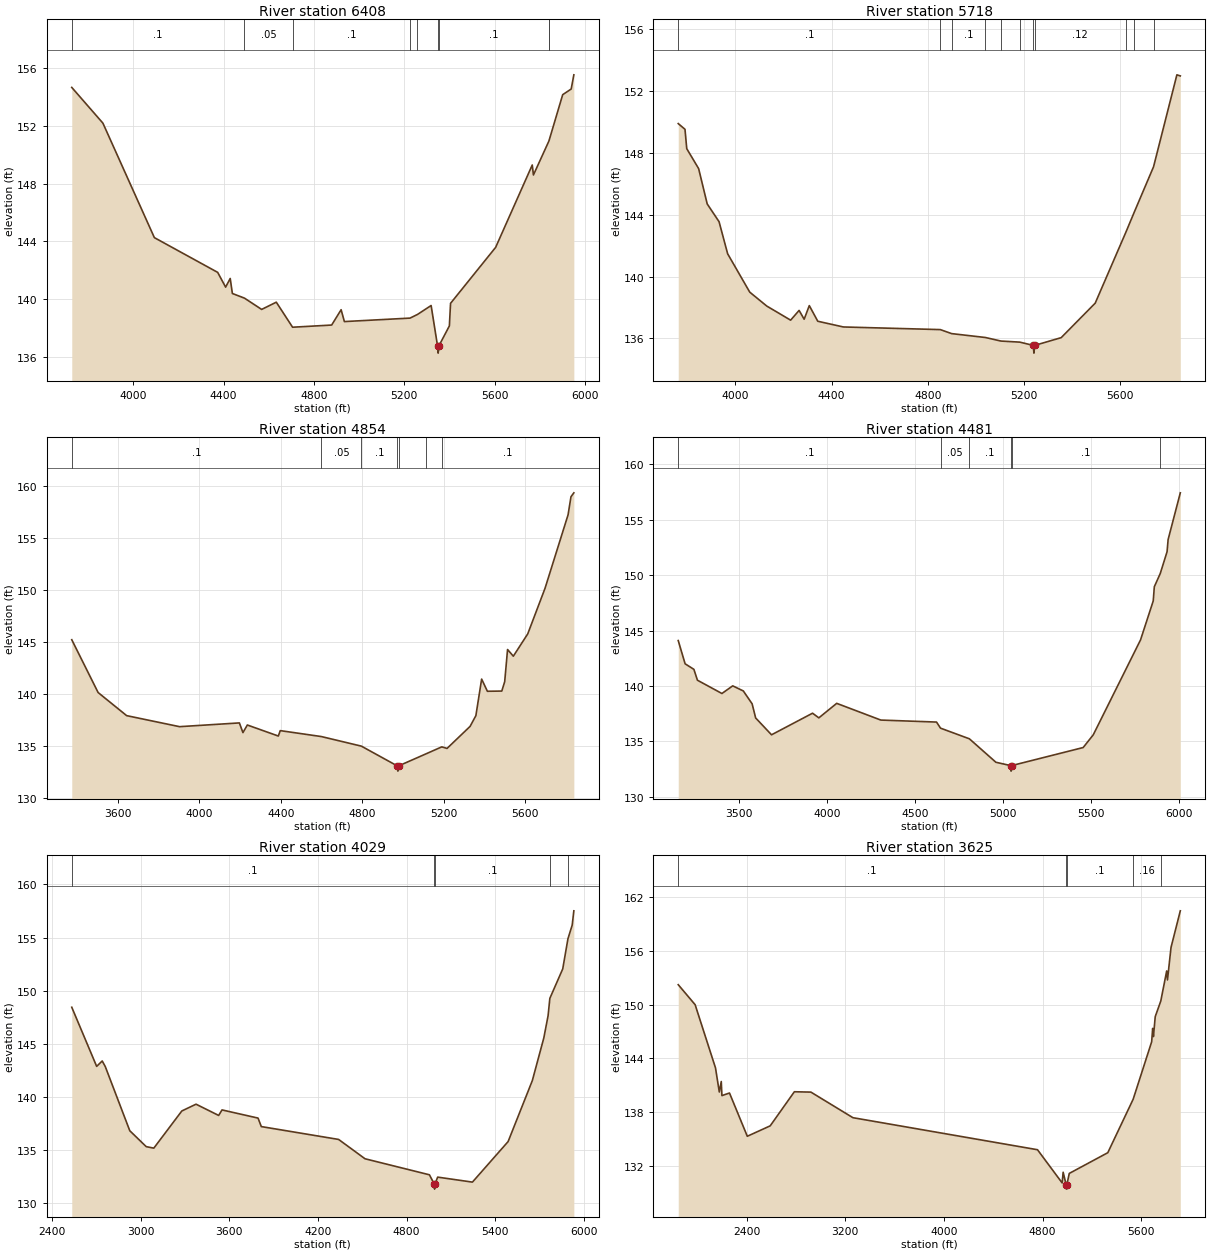
Type RM Length L Ch R = 1,6408,690,690,690
BEGIN DESCRIPTION:
UNT041 IN SPCR 13.0
END DESCRIPTION:
XS GIS Cut Line= 3
      2244299.97     13342736.26      2244561.19     13342085.28
      2245017.27     13340634.09
#Sta/Elev= 30
  3728.3  154.64  3866.2  152.17  4094.0  144.26  4374.2  141.86  4409.4  140.84
  4429.7  141.44  4439.3  140.40  4492.8  140.08  4568.9  139.30  4633.7  139.80
  4705.8  138.07  4878.8  138.22  4920.7  139.28  4935.1  138.46  5225.7  138.70
  5258.5  138.95  5319.1  139.57  5347.5  136.78  5350.3  136.28  5353.5  136.78
  5399.9  138.16  5405.1  139.72  5604.8  143.59  5766.8  149.28  5772.0  148.59
  5839.2  150.89  5841.2  150.97  5901.6  154.14  5939.2  154.53  5950.9  155.51
#Mann=9,-1,0
  3728.3     0.1       0  4492.8    0.05       0  4705.8     0.1       0
  5225.7    0.12       0  5258.5     0.1       0  5347.5    0.07       0
  5353.5     0.1       0  5839.2    0.16       0  5841.2     0.1       0
Bank Sta=5347.5,5353.5
Exp/Cntr=0.3,0.1

Type RM Length L Ch R = 1,5718,864,864,864
BEGIN DESCRIPTION:
UNT041 IN SPCR 12.0
END DESCRIPTION:
XS GIS Cut Line= 3
      2244437.72     13342696.86      2245337.72     13341846.85
      2245937.74     13341246.84
#Sta/Elev= 30
  3762.7  149.88  3790.8  149.51  3798.1  148.26  3847.5  146.97  3883.1  144.69
  3932.4  143.54  3968.0  141.47  4059.9  138.99  4130.7  138.09  4229.8  137.18
  4265.0  137.81  4286.0  137.24  4307.4  138.12  4342.6  137.11  4449.0  136.74
  4851.8  136.57  4899.1  136.31  5039.2  136.06  5103.6  135.83  5182.4  135.76
  5238.1  135.55  5240.8  135.05  5244.1  135.55  5354.2  136.05  5495.6  138.28
  5623.5  142.88  5657.9  144.16  5738.0  147.09  5835.0  153.03  5849.2  152.96
#Mann=11,-1,0
  3762.7     0.1       0  4851.8    0.05       0  4899.1     0.1       0
  5039.2    0.12       0  5103.6     0.1       0  5182.4    0.12       0
  5238.1    0.07       0  5244.1    0.12       0  5623.5     0.1       0
  5657.9    0.12       0  5738.0     0.1       0
Bank Sta=5238.1,5244.1
Exp/Cntr=0.3,0.1

Type RM Length L Ch R = 1,4854,373,373,373
BEGIN DESCRIPTION:
UNT041 IN SPCR 11.0
END DESCRIPTION:
XS GIS Cut Line= 3
      2244537.70     13342796.86      2246037.72     13342196.85
      2246637.72     13341596.86
#Sta/Elev= 30
  3374.2  145.21  3503.5  140.14  3643.5  137.92  3903.3  136.86  4196.8  137.22
  4214.3  136.29  4235.9  137.02  4388.0  135.96  4397.4  136.48  4599.2  135.91
  4795.5  134.99  4972.0  133.09  4974.7  132.59  4978.0  133.09  5112.8  134.25
  5190.1  134.92  5216.0  134.77  5329.2  136.89  5357.5  137.92  5385.8  141.43
  5414.0  140.26  5484.7  140.28  5498.9  141.18  5513.0  144.27  5541.3  143.63
  5612.0  145.77  5696.9  150.15  5810.0  157.21  5824.2  158.94  5838.3  159.32
#Mann=7,-1,0
  3374.2     0.1       0  4599.2    0.05       0  4795.5     0.1       0
  4972.0    0.07       0  4978.0     0.1       0  5112.8    0.12       0
  5190.1     0.1       0
Bank Sta=4972,4978
Exp/Cntr=0.3,0.1

Type RM Length L Ch R = 1,4481,452,452,452
BEGIN DESCRIPTION:
UNT041 IN SPCR 10.0
END DESCRIPTION:
XS GIS Cut Line= 4
      2244548.85     13343128.71      2245208.58     13343189.47
      2246441.22     13342347.46      2246822.96     13341757.49
#Sta/Elev= 30
  3152.3  144.10  3191.5  142.00  3241.5  141.50  3261.6  140.52  3400.9  139.32
  3462.5  140.01  3522.7  139.55  3572.9  138.39  3593.0  137.11  3683.4  135.59
  3916.8  137.54  3952.7  137.12  4054.4  138.43  4305.6  136.92  4622.6  136.74
  4645.4  136.19  4809.5  135.23  4960.6  133.11  5044.3  132.81  5047.0  132.31
  5050.3  132.81  5457.4  134.44  5514.8  135.59  5783.9  144.16  5856.2  147.68
  5862.4  148.96  5896.0  150.15  5934.9  152.12  5940.9  153.22  6010.3  157.44
#Mann=6,-1,0
  3152.3     0.1       0  4645.4    0.05       0  4809.5     0.1       0
  5044.3    0.07       0  5050.3     0.1       0  5896.0    0.16       0
Bank Sta=5044.3,5050.3
Exp/Cntr=0.3,0.1

Type RM Length L Ch R = 1,4029,404,404,404
BEGIN DESCRIPTION:
UNT041 IN SPCR 9.0
END DESCRIPTION:
XS GIS Cut Line= 4
      2244366.61     13343354.41      2245156.49     13343536.69
      2246432.53     13342842.25      2247143.55     13341957.82
#Sta/Elev= 30
  2533.2  148.44  2701.7  142.87  2739.3  143.38  2760.1  142.85  2925.8  136.81
  3037.2  135.31  3088.5  135.17  3278.1  138.67  3374.3  139.31  3527.4  138.25
  3550.2  138.77  3794.1  138.00  3816.0  137.20  4339.3  135.99  4517.9  134.17
  4953.8  132.66  4986.0  131.81  4988.8  131.31  4992.0  131.81  5009.8  132.44
  5245.0  131.97  5486.6  135.79  5650.4  141.53  5728.2  145.55  5757.0  147.64
  5769.1  149.28  5856.2  152.05  5891.5  154.89  5920.2  156.17  5931.4  157.52
#Mann=5,-1,0
  2533.2     0.1       0  4986.0    0.07       0  4992.0     0.1       0
  5769.1    0.16       0  5891.5     0.1       0
Bank Sta=4986,4992
Exp/Cntr=0.3,0.1

Type RM Length L Ch R = 1,3625,601,601,601
BEGIN DESCRIPTION:
UNT041 IN SPCR 8.0
END DESCRIPTION:
XS GIS Cut Line= 5
      2244114.80     13343475.92      2245278.02     13343771.07
      2246536.70     13343111.35      2246814.48     13342929.05
      2247508.94     13342052.29
#Sta/Elev= 30
  1845.6  152.22  1982.7  149.99  2147.8  142.95  2178.7  140.26  2194.6  141.43
  2199.8  139.86  2261.3  140.15  2405.7  135.33  2591.4  136.49  2787.4  140.29
  2921.6  140.25  3262.4  137.40  4759.3  133.83  4959.3  130.13  4967.3  131.32
  4991.5  129.94  4994.3  129.44  4997.5  129.94  5017.0  131.19  5329.5  133.50
  5535.2  139.46  5685.2  145.86  5693.3  147.35  5699.6  146.44  5714.1  148.66
  5759.2  150.40  5807.0  153.75  5813.4  152.75  5842.3  156.38  5917.5  160.45
#Mann=5,-1,0
  1845.6     0.1       0  4991.5    0.07       0  4997.5     0.1       0
  5535.2    0.16       0  5759.2     0.1       0
Bank Sta=4991.5,4997.5
Exp/Cntr=0.3,0.1

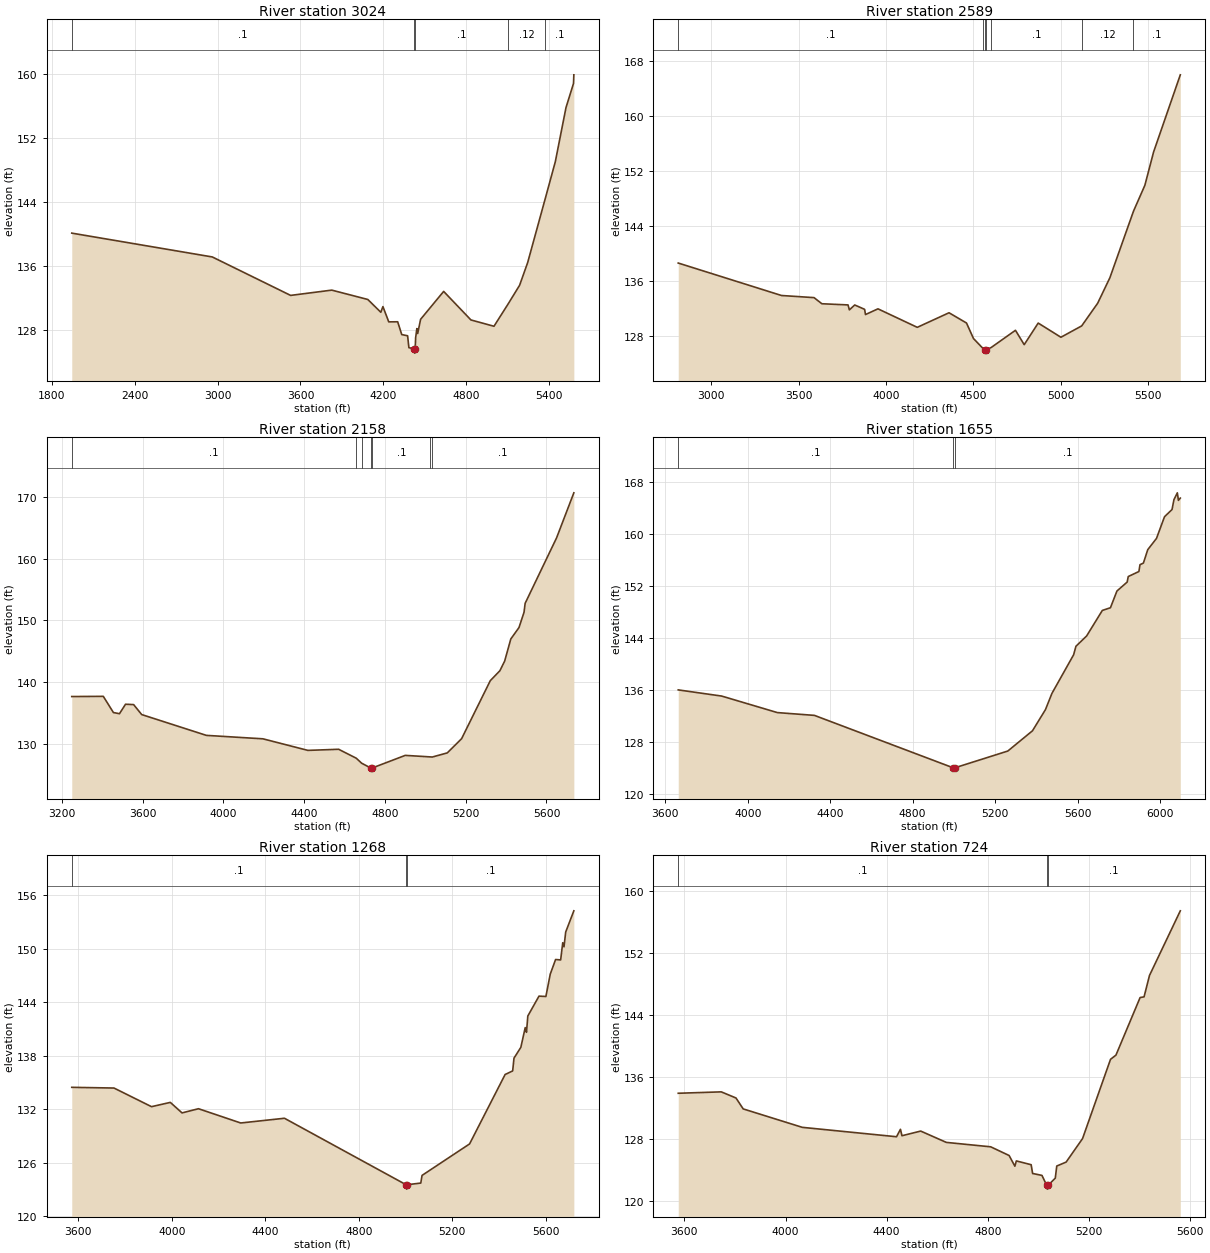
Type RM Length L Ch R = 1,3024,435,435,435
BEGIN DESCRIPTION:
Mapping XS b5af5421
END DESCRIPTION:
XS GIS Cut Line= 4
      2245643.01     13345097.43      2246863.76     13343682.73
      2247571.10     13342564.68      2247673.70     13342131.46
#Sta/Elev= 30
  1943.5  140.13  2961.3  137.15  3528.8  132.34  3826.9  133.00  4088.0  131.83
  4182.1  130.23  4197.4  130.94  4239.7  129.03  4304.2  129.04  4333.8  127.44
  4376.2  127.29  4385.5  125.81  4424.9  125.62  4427.7  125.12  4430.9  125.62
  4434.4  127.05  4443.2  128.19  4449.1  127.57  4470.3  129.35  4637.3  132.84
  4834.8  129.27  5001.8  128.48  5106.1  131.32  5187.5  133.61  5245.9  136.45
  5372.1  144.38  5446.1  149.06  5523.4  155.83  5578.0  158.86  5580.3  159.93
#Mann=5,-1,0
  1943.5     0.1       0  4424.9    0.07       0  4430.9     0.1       0
  5106.1    0.12       0  5372.1     0.1       0
Bank Sta=4424.9,4430.9
Exp/Cntr=0.3,0.1

Type RM Length L Ch R = 1,2589,431,431,431
BEGIN DESCRIPTION:
UNT041 IN SPCR 6.0
END DESCRIPTION:
XS GIS Cut Line= 3
      2247593.92     13344914.84      2247890.54     13343500.19
      2247890.54     13342074.10
#Sta/Elev= 30
  2811.7  138.64  3402.3  133.92  3588.4  133.61  3633.2  132.72  3782.9  132.55
  3790.5  131.83  3821.2  132.54  3877.6  131.91  3882.7  131.15  3954.0  131.98
  4178.8  129.29  4360.4  131.41  4460.4  129.92  4500.4  127.66  4557.3  126.15
  4567.4  126.04  4570.2  125.54  4573.4  126.04  4601.1  126.35  4740.4  128.86
  4790.4  126.77  4870.4  129.91  5000.4  127.85  5119.2  129.50  5210.4  132.79
  5280.4  136.50  5415.3  146.17  5480.4  149.94  5530.4  154.79  5683.2  166.01
#Mann=7,-1,0
  2811.7     0.1       0  4557.3    0.12       0  4567.4    0.07       0
  4573.4    0.12       0  4601.1     0.1       0  5119.2    0.12       0
  5415.3     0.1       0
Bank Sta=4567.4,4573.4
Exp/Cntr=0.3,0.1

Type RM Length L Ch R = 1,2158,503,503,503
BEGIN DESCRIPTION:
UNT041 IN SPCR 5.0
END DESCRIPTION:
XS GIS Cut Line= 4
      2248392.52     13344412.92      2248426.75     13343431.74
      2248209.99     13342176.78      2248084.51     13341982.86
#Sta/Elev= 30
  3249.3  137.64  3405.5  137.67  3455.5  135.04  3485.5  134.85  3515.5  136.39
  3555.6  136.33  3595.6  134.71  3915.8  131.33  4195.9  130.77  4418.7  128.89
  4570.9  129.07  4658.0  127.62  4684.7  126.81  4730.3  126.02  4733.0  125.52
  4736.3  126.02  4900.9  128.08  5025.5  127.83  5034.3  127.81  5108.8  128.48
  5179.8  130.79  5321.9  140.22  5369.3  141.83  5392.9  143.39  5423.4  146.99
  5464.0  148.85  5488.9  151.33  5494.4  152.78  5650.1  163.42  5735.6  170.74
#Mann=7,-1,0
  3249.3     0.1       0  4658.0    0.12       0  4684.7     0.1       0
  4730.3    0.07       0  4736.3     0.1       0  5025.5    0.12       0
  5034.3     0.1       0
Bank Sta=4730.3,4736.3
Exp/Cntr=0.3,0.1

Type RM Length L Ch R = 1,1655,387,387,387
BEGIN DESCRIPTION:
UNT041 IN SPCR 4.0
END DESCRIPTION:
XS GIS Cut Line= 4
      2248814.65     13344047.78      2248837.47     13343112.30
      2248460.98     13341948.61      2248198.54     13341857.32
#Sta/Elev= 30
  3662.2  136.04  3873.2  135.09  4143.3  132.55  4323.3  132.12  4997.5  124.05
  5000.3  123.55  5003.5  124.05  5261.8  126.64  5381.4  129.75  5444.5  133.01
  5476.0  135.51  5581.1  141.44  5592.4  142.75  5644.2  144.33  5720.5  148.26
  5759.8  148.67  5791.3  151.24  5841.0  152.62  5846.3  153.47  5897.9  154.24
  5903.2  155.29  5919.8  155.54  5940.9  157.60  5983.3  159.33  6022.3  162.67
  6058.7  163.77  6068.0  165.29  6084.5  166.34  6089.8  165.18  6098.9  165.53
#Mann=3,-1,0
  3662.2     0.1       0  4997.5    0.07       0  5003.5     0.1       0
Bank Sta=4997.5,5003.5
Exp/Cntr=0.3,0.1

Type RM Length L Ch R = 1,1268,544,544,544
BEGIN DESCRIPTION:
UNT041 IN SPCR 3.0
END DESCRIPTION:
XS GIS Cut Line= 3
      2249202.55     13343876.68      2249271.00     13343123.70
      2248746.19     13341834.51
#Sta/Elev= 30
  3572.4  134.46  3753.0  134.38  3913.6  132.29  3994.0  132.77  4044.2  131.59
  4114.5  132.06  4295.2  130.46  4482.3  130.99  5002.3  123.54  5005.0  123.04
  5008.3  123.54  5065.6  123.72  5071.0  124.58  5274.3  128.11  5426.4  135.90
  5458.7  136.30  5464.3  137.73  5493.7  138.95  5512.4  141.16  5517.8  140.63
  5523.5  142.46  5571.3  144.69  5600.8  144.65  5619.4  147.15  5642.3  148.80
  5663.9  148.75  5672.9  150.68  5678.3  150.22  5685.5  151.88  5720.4  154.26
#Mann=3,-1,0
  3572.4     0.1       0  5002.3    0.07       0  5008.3     0.1       0
Bank Sta=5002.3,5008.3
Exp/Cntr=0.3,0.1

Type RM Length L Ch R = 1,724,348,348,348
BEGIN DESCRIPTION:
Mapping XS 910244a0
END DESCRIPTION:
XS GIS Cut Line= 2
      2250504.28     13342782.43      2248794.83     13341771.51
#Sta/Elev= 30
  3575.6  133.87  3745.9  134.05  3804.0  133.26  3832.6  131.85  4066.6  129.47
  4439.1  128.26  4454.6  129.22  4460.6  128.39  4534.7  128.99  4636.1  127.53
  4811.6  126.96  4884.4  125.84  4907.2  124.46  4913.0  125.14  4971.6  124.65
  4977.4  123.52  5014.4  123.27  5032.9  122.00  5035.6  121.50  5038.9  122.00
  5067.1  122.92  5072.9  124.48  5110.0  124.99  5174.9  128.02  5285.6  138.25
  5307.0  138.79  5402.6  146.22  5418.2  146.31  5439.7  149.07  5561.6  157.41
#Mann=3,-1,0
  3575.6     0.1       0  5032.9    0.07       0  5038.9     0.1       0
Bank Sta=5032.9,5038.9
Exp/Cntr=0.3,0.1

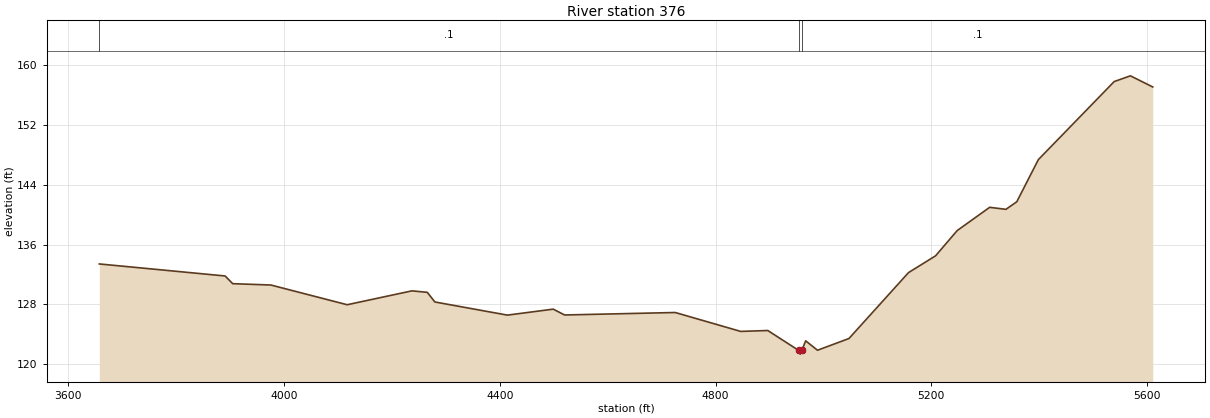
Type RM Length L Ch R = 1,376,0,0,0
BEGIN DESCRIPTION:
UNT041 IN SPCR 1.0
END DESCRIPTION:
XS GIS Cut Line= 3
      2250394.32     13342520.07      2249621.49     13341772.89
      2248746.48     13341699.98
#Sta/Elev= 30
  3657.5  133.42  3890.7  131.81  3904.8  130.78  3975.5  130.60  4117.0  127.96
  4237.2  129.82  4265.5  129.62  4279.6  128.33  4414.1  126.57  4499.0  127.37
  4520.1  126.59  4725.2  126.92  4846.6  124.39  4896.8  124.51  4954.0  121.85
  4956.8  121.35  4960.0  121.85  4967.0  123.13  4989.0  121.87  5047.3  123.44
  5157.7  132.26  5207.9  134.51  5248.0  137.89  5308.2  141.00  5338.3  140.73
  5358.4  141.74  5398.5  147.39  5539.0  157.83  5569.1  158.60  5610.5  157.11
#Mann=3,-1,0
  3657.5     0.1       0  4954.0    0.07       0  4960.0     0.1       0
Bank Sta=4954,4960
Exp/Cntr=0.3,0.1

Chan Stop Cuts=-1