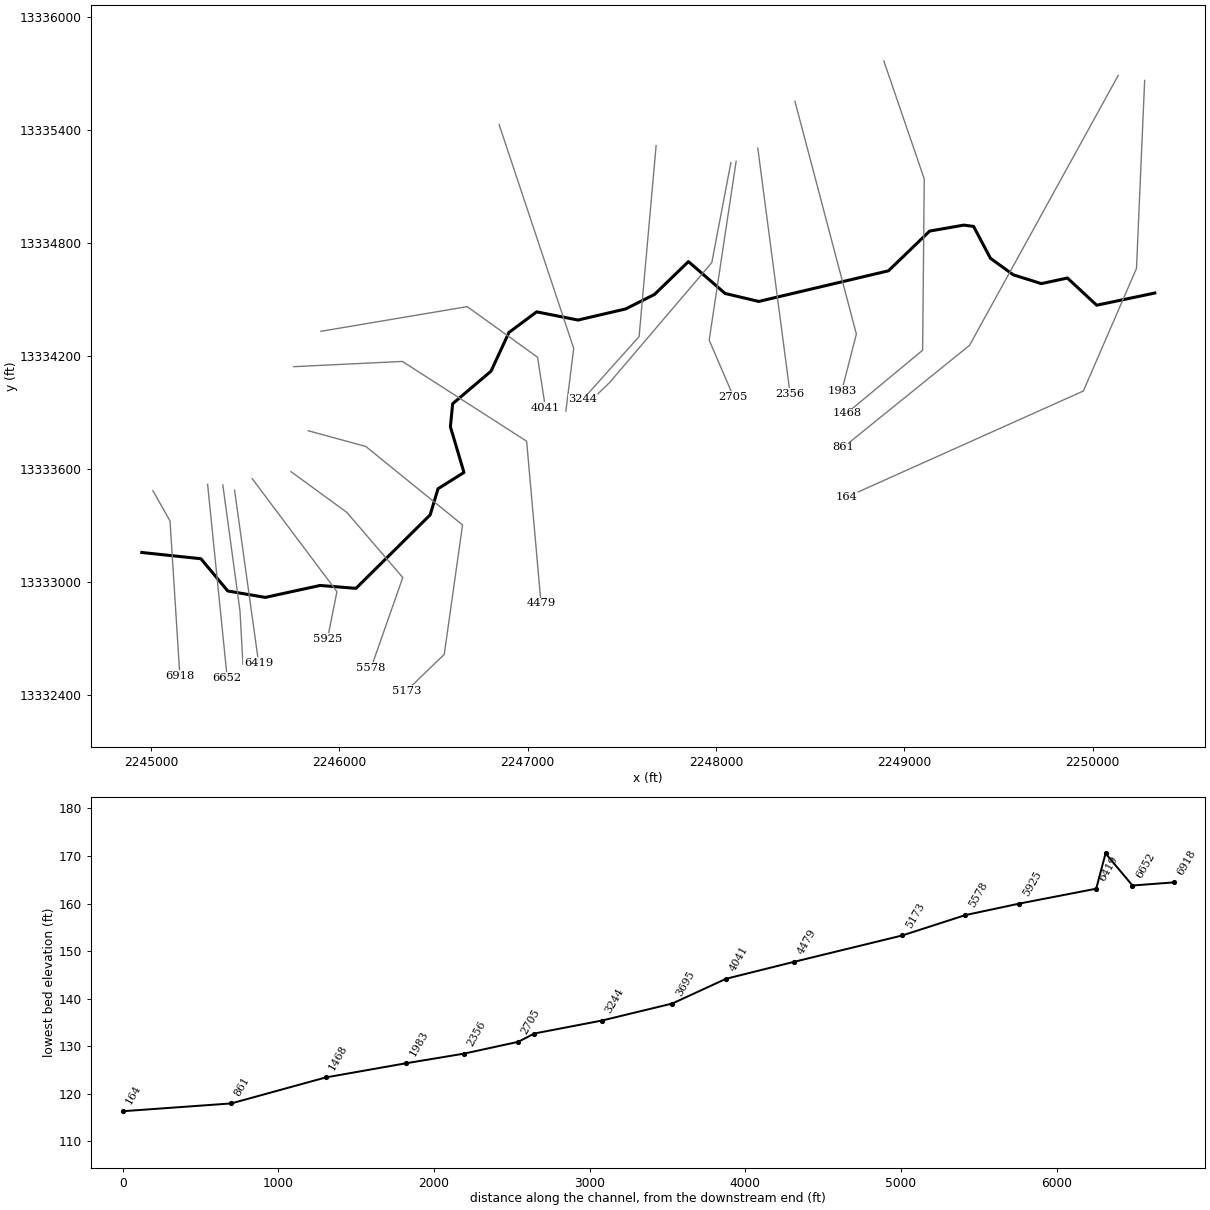
--- UNT042 IN SPCR.prj (project) ---

Proj Title=UNT042 IN SPCR Base Level Engineering
Current Plan=p01
Default Exp/Contr=0.3,0.1
English Units
Geom File=g01
Flow File=f01
Plan File=p01
Y Axis Title=Elevation
X Axis Title(PF)=Main Channel Distance
X Axis Title(XS)=Station
BEGIN DESCRIPTION:
UNT042 IN SPCR
END DESCRIPTION:
DSS Export Rating Curves= 0
DSS Export Rating Curve Sorted= 0
DSS Export Volume Flow Curves= 0
DXF OffsetX= 0
DXF OffsetY= 0
DXF ScaleX= 1
DXF ScaleY= 10

--- UNT042 IN SPCR.p01 (plan) ---

Plan Title=Multiple Run
Short Identifier=Multiple
Geom File=g01
Flow File=f01
Subcritical Flow
K Sum by GR= 0
Std Step Tol= 0.01
Critical Tol= 0.01
Num of Std Step Trials= 20
Max Error Tol= 0.3
Flow Tol Ratio= 0.001
Split Flow NTrial= 30
Split Flow Tol= 0.02
Split Flow Ratio= 0.02
Log Output Level= 0
Friction Slope Method= 1
Unsteady Friction Slope Method= 2
Unsteady Bridges Friction Slope Method= 1
Parabolic Critical Depth
Global Vel Dist=  1 , 1 , 1
Global Log Level= 0
CheckData=True
Encroach Param= -1, 0, 0, 0
BEGIN DESCRIPTION:
Multiple Run
END DESCRIPTION:

--- UNT042 IN SPCR.f01 (steady flow) ---

Flow Title=Multiple
Number of Profiles=7
Profile Names=10-year,25-year,50-year,1pct_min,100-year,1pct_plu,500-year
River Rch & RM= UNT042 IN SPCR,Reach-1,6918
     207     286     352     318     431     582     655
River Rch & RM= UNT042 IN SPCR,Reach-1,4041
     261     365     452     412     557     753     860
Boundary for River Rch & Prof#=UNT042 IN SPCR,Reach-1,1
Up Type=0
Dn Type=3
Dn Slope=0.005
Boundary for River Rch & Prof#=UNT042 IN SPCR,Reach-1,2
Up Type=0
Dn Type=3
Dn Slope=0.005
Boundary for River Rch & Prof#=UNT042 IN SPCR,Reach-1,3
Up Type=0
Dn Type=3
Dn Slope=0.005
Boundary for River Rch & Prof#=UNT042 IN SPCR,Reach-1,4
Up Type=0
Dn Type=3
Dn Slope=0.005
Boundary for River Rch & Prof#=UNT042 IN SPCR,Reach-1,5
Up Type=0
Dn Type=3
Dn Slope=0.005
Boundary for River Rch & Prof#=UNT042 IN SPCR,Reach-1,6
Up Type=0
Dn Type=3
Dn Slope=0.005
Boundary for River Rch & Prof#=UNT042 IN SPCR,Reach-1,7
Up Type=0
Dn Type=3
Dn Slope=0.005

--- UNT042 IN SPCR.g01 (geometry) ---

Geom Title=Existing Conditions
Program Version=4.10

River Reach=UNT042 IN SPCR  ,Reach-1
Reach XY= 30
       2244951.6     13333154.81      2245265.41     13333121.66
      2245407.98     13332950.36      2245607.28     13332916.33
      2245898.04     13332979.74      2246088.72     13332964.35
      2246482.76     13333354.46      2246524.44     13333493.31
      2246662.35     13333579.77      2246590.15     13333822.41
      2246602.18     13333944.74      2246805.83     13334117.41
      2246901.11     13334323.16      2247048.27     13334432.55
      2247267.74      13334389.1      2247520.67     13334448.03
      2247674.19     13334525.22      2247854.23     13334699.47
      2248049.04     13334530.09      2248227.73     13334487.89
      2248916.21      13334650.5       2249135.1     13334861.57
      2249316.91     13334893.23      2249368.38     13334886.28
      2249457.95     13334716.85       2249578.9     13334629.46
      2249727.67     13334582.55      2249866.69      13334612.2
      2250021.93     13334467.76      2250330.44     13334532.51

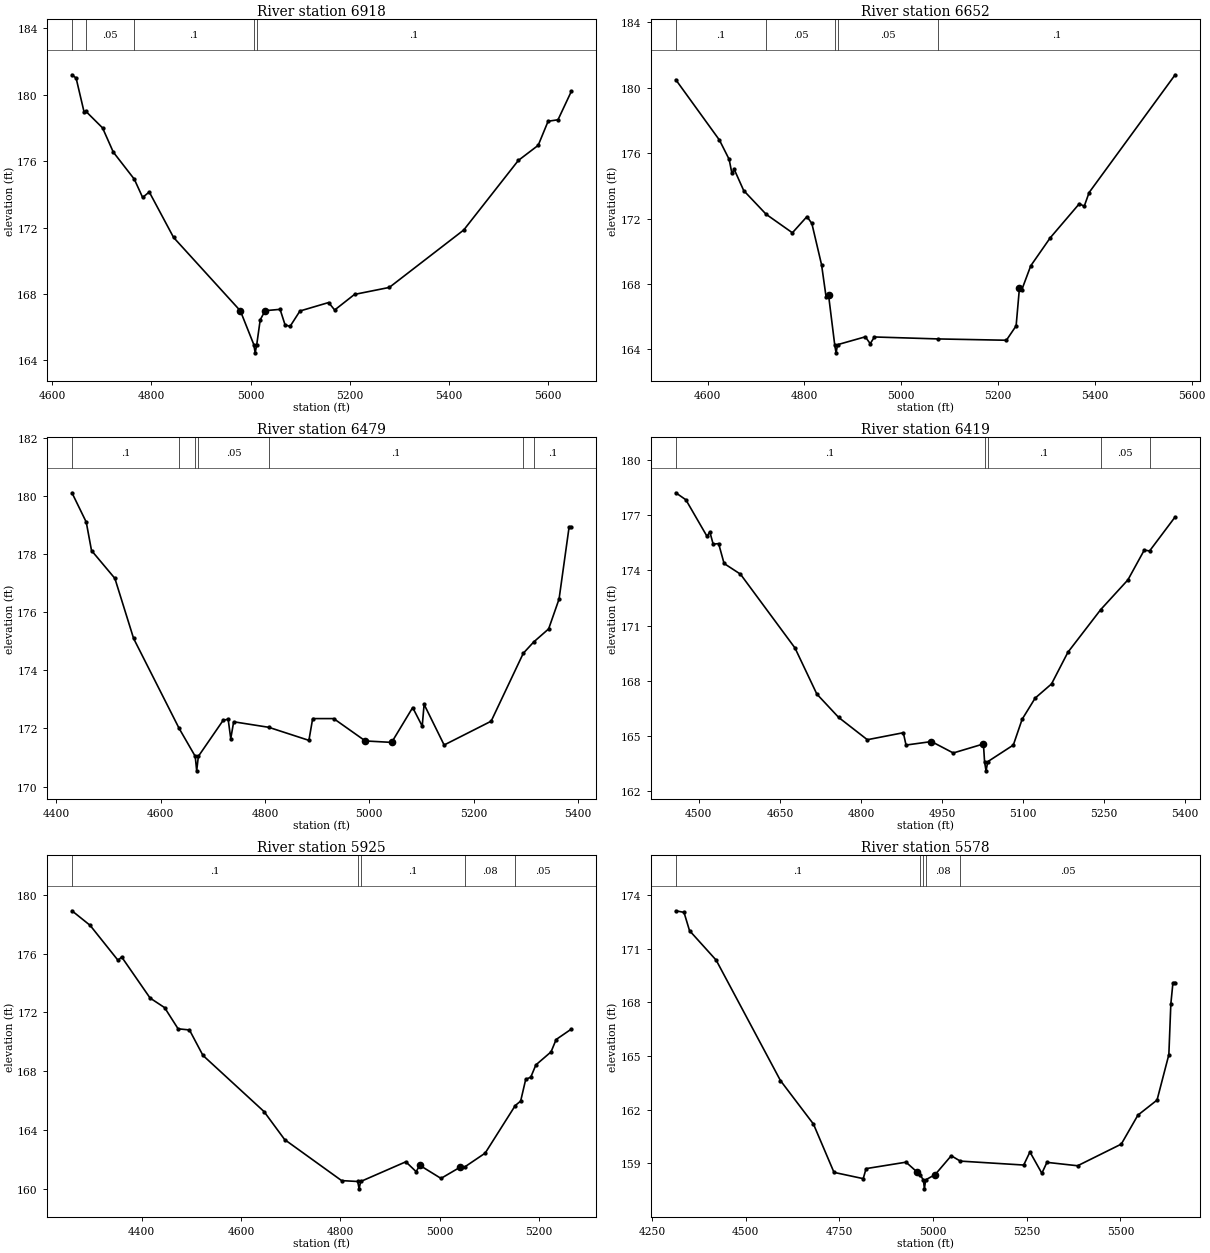
Type RM Length L Ch R = 1 ,6918    ,266,266,266
BEGIN DESCRIPTION:
UNT042 IN SPCR 12.0
END DESCRIPTION:
XS GIS Cut Line= 3
      2245010.61     13333482.71      2245101.37     13333322.14
      2245153.62     13332500.05
#Sta/Elev= 30
  4639.5   181.2  4647.9     181  4663.8  178.98  4667.9  178.99  4701.3     178
    4723  176.54  4765.4  174.91  4782.2  173.81  4795.6  174.14  4844.7   171.4
  4979.5  166.98  5006.6  164.95  5009.4  164.45  5012.6  164.95  5019.6  166.44
  5029.6  166.99  5059.7  167.07  5069.7  166.14  5079.8  166.04  5099.8  166.97
  5157.7  167.48  5169.9  167.03    5210  167.97  5280.2  168.39  5430.5  171.85
  5540.7  176.04  5580.8  176.95  5600.8   178.4  5620.8  178.49  5647.7   180.2
#Mann= 5 ,-1 , 0
  4639.5      .1       0  4667.9     .05       0  4765.4      .1       0
  5006.6     .07       0  5012.6      .1       0
Bank Sta=4979.5,5029.6
XS Rating Curve= 0 ,0
Exp/Cntr=0.3,0.1

Type RM Length L Ch R = 1 ,6652    ,173,173,173
BEGIN DESCRIPTION:
Mapping XS cdaec80a
END DESCRIPTION:
XS GIS Cut Line= 2
      2245300.98     13333516.58      2245404.95     13332489.93
#Sta/Elev= 30
    4534  180.49  4624.2   176.8  4644.3  175.62  4649.9  174.78  4654.9     175
  4674.4  173.71  4720.8  172.26    4775  171.13  4805.1  172.12  4815.2   171.7
  4835.3  169.17  4844.6  167.21  4849.7  167.32  4862.4  164.29  4865.2  163.79
  4868.4  164.29  4925.7  164.77  4935.8  164.35  4944.5  164.76  5076.6  164.64
  5217.2  164.56  5237.3  165.44  5244.2  167.77  5249.2  167.66  5267.5  169.11
  5307.7  170.82    5368  172.91    5378  172.75  5388.1  173.59  5565.9  180.79
#Mann= 5 ,-1 , 0
    4534      .1       0  4720.8     .05       0  4862.4    .033       0
  4868.4     .05       0  5076.6      .1       0
Bank Sta=4849.7,5244.2
XS Rating Curve= 0 ,0
Exp/Cntr=0.3,0.1

Type RM Length L Ch R = 1 ,6479    ,60,60,60
BEGIN DESCRIPTION:
Mapping XS f8279686
END DESCRIPTION:
XS GIS Cut Line= 3
      2245381.71     13333514.01      2245472.86     13332844.72
      2245488.48     13332563.42
#Sta/Elev= 30
    4430  180.12  4457.4  179.11  4467.5  178.13  4512.3  177.17  4548.2   175.1
  4635.5     172  4666.3  171.04  4669.1  170.54  4672.3  171.04  4719.8  172.28
  4729.4  172.32  4734.4  171.65    4740  172.23  4807.2  172.04  4884.2  171.59
  4891.4  172.34  4931.7  172.34  4992.3  171.57  5042.8  171.52  5083.1  172.72
  5101.4  172.08    5105  172.83  5143.4  171.43  5233.5  172.25  5295.1  174.59
  5315.1  174.98  5343.7  175.43  5363.7  176.46    5383  178.95  5387.2  178.95
#Mann= 7 ,-1 , 0
    4430      .1       0  4635.5     .05       0  4666.3     .07       0
  4672.3     .05       0  4807.2      .1       0  5295.1     .05       0
  5315.1      .1       0
Bank Sta=4992.3,5042.8
XS Rating Curve= 0 ,0
Exp/Cntr=0.3,0.1

Type RM Length L Ch R = 1 ,6419    ,494,494,494
BEGIN DESCRIPTION:
UNT042 IN SPCR 11.0
END DESCRIPTION:
XS GIS Cut Line= 2
       2245444.2     13333485.39      2245571.59     13332570.31
#Sta/Elev= 30
  4457.3  178.22    4476  177.84  4515.2  175.85  4520.3   176.1  4526.5  175.43
  4536.6  175.46  4546.7  174.38    4577   173.8  4677.9  169.79  4718.3  167.29
  4758.7  166.02  4811.7  164.81  4878.3  165.19  4883.3  164.52  4930.4  164.71
  4970.7  164.09  5026.5  164.58  5028.6  163.62  5031.3  163.12  5034.6  163.62
  5081.8  164.52  5098.1  165.92  5122.2  167.07  5152.5  167.84  5182.8  169.56
  5243.6  171.88  5293.8  173.49  5324.1  175.11  5333.9  175.06  5381.2  176.91
#Mann= 5 ,-1 , 0
  4457.3      .1       0  5028.6     .07       0  5034.6      .1       0
  5243.6     .05       0  5333.9      .1       0
Bank Sta=4930.4,5026.5
XS Rating Curve= 0 ,0
Exp/Cntr=0.3,0.1

Type RM Length L Ch R = 1 ,5925    ,347,347,347
BEGIN DESCRIPTION:
UNT042 IN SPCR 10.0
END DESCRIPTION:
XS GIS Cut Line= 3
      2245537.71     13333546.87      2245987.72     13332946.85
      2245937.72     13332696.83
#Sta/Elev= 30
    4260  178.91  4296.5  177.92  4352.7  175.54    4360  175.77  4417.3  172.97
  4446.5  172.32  4473.6  170.88  4496.5   170.8  4523.6  169.07  4646.5  165.25
  4688.1  163.34  4802.7  160.55  4835.1  160.49  4837.9  159.99  4841.1  160.49
  4931.9  161.83  4952.7  161.16    4960  161.59  5002.7   160.7  5040.6  161.45
  5050.9  161.49  5091.6  162.42  5152.2  165.66    5163  165.96  5173.2  167.44
  5183.4  167.59  5193.6  168.42  5224.2  169.31  5234.4  170.15    5265  170.86
#Mann= 5 ,-1 , 0
    4260      .1       0  4835.1     .07       0  4841.1      .1       0
  5050.9     .08       0  5152.2     .05       0
Bank Sta=4960,5040.6
XS Rating Curve= 0 ,0
Exp/Cntr=0.3,0.1

Type RM Length L Ch R = 1 ,5578    ,405,405,405
BEGIN DESCRIPTION:
UNT042 IN SPCR 9.0
END DESCRIPTION:
XS GIS Cut Line= 4
      2245743.77       13333584.      2246040.55     13333367.52
      2246337.32     13333021.88      2246168.79     13332541.29
#Sta/Elev= 30
  4313.7  173.11  4335.7  173.02  4350.4     172  4421.5  170.35    4593  163.62
    4681  161.19  4735.8  158.49  4813.8  158.14  4821.4   158.7  4927.9  159.06
  4956.4  158.53  4964.6  158.37  4974.3  158.07    4977  157.57  4980.3  158.07
  5005.8  158.37  5048.6  159.42  5072.7  159.12  5241.9   158.9  5258.5  159.63
  5290.3  158.44  5303.9  159.05  5385.7  158.86  5502.2  160.07  5546.6  161.69
  5597.6  162.53  5629.1  165.07  5634.4   167.9    5640  169.09  5645.9   169.1
#Mann= 5 ,-1 , 0
  4313.7      .1       0  4964.6     .08       0  4974.3     .07       0
  4980.3     .08       0  5072.7     .05       0
Bank Sta=4956.4,5005.8
XS Rating Curve= 0 ,0
Exp/Cntr=0.3,0.1

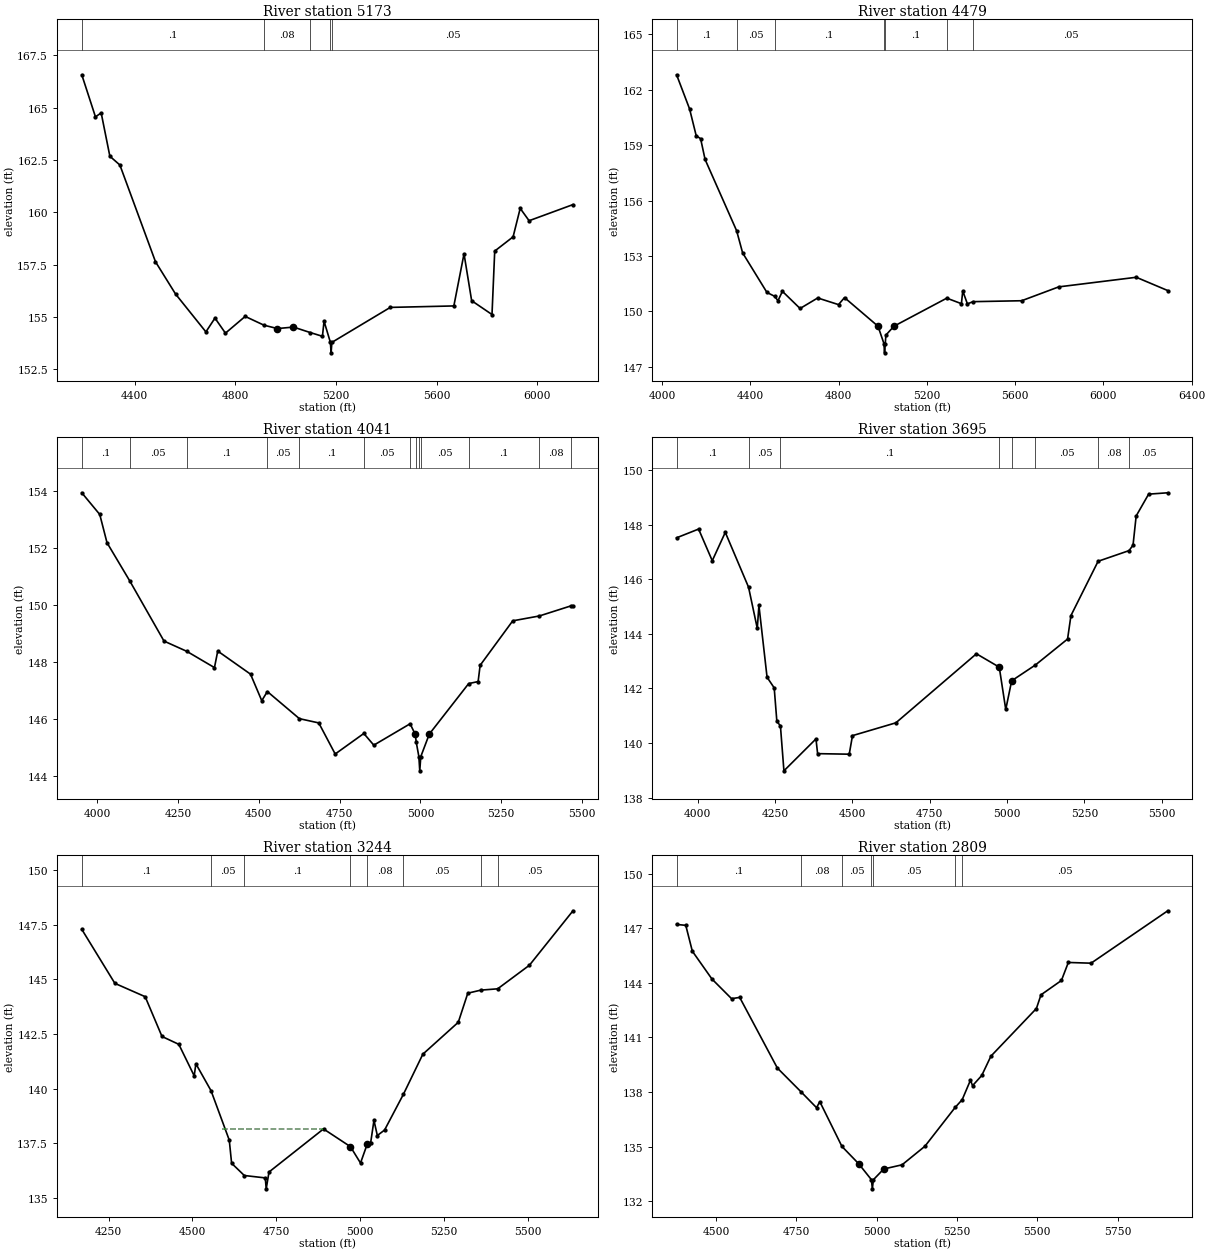
Type RM Length L Ch R = 1 ,5173    ,694,694,694
BEGIN DESCRIPTION:
Mapping XS 8bd6f4e4
END DESCRIPTION:
XS GIS Cut Line= 5
      2245835.31     13333801.25      2246140.87     13333717.92
      2246654.76     13333301.25      2246557.54     13332613.75
       2246357.5     13332420.61
#Sta/Elev= 30
  4190.6  166.57  4244.9  164.56  4267.6  164.75  4302.1  162.68  4341.9  162.26
  4483.3  157.64  4562.9   156.1  4683.5  154.29  4719.5  154.95  4761.1  154.23
  4839.5  155.03  4914.2  154.61  4967.3  154.45  5031.3  154.52  5097.6  154.26
  5146.3  154.08  5152.7   154.8  5177.9  153.79  5180.7  153.29  5183.9  153.79
  5415.7  155.46  5668.2  155.53  5708.6  158.02  5738.9  155.78  5819.7  155.12
  5830.5  158.15  5903.5  158.83  5931.7  160.19    5967   159.6  6141.3  160.37
#Mann= 5 ,-1 , 0
  4190.6      .1       0  4914.2     .08       0  5097.6     .05       0
  5177.9     .07       0  5183.9     .05       0
Bank Sta=4967.3,5031.3
XS Rating Curve= 0 ,0
Exp/Cntr=0.3,0.1

Type RM Length L Ch R = 1 ,4479    ,438,438,438
BEGIN DESCRIPTION:
Mapping XS a27d3c52
END DESCRIPTION:
XS GIS Cut Line= 4
       2245758.9     13334141.53      2246335.32     13334169.31
      2246995.04     13333745.69      2247071.43     13332884.58
#Sta/Elev= 30
  4065.9  162.81  4124.8  160.96  4154.8  159.51  4174.8  159.35  4194.9  158.23
  4337.9  154.37  4365.1  153.17  4475.2  151.03  4510.1  150.82  4525.3  150.58
  4545.3  151.09  4625.4  150.16  4705.3  150.73  4799.6  150.37  4826.7  150.75
  4978.6   149.2  5005.4  148.26  5008.1  147.76  5011.4  148.26  5014.3  148.72
  5050.6   149.2  5290.2  150.72  5356.5  150.42  5362.5  151.11  5383.6  150.41
  5409.2  150.53  5629.4  150.58  5797.3  151.33  6148.7  151.85  6291.5  151.13
#Mann= 7 ,-1 , 0
  4065.9      .1       0  4337.9     .05       0  4510.1      .1       0
  5005.4     .07       0  5011.4      .1       0  5290.2     .08       0
  5409.2     .05       0
Bank Sta=4978.6,5050.6
XS Rating Curve= 0 ,0
Exp/Cntr=0.3,0.1

Type RM Length L Ch R = 1 ,4041    ,346,346,346
BEGIN DESCRIPTION:
Mapping XS 84c6b28e
END DESCRIPTION:
XS GIS Cut Line= 4
      2245902.89     13334329.37      2246679.48     13334460.33
      2247053.06     13334191.49      2247094.95     13333922.64
#Sta/Elev= 30
  3952.1  153.94  4007.7  153.18  4030.1  152.19  4100.5  150.85  4206.5  148.74
  4277.1  148.38  4362.6  147.81  4372.8  148.39  4474.2  147.58    4509  146.65
  4526.3  146.97  4625.4  146.02  4685.4  145.87  4736.2  144.78  4824.8   145.5
  4855.7  145.09    4968  145.84  4983.9  145.47  4987.1  145.19  4995.1  144.69
  4997.9  144.19  5001.1  144.69  5027.5  145.48  5149.3  147.25  5178.5  147.32
  5184.7  147.89  5285.6  149.45  5367.8  149.62  5467.3  149.98    5472  149.98
#Mann= 13 ,-1 , 0
  3952.1      .1       0  4100.5     .05       0  4277.1      .1       0
  4526.3     .05       0  4625.4      .1       0  4824.8     .05       0
    4968      .1       0  4987.1     .05       0  4995.1     .04       0
  5001.1     .05       0  5149.3      .1       0  5367.8     .08       0
  5467.3     .05       0
Bank Sta=4983.9,5027.5
XS Rating Curve= 0 ,0
Exp/Cntr=0.3,0.1

Type RM Length L Ch R = 1 ,3695    ,451,451,451
BEGIN DESCRIPTION:
Mapping XS eeec7eaf
END DESCRIPTION:
XS GIS Cut Line= 3
      2246849.22     13335426.21      2247245.04     13334238.75
      2247203.37     13333905.43
#Sta/Elev= 30
  3932.1  147.52  4003.2  147.84  4047.4  146.68  4089.5  147.72  4164.7  145.71
  4192.9   144.2  4198.2  145.04  4224.5  142.41  4247.6  142.02  4256.2  140.79
  4267.7  140.63    4279  138.98  4382.6  140.15  4387.9  139.61  4490.1  139.59
  4500.6  140.27  4640.9  140.74  4901.2  143.27    4975  142.78    4996  141.23
  5015.1  142.28    5092  142.86  5195.8  143.81  5206.7  144.67  5294.5  146.66
  5394.4  147.05  5407.4  147.25  5417.5  148.32  5457.8  149.12  5519.7  149.17
#Mann= 8 ,-1 , 0
  3932.1      .1       0  4164.7     .05       0  4267.7      .1       0
    4975     .07       0  5015.1      .1       0    5092     .05       0
  5294.5     .08       0  5394.4     .05       0
#XS Ineff= 1 ,-1
    4160 4900.45143.2372
Permanent Ineff=
       F
Bank Sta=4975,5015.1
XS Rating Curve= 0 ,0
Exp/Cntr=0.3,0.1

Type RM Length L Ch R = 1 ,3244    ,435,435,435
BEGIN DESCRIPTION:
Mapping XS 604bdb94
END DESCRIPTION:
XS GIS Cut Line= 3
      2247682.54     13335315.17      2247592.26     13334301.25
      2247293.62     13333967.88
#Sta/Elev= 30
  4169.9  147.28  4268.6  144.81    4359   144.2  4409.2  142.38  4459.4  142.02
  4505.3  140.58  4510.3  141.13  4555.5   139.9  4609.9  137.64  4616.9  136.58
  4654.8  136.02  4717.4  135.91  4720.1  135.41  4728.5  136.18  4891.1  138.15
  4971.4  137.34  5001.5  136.59  5021.6  137.46  5031.6   137.5  5041.6  138.54
  5051.7  137.85  5073.3   138.1  5129.3  139.73  5187.5  141.57  5293.2  143.03
  5321.6  144.36  5360.4   144.5  5410.7  144.56  5505.5  145.64  5635.4  148.13
#Mann= 8 ,-1 , 0
  4169.9      .1       0  4555.5     .05       0  4654.8      .1       0
  4971.4     .07       0  5021.6     .08       0  5129.3     .05       0
  5360.4     .08       0  5410.7     .05       0
#XS Ineff= 1 ,-1
 4589.18 4890.21  138.14
Permanent Ineff=
       F
Bank Sta=4971.4,5021.6
XS Rating Curve= 0 ,0
Exp/Cntr=0.3,0.1

Type RM Length L Ch R = 1 ,2809    ,104,104,104
BEGIN DESCRIPTION:
Mapping XS 1d8f1521
END DESCRIPTION:
XS GIS Cut Line= 4
      2248079.53     13335224.98      2247978.27     13334694.25
      2247437.11     13334058.82      2247326.03     13333951.21
#Sta/Elev= 30
  4376.9  147.21  4405.5  147.16  4425.9  145.74    4487  144.21  4548.1  143.13
  4573.4   143.2  4690.6  139.32  4765.6  137.99  4812.7  137.14  4822.9  137.47
  4891.8  135.01  4943.9  134.06  4983.7  133.18  4986.5  132.68  4989.7  133.18
  5021.9  133.77    5079     134  5150.2  135.02  5244.2  137.15  5266.3  137.58
    5292  138.65  5298.6  138.35  5327.2  138.91  5355.7  139.97  5497.4  142.59
  5511.6  143.34  5575.3  144.13  5596.8  145.12  5667.6  145.08  5906.5  147.96
#Mann= 7 ,-1 , 0
  4376.9      .1       0  4765.6     .08       0  4891.8     .05       0
  4983.7     .03       0  4989.7     .05       0  5244.2      .1       0
  5266.3     .05       0
Bank Sta=4943.9,5021.9
XS Rating Curve= 0 ,0
Exp/Cntr=0.3,0.1

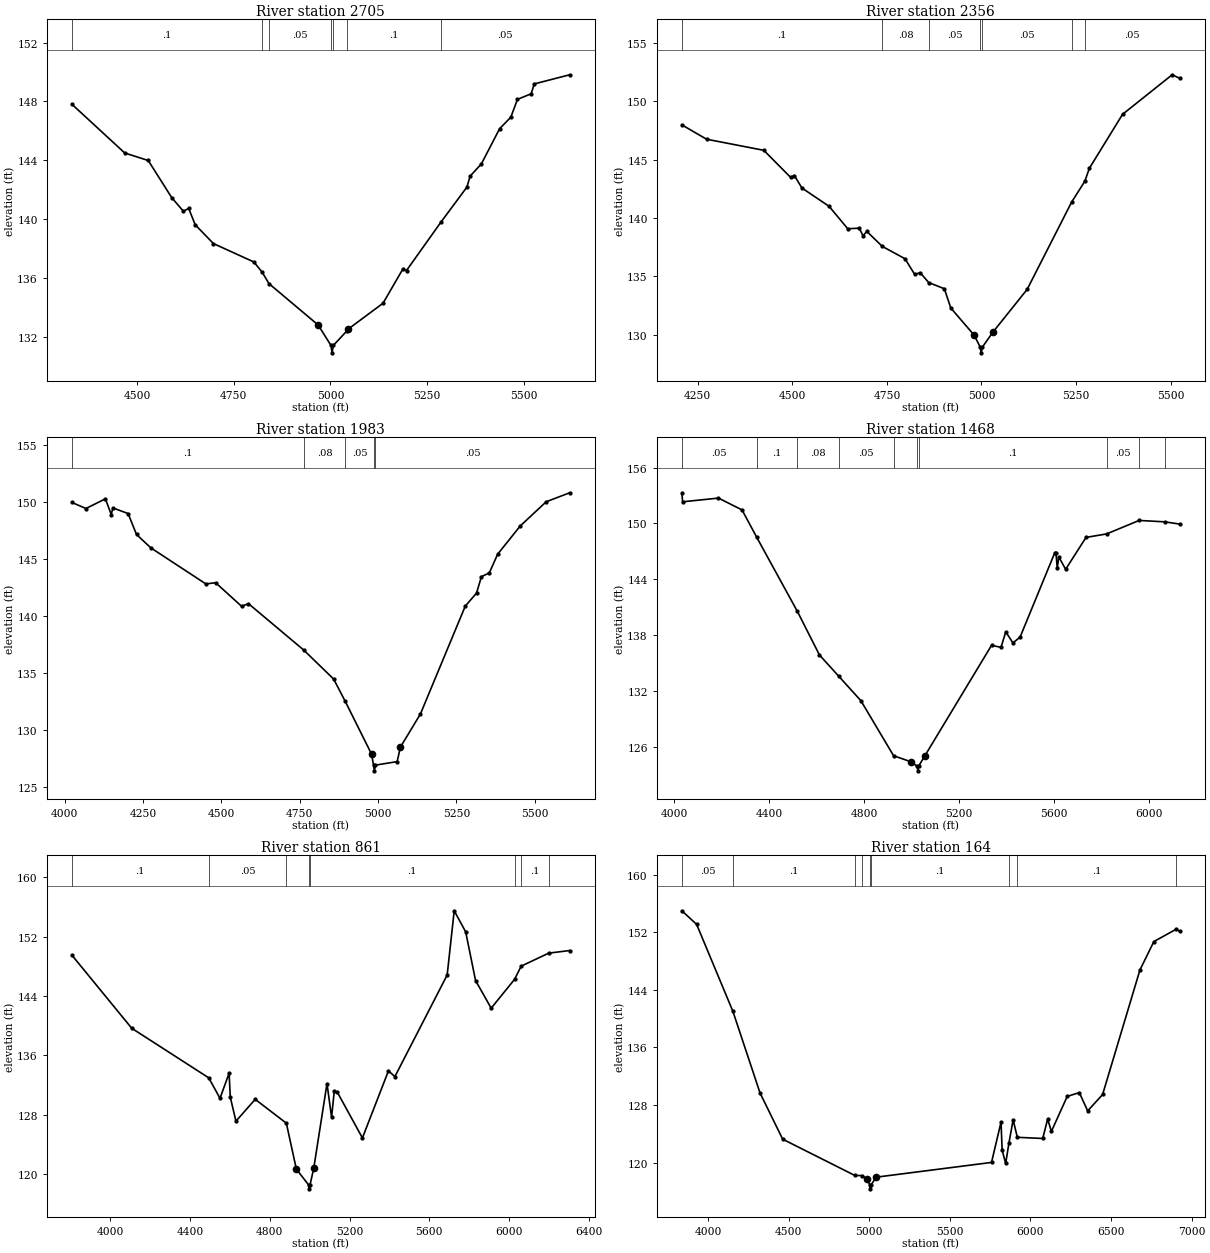
Type RM Length L Ch R = 1 ,2705    ,349,349,349
BEGIN DESCRIPTION:
Mapping XS 101119fd
END DESCRIPTION:
XS GIS Cut Line= 3
      2248107.46     13335231.94      2247964.31     13334282.27
       2248093.1      13333982.9
#Sta/Elev= 30
  4331.7  147.81  4468.3   144.5    4529  143.99  4589.7  141.47    4620  140.54
  4633.5  140.74  4650.3  139.63  4697.4  138.35    4802   137.1  4823.6   136.4
    4841  135.63  4968.1  132.82  5001.3  131.43    5004  130.93  5007.3  131.43
  5042.7  132.43  5044.7  132.52  5135.8   134.3  5186.3  136.59  5196.4  136.52
  5285.5  139.81  5352.4  142.18  5360.9  142.93  5389.9  143.76    5437  146.15
    5466  146.93  5483.1  148.14  5518.5  148.52  5526.6  149.19    5618  149.81
#Mann= 7 ,-1 , 0
  4331.7      .1       0  4823.6     .08       0    4841     .05       0
  5001.3     .03       0  5007.3     .05       0  5042.7      .1       0
  5285.5     .05       0
Bank Sta=4968.1,5044.7
XS Rating Curve= 0 ,0
Exp/Cntr=0.3,0.1

Type RM Length L Ch R = 1 ,2356    ,373,373,373
BEGIN DESCRIPTION:
UNT042 IN SPCR 5.0
END DESCRIPTION:
XS GIS Cut Line= 2
      2248222.48     13335301.49      2248394.11     13333997.13
#Sta/Elev= 30
  4208.2  147.97  4273.4  146.74  4424.7  145.79  4495.3  143.48  4505.4  143.63
  4525.5  142.56  4597.3  140.99  4646.6  139.07  4676.8  139.12  4686.9  138.47
    4697  138.84  4737.9  137.56  4797.9   136.5  4823.2  135.17  4838.2   135.3
  4860.5  134.46  4901.9  133.93  4918.9  132.28  4980.5  129.96  4996.6  128.94
  4999.3  128.44  5002.6  128.94  5029.9   130.2  5120.6  133.87  5238.2  141.35
  5273.3  143.15  5285.1  144.25  5372.8  148.87  5503.9  152.26  5523.8  151.96
#Mann= 7 ,-1 , 0
  4208.2      .1       0  4737.9     .08       0  4860.5     .05       0
  4996.6    .035       0  5002.6     .05       0  5238.2      .1       0
  5273.3     .05       0
Bank Sta=4980.5,5029.9
XS Rating Curve= 0 ,0
Exp/Cntr=0.3,0.1

Type RM Length L Ch R = 1 ,1983    ,515,515,515
BEGIN DESCRIPTION:
UNT042 IN SPCR 4.0
END DESCRIPTION:
XS GIS Cut Line= 3
      2248419.86     13335550.29      2248745.94     13334314.61
      2248668.71     13334014.26
#Sta/Elev= 30
  4023.2  149.97  4068.1  149.44  4130.2  150.29  4148.8  148.91    4154  149.49
  4202.6     149  4229.4  147.16    4275  145.99  4450.8  142.82  4481.8  142.93
  4564.6  140.86  4586.7  141.09  4763.3  137.01  4858.4  134.47  4895.5  132.51
  4979.2  127.89  4985.6  126.92  4988.3  126.42  4991.6  126.92    5061  127.23
  5071.3   128.5  5135.2  131.41  5278.2  140.87  5314.2  142.02  5329.8  143.46
    5355  143.79  5381.5  145.43  5453.7  147.91  5536.3  150.03  5611.3  150.82
#Mann= 5 ,-1 , 0
  4023.2      .1       0  4763.3     .08       0  4895.5     .05       0
  4985.6    .035       0  4991.6     .05       0
Bank Sta=4979.2,5071.3
XS Rating Curve= 0 ,0
Exp/Cntr=0.3,0.1

Type RM Length L Ch R = 1 ,1468    ,607,607,607
BEGIN DESCRIPTION:
UNT042 IN SPCR 3.0
END DESCRIPTION:
XS GIS Cut Line= 4
      2248891.83     13335764.85      2249106.36     13335138.42
      2249097.78      13334228.8      2248694.46     13333894.13
#Sta/Elev= 30
  4032.4  153.29  4035.4  152.32  4186.5  152.72  4285.7  151.45    4348  148.49
  4518.8  140.55  4611.6  135.88  4693.8  133.57  4786.1  130.97  4923.8  125.06
  4996.1  124.42  5023.1  123.94  5025.9  123.44  5029.1  123.94  5056.1  125.08
  5336.1  136.91  5376.1   136.7  5396.1  138.36  5426.1  137.18  5456.1  137.78
  5602.7  146.87  5607.5  146.87  5612.9  145.17  5619.4  146.41  5648.1  145.07
    5734   148.5  5820.3  148.87  5957.7  150.32  6065.6  150.17  6128.3  149.93
#Mann= 10 ,-1 , 0
  4032.4     .05       0    4348      .1       0  4518.8     .08       0
  4693.8     .05       0  4923.8      .1       0  5023.1     .07       0
  5029.1      .1       0  5820.3     .05       0  5957.7      .1       0
  6065.6     .05       0
Bank Sta=4996.1,5056.1
XS Rating Curve= 0 ,0
Exp/Cntr=0.3,0.1

Type RM Length L Ch R = 1 ,861     ,697,697,697
BEGIN DESCRIPTION:
UNT042 IN SPCR 2.0
END DESCRIPTION:
XS GIS Cut Line= 3
       2250136.1     13335687.58      2249346.64     13334254.54
      2248677.31     13333713.93
#Sta/Elev= 30
  3807.6  149.49  4107.9  139.63  4493.8  132.95  4550.5  130.19  4596.2  133.57
    4602  130.34  4630.5   127.1    4727  130.05  4883.3  126.83  4933.4  120.64
  4995.7  118.48  4998.5  117.98  5001.7  118.48  5020.5  120.73  5087.1  132.17
    5110  127.63  5123.7  131.16  5139.7  130.97  5264.7  124.84  5395.4  133.89
  5427.5  133.11  5689.8  146.81  5725.1  155.47  5782.6  152.63  5832.2  146.06
  5910.5  142.34  6027.6  146.22  6061.2  148.01  6199.3  149.76  6304.1  150.11
#Mann= 8 ,-1 , 0
  3807.6      .1       0  4493.8     .05       0  4883.3      .1       0
  4995.7     .07       0  5001.7      .1       0  6027.6     .05       0
  6061.2      .1       0  6199.3     .05       0
Bank Sta=4933.4,5020.5
XS Rating Curve= 0 ,0
Exp/Cntr=0.3,0.1

Type RM Length L Ch R = 1 ,164     ,0,0,0
BEGIN DESCRIPTION:
UNT042 IN SPCR 1.0
END DESCRIPTION:
XS GIS Cut Line= 4
      2250276.77     13335661.57      2250233.37     13334663.32
      2249951.25     13334012.28      2248692.66     13333448.08
#Sta/Elev= 30
  3837.9  154.98  3929.4  153.09  4154.5     141  4323.1  129.64  4463.2  123.24
  4910.8   118.2  4954.4  118.18    4985  117.75  5004.6  116.84  5007.4  116.34
  5010.6  116.84  5042.8  117.96  5758.7  120.01  5817.8  125.62  5824.5  121.73
  5846.5  119.87  5866.6  122.68  5892.8  125.93  5918.8   123.5  6076.5  123.34
  6106.9  126.04  6130.1  124.32  6228.3  129.18  6303.3  129.72  6355.2  127.17
  6447.9  129.45  6679.3  146.75  6765.7   150.7  6901.2  152.38  6925.9  152.17
#Mann= 9 ,-1 , 0
  3837.9     .05       0  4154.5      .1       0  4910.8     .07       0
  4954.4      .1       0  5004.6     .07       0  5010.6      .1       0
  5866.6     .16       0  5918.8      .1       0  6901.2     .05       0
Bank Sta=4985,5042.8
XS Rating Curve= 0 ,0
Exp/Cntr=0.3,0.1

Chan Stop Cuts=-1
Use User Specified Reach Order=0
Composite Channel Slope=5