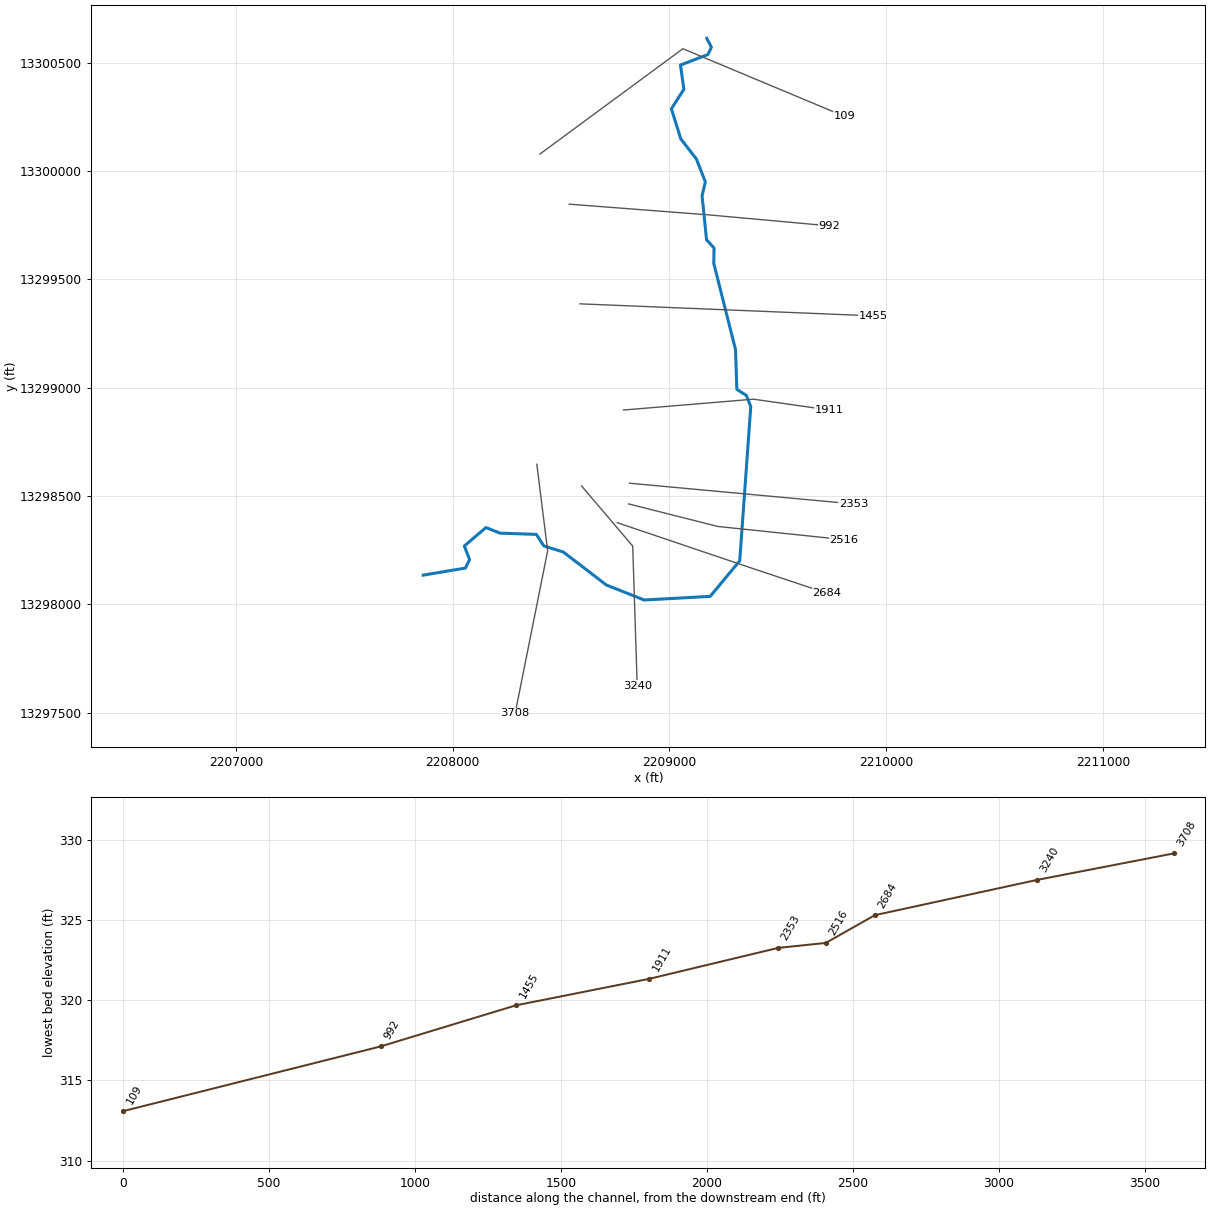
--- UNT043 IN SPCR.prj (project) ---

Proj Title=UNT043 IN SPCR Base Level Engineering
Current Plan=p01
Default Exp/Contr=0.3,0.1
English Units
Geom File=g01
Flow File=f01
Plan File=p01
BEGIN DESCRIPTION:
UNT043 IN SPCR
END DESCRIPTION:

--- UNT043 IN SPCR.p01 (plan) ---

Plan Title=Multiple Run
Short Identifier=Multiple
Geom File=g01
Flow File=f01
Subcritical Flow
K Sum by GR= 0
Std Step Tol= 0.01
Critical Tol= 0.01
Num of Std Step Trials= 20
Max Error Tol= 0.3
Flow Tol Ratio= 0.001
Split Flow NTrial= 30
Split Flow Tol= 0.02
Split Flow Ratio= 0.02
Log Output Level= 0
Friction Slope Method= 1
Unsteady Friction Slope Method= 2
Unsteady Bridges Friction Slope Method= 1
Parabolic Critical Depth
Global Vel Dist=  1 , 1 , 1
Global Log Level= 0
CheckData=True
Encroach Param= -1, 0, 0, 0
BEGIN DESCRIPTION:
Multiple Run
END DESCRIPTION:

--- UNT043 IN SPCR.f01 (steady flow) ---

Flow Title=Multiple
Number of Profiles=7
Profile Names=10-year,25-year,50-year,1pct_min,100-year,1pct_plu,500-year
River Rch & RM= UNT043 IN SPCR,Reach-1,3708
     209     289     355     321     434     587     658
Boundary for River Rch & Prof#=UNT043 IN SPCR,Reach-1,1
Up Type=0
Dn Type=3
Dn Slope=0.005
Boundary for River Rch & Prof#=UNT043 IN SPCR,Reach-1,2
Up Type=0
Dn Type=3
Dn Slope=0.005
Boundary for River Rch & Prof#=UNT043 IN SPCR,Reach-1,3
Up Type=0
Dn Type=3
Dn Slope=0.005
Boundary for River Rch & Prof#=UNT043 IN SPCR,Reach-1,4
Up Type=0
Dn Type=3
Dn Slope=0.005
Boundary for River Rch & Prof#=UNT043 IN SPCR,Reach-1,5
Up Type=0
Dn Type=3
Dn Slope=0.005
Boundary for River Rch & Prof#=UNT043 IN SPCR,Reach-1,6
Up Type=0
Dn Type=3
Dn Slope=0.005
Boundary for River Rch & Prof#=UNT043 IN SPCR,Reach-1,7
Up Type=0
Dn Type=3
Dn Slope=0.005

--- UNT043 IN SPCR.g01 (geometry) ---

Geom Title=Existing Conditions

River Reach=UNT043 IN SPCR,Reach-1
Reach XY= 30
      2207863.55     13298134.85      2208058.06     13298167.46
      2208077.38     13298206.49      2208053.33     13298269.43
      2208153.09     13298354.46      2208218.00     13298328.66
      2208385.57     13298322.87      2208419.69     13298269.87
      2208510.37     13298241.25      2208708.73     13298089.29
      2208883.38     13298020.04      2209187.72     13298036.85
      2209324.16     13298200.92      2209375.03     13298912.38
      2209355.09     13298963.91      2209310.77     13298992.28
      2209304.75     13299175.58      2209204.53     13299573.24
      2209205.64     13299644.73      2209170.99     13299682.55
      2209150.38     13299885.09      2209165.45     13299949.65
      2209124.20     13300055.23      2209052.22     13300148.12
      2209008.73     13300287.14      2209066.51     13300376.98
      2209050.74     13300488.88      2209177.56     13300537.49
      2209193.34     13300571.36      2209172.19     13300612.18

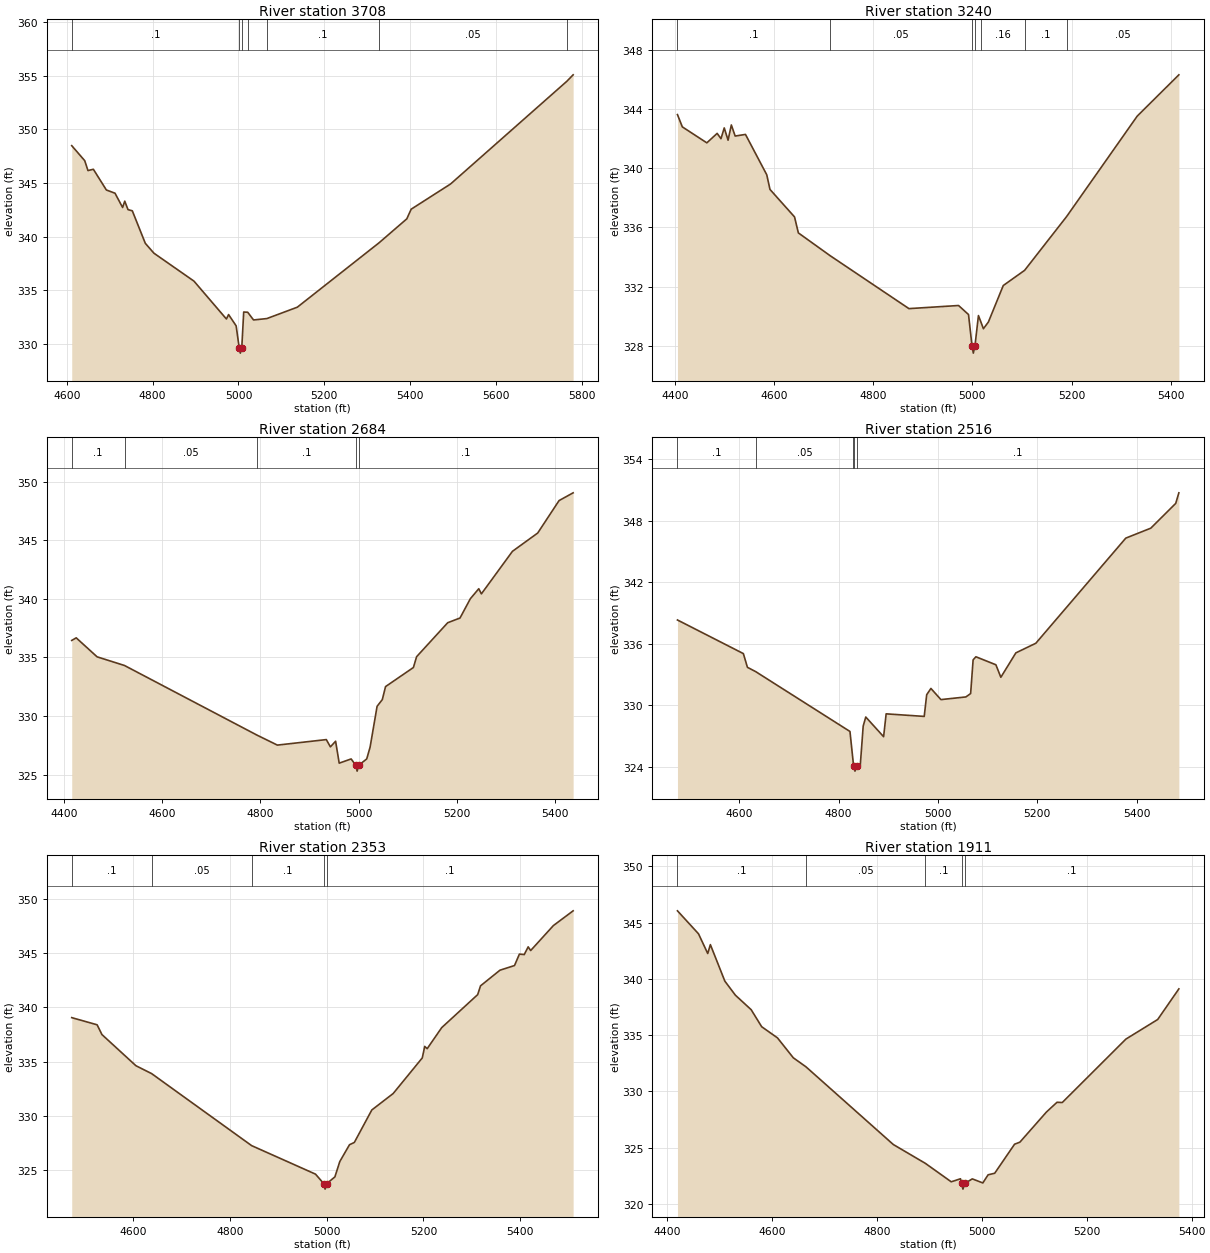
Type RM Length L Ch R = 1,3708,468,468,468
BEGIN DESCRIPTION:
UNT043 IN SPCR 7.0
END DESCRIPTION:
XS GIS Cut Line= 3
      2208387.72     13298646.89      2208437.72     13298246.85
      2208287.72     13297496.86
#Sta/Elev= 30
  4611.6  348.48  4641.9  347.08  4649.4  346.16  4662.0  346.28  4692.3  344.35
  4712.4  344.05  4730.1  342.72  4735.1  343.31  4742.7  342.52  4752.7  342.41
  4783.0  339.38  4803.1  338.46  4896.3  335.86  4971.9  332.33  4977.0  332.74
  4994.6  331.69  5001.7  329.65  5004.4  329.15  5007.7  329.65  5012.2  332.98
  5021.5  332.96  5035.1  332.24  5066.2  332.37  5137.1  333.43  5327.5  339.43
  5392.1  341.66  5402.3  342.56  5494.1  344.91  5764.7  354.47  5779.6  355.08
#Mann=7,-1,0
  4611.6     0.1       0  5001.7    0.07       0  5007.7     0.1       0
  5021.5    0.16       0  5066.2     0.1       0  5327.5    0.05       0
  5764.7    0.08       0
Bank Sta=5001.7,5007.7
Exp/Cntr=0.3,0.1

Type RM Length L Ch R = 1,3240,556,556,556
BEGIN DESCRIPTION:
Mapping XS f748f546
END DESCRIPTION:
XS GIS Cut Line= 3
      2208594.13     13298546.61      2208830.23     13298268.84
      2208851.06     13297623.03
#Sta/Elev= 30
  4405.6  343.63  4415.4  342.80  4464.8  341.72  4485.6  342.36  4493.3  342.00
  4499.9  342.73  4507.6  341.90  4514.2  342.93  4521.9  342.18  4542.7  342.29
  4585.6  339.56  4592.1  338.57  4641.6  336.71  4649.3  335.63  4713.3  334.09
  4872.2  330.51  4972.2  330.72  4992.3  330.11  4999.3  328.00  5002.0  327.50
  5005.3  328.00  5012.3  330.04  5017.3  329.60  5022.3  329.15  5032.3  329.60
  5062.3  332.07  5105.4  333.10  5189.9  336.73  5332.4  343.53  5416.3  346.32
#Mann=7,-1,0
  4405.6     0.1       0  4713.3    0.05       0  4999.3   0.035       0
  5005.3    0.05       0  5017.3    0.16       0  5105.4     0.1       0
  5189.9    0.05       0
Bank Sta=4999.3,5005.3
Exp/Cntr=0.3,0.1

Type RM Length L Ch R = 1,2684,168,168,168
BEGIN DESCRIPTION:
Mapping XS 87268127
END DESCRIPTION:
XS GIS Cut Line= 3
      2208759.11     13298376.78      2209375.42     13298168.45
      2209726.09     13298051.56
#Sta/Elev= 30
  4416.2  336.45  4425.3  336.67  4467.8  335.05  4523.6  334.31  4793.7  328.36
  4834.6  327.52  4934.2  327.99  4942.5  327.37  4953.1  327.85  4960.4  325.98
  4984.7  326.34  4994.1  325.80  4996.9  325.30  5000.1  325.80  5016.4  326.34
  5023.3  327.35  5037.5  330.83  5048.1  331.40  5054.7  332.51  5111.4  334.14
  5117.9  335.06  5181.2  337.96  5206.2  338.36  5227.3  340.01  5244.4  340.86
  5249.7  340.42  5312.9  344.05  5364.3  345.61  5407.8  348.38  5436.4  349.04
#Mann=5,-1,0
  4416.2     0.1       0  4523.6    0.05       0  4793.7     0.1       0
  4994.1    0.07       0  5000.1     0.1       0
Bank Sta=4994.1,5000.1
Exp/Cntr=0.3,0.1

Type RM Length L Ch R = 1,2516,163,163,163
BEGIN DESCRIPTION:
Mapping XS fce4ec61
END DESCRIPTION:
XS GIS Cut Line= 3
      2208811.17     13298463.60      2209223.51     13298359.42
      2209803.95     13298298.78
#Sta/Elev= 30
  4475.9  338.32  4608.5  335.04  4616.7  333.70  4633.3  333.28  4823.0  327.44
  4829.2  324.58  4830.3  324.07  4833.1  323.57  4836.3  324.07  4843.7  324.11
  4849.6  327.96  4854.8  328.85  4890.7  326.93  4895.8  329.16  4972.4  328.91
  4977.4  331.03  4985.9  331.64  5006.0  330.55  5056.2  330.81  5065.8  331.14
  5070.8  334.43  5076.4  334.73  5116.6  333.95  5126.6  332.73  5156.8  335.11
  5197.0  336.05  5378.0  346.31  5428.3  347.28  5478.5  349.70  5484.8  350.73
#Mann=5,-1,0
  4475.9     0.1       0  4633.3    0.05       0  4829.2     0.1       0
  4830.3    0.07       0  4836.3     0.1       0
Bank Sta=4830.3,4836.3
Exp/Cntr=0.3,0.1

Type RM Length L Ch R = 1,2353,442,442,442
BEGIN DESCRIPTION:
Mapping XS 83ed2efc
END DESCRIPTION:
XS GIS Cut Line= 2
      2208815.49     13298559.08      2209848.48     13298463.59
#Sta/Elev= 30
  4472.3  339.06  4524.8  338.40  4534.8  337.50  4605.1  334.63  4637.7  333.90
  4844.4  327.27  4976.7  324.64  4993.8  323.76  4996.5  323.26  4999.8  323.76
  5016.8  324.39  5026.9  325.80  5047.0  327.35  5057.0  327.56  5093.1  330.55
  5137.4  332.07  5197.6  335.35  5202.6  336.41  5207.7  336.20  5237.8  338.14
  5312.2  341.18  5318.1  341.99  5358.3  343.43  5388.4  343.86  5398.5  344.91
  5408.5  344.87  5416.7  345.58  5421.8  345.24  5468.8  347.54  5509.7  348.90
#Mann=5,-1,0
  4472.3     0.1       0  4637.7    0.05       0  4844.4     0.1       0
  4993.8    0.07       0  4999.8     0.1       0
Bank Sta=4993.8,4999.8
Exp/Cntr=0.3,0.1

Type RM Length L Ch R = 1,1911,456,456,456
BEGIN DESCRIPTION:
UNT043 IN SPCR 4.0
END DESCRIPTION:
XS GIS Cut Line= 3
      2208787.73     13298896.86      2209387.72     13298946.85
      2209737.70     13298896.86
#Sta/Elev= 30
  4420.1  346.04  4460.2  344.00  4477.8  342.25  4482.8  343.04  4510.4  339.80
  4530.5  338.55  4560.6  337.26  4580.6  335.75  4610.7  334.76  4640.9  332.99
  4665.0  332.19  4831.5  325.29  4892.5  323.62  4941.9  321.98  4959.5  322.25
  4961.5  321.83  4964.2  321.33  4967.5  321.83  4982.0  322.24  5002.1  321.88
  5012.1  322.60  5024.7  322.74  5062.6  325.32  5072.7  325.50  5123.2  328.17
  5143.4  329.04  5153.5  329.02  5274.7  334.65  5335.3  336.39  5375.7  339.11
#Mann=5,-1,0
  4420.1     0.1       0  4665.0    0.05       0  4892.5     0.1       0
  4961.5    0.07       0  4967.5     0.1       0
Bank Sta=4961.5,4967.5
Exp/Cntr=0.3,0.1

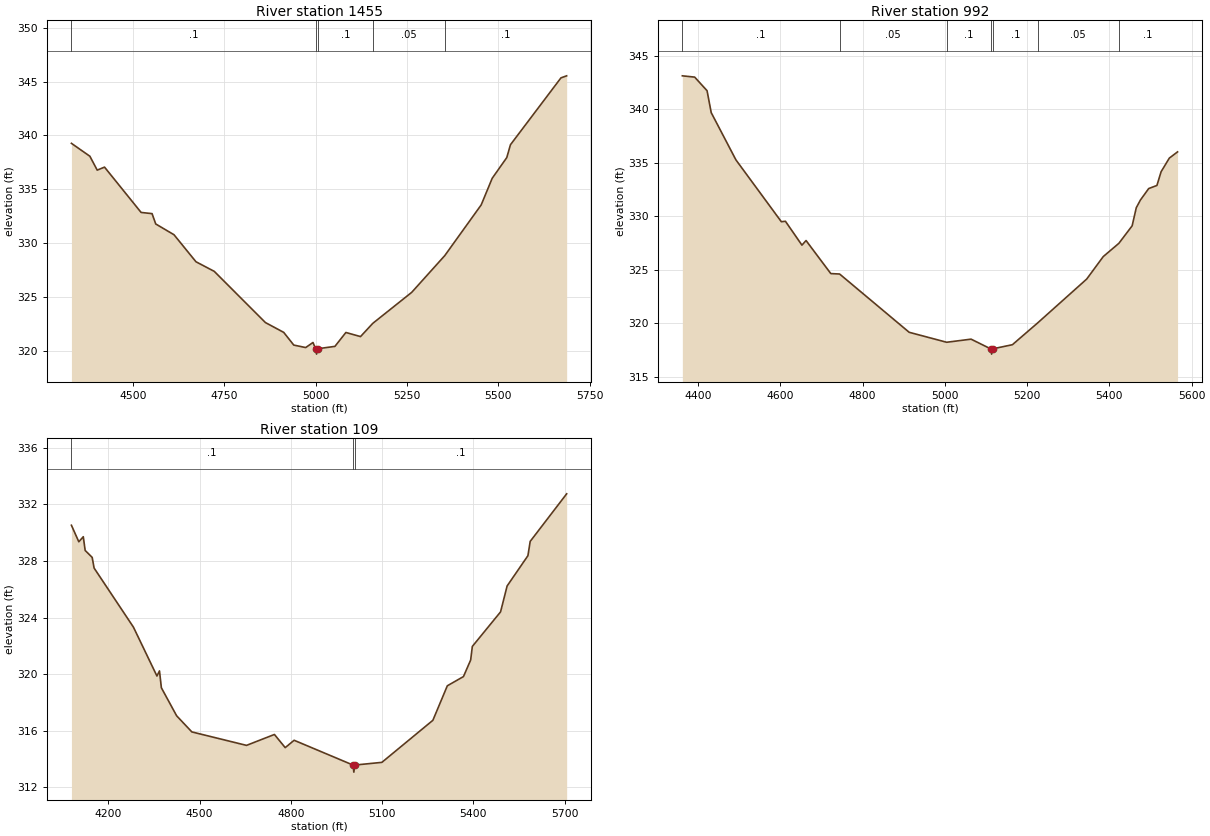
Type RM Length L Ch R = 1,1455,463,463,463
BEGIN DESCRIPTION:
UNT043 IN SPCR 3.0
END DESCRIPTION:
XS GIS Cut Line= 2
      2208587.21     13299386.90      2209941.38     13299331.34
#Sta/Elev= 30
  4331.8  339.26  4382.3  338.06  4402.4  336.77  4422.4  337.05  4522.5  332.84
  4552.5  332.73  4562.5  331.77  4612.5  330.77  4672.6  328.26  4722.6  327.37
  4862.8  322.61  4912.8  321.70  4940.3  320.52  4972.8  320.29  4992.9  320.76
  4999.9  320.18  5002.6  319.68  5005.9  320.18  5052.9  320.40  5082.9  321.69
  5123.0  321.31  5156.6  322.54  5263.1  325.42  5353.5  328.83  5453.2  333.54
  5483.3  336.01  5523.3  337.94  5533.3  339.13  5671.5  345.34  5687.1  345.53
#Mann=5,-1,0
  4331.8     0.1       0  4999.9    0.07       0  5005.9     0.1       0
  5156.6    0.05       0  5353.5     0.1       0
Bank Sta=4999.9,5005.9
Exp/Cntr=0.3,0.1

Type RM Length L Ch R = 1,992,883,883,883
BEGIN DESCRIPTION:
UNT043 IN SPCR 2.0
END DESCRIPTION:
XS GIS Cut Line= 3
      2208537.76     13299846.85      2209187.72     13299796.85
      2209737.68     13299746.86
#Sta/Elev= 30
  4361.7  343.14  4391.7  343.02  4421.8  341.75  4431.9  339.70  4492.0  335.28
  4602.4  329.50  4612.4  329.54  4652.5  327.31  4662.5  327.74  4722.7  324.65
  4744.1  324.61  4913.3  319.16  5004.4  318.23  5063.8  318.52  5111.0  317.62
  5113.7  317.12  5117.0  317.62  5164.2  318.00  5225.4  320.03  5344.9  324.14
  5385.1  326.24  5423.1  327.48  5455.4  329.12  5465.4  330.81  5475.5  331.53
  5495.6  332.60  5515.6  332.89  5525.7  334.17  5545.8  335.45  5565.8  336.03
#Mann=7,-1,0
  4361.7     0.1       0  4744.1    0.05       0  5004.4     0.1       0
  5111.0    0.03       0  5117.0     0.1       0  5225.4    0.05       0
  5423.1     0.1       0
Bank Sta=5111,5117
Exp/Cntr=0.3,0.1

Type RM Length L Ch R = 1,109,0,0,0
BEGIN DESCRIPTION:
UNT043 IN SPCR 1.0
END DESCRIPTION:
XS GIS Cut Line= 3
      2208402.11     13300078.17      2209061.84     13300564.28
      2209808.30     13300251.81
#Sta/Elev= 30
  4078.2  330.52  4102.5  329.35  4117.2  329.71  4123.4  328.74  4146.5  328.25
  4152.7  327.50  4282.2  323.32  4359.4  319.87  4367.8  320.23  4374.0  319.04
  4424.2  317.06  4474.3  315.92  4654.0  314.97  4745.8  315.74  4781.3  314.81
  4810.6  315.33  5004.3  313.58  5007.0  313.08  5010.3  313.58  5099.2  313.77
  5266.9  316.74  5314.5  319.18  5367.5  319.83  5391.2  321.00  5396.7  321.96
  5489.5  324.40  5511.1  326.23  5579.5  328.37  5587.0  329.38  5706.9  332.74
#Mann=3,-1,0
  4078.2     0.1       0  5004.3    0.07       0  5010.3     0.1       0
Bank Sta=5004.3,5010.3
Exp/Cntr=0.3,0.1

Chan Stop Cuts=-1