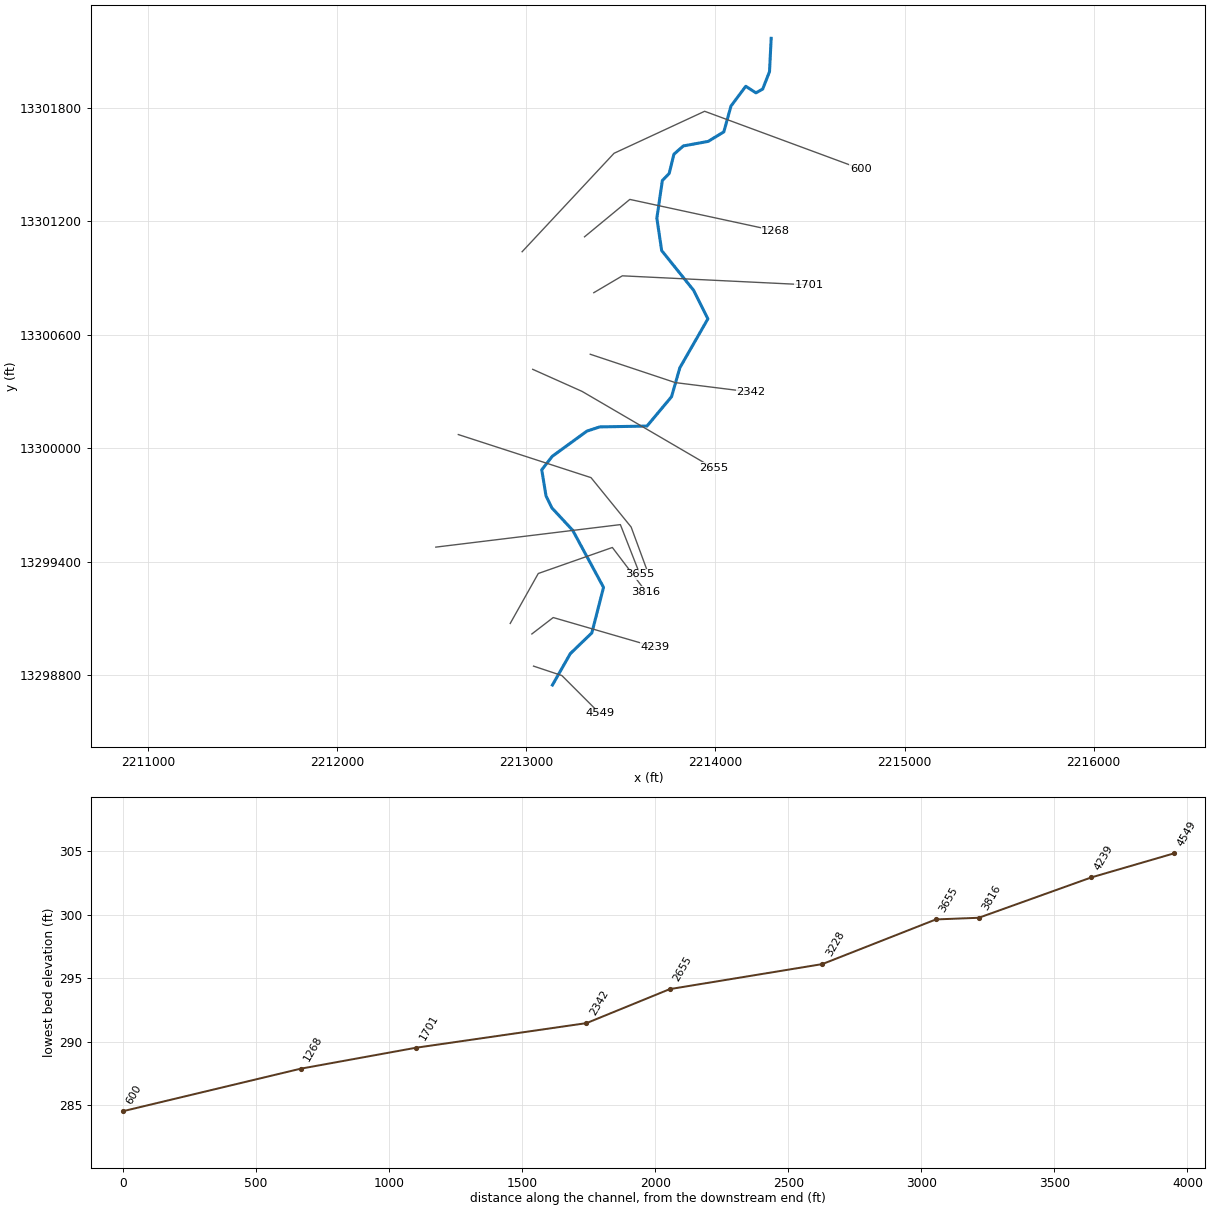
--- UNT045 IN SPCR.prj (project) ---

Proj Title=UNT045 IN SPCR Base Level Engineering
Current Plan=p01
Default Exp/Contr=0.3,0.1
English Units
Geom File=g01
Flow File=f01
Plan File=p01
BEGIN DESCRIPTION:
UNT045 IN SPCR
END DESCRIPTION:

--- UNT045 IN SPCR.p01 (plan) ---

Plan Title=Multiple Run
Short Identifier=Multiple
Geom File=g01
Flow File=f01
Subcritical Flow
K Sum by GR= 0
Std Step Tol= 0.01
Critical Tol= 0.01
Num of Std Step Trials= 20
Max Error Tol= 0.3
Flow Tol Ratio= 0.001
Split Flow NTrial= 30
Split Flow Tol= 0.02
Split Flow Ratio= 0.02
Log Output Level= 0
Friction Slope Method= 1
Unsteady Friction Slope Method= 2
Unsteady Bridges Friction Slope Method= 1
Parabolic Critical Depth
Global Vel Dist=  1 , 1 , 1
Global Log Level= 0
CheckData=True
Encroach Param= -1, 0, 0, 0
BEGIN DESCRIPTION:
Multiple Run
END DESCRIPTION:

--- UNT045 IN SPCR.f01 (steady flow) ---

Flow Title=Multiple
Number of Profiles=7
Profile Names=10-year,25-year,50-year,1pct_min,100-year,1pct_plu,500-year
River Rch & RM= UNT045 IN SPCR,Reach-1,4549
     262     366     453     412     558     754     858
River Rch & RM= UNT045 IN SPCR,Reach-1,2342
     304     427     530     484     655     886    1016
Boundary for River Rch & Prof#=UNT045 IN SPCR,Reach-1,1
Up Type=0
Dn Type=3
Dn Slope=0.005
Boundary for River Rch & Prof#=UNT045 IN SPCR,Reach-1,2
Up Type=0
Dn Type=3
Dn Slope=0.005
Boundary for River Rch & Prof#=UNT045 IN SPCR,Reach-1,3
Up Type=0
Dn Type=3
Dn Slope=0.005
Boundary for River Rch & Prof#=UNT045 IN SPCR,Reach-1,4
Up Type=0
Dn Type=3
Dn Slope=0.005
Boundary for River Rch & Prof#=UNT045 IN SPCR,Reach-1,5
Up Type=0
Dn Type=3
Dn Slope=0.005
Boundary for River Rch & Prof#=UNT045 IN SPCR,Reach-1,6
Up Type=0
Dn Type=3
Dn Slope=0.005
Boundary for River Rch & Prof#=UNT045 IN SPCR,Reach-1,7
Up Type=0
Dn Type=3
Dn Slope=0.005

--- UNT045 IN SPCR.g01 (geometry) ---

Geom Title=Existing Conditions

River Reach=UNT045 IN SPCR,Reach-1
Reach XY= 30
      2213137.72     13298746.85      2213232.26     13298912.94
      2213346.14     13299022.73      2213407.96     13299263.61
      2213245.04     13299565.11      2213134.52     13299684.40
      2213103.66     13299747.77      2213081.24     13299885.42
      2213136.60     13299956.72      2213319.83     13300090.14
      2213388.27     13300112.54      2213637.72     13300116.85
      2213767.45     13300271.97      2213811.57     13300425.26
      2213959.77     13300684.15      2213884.25     13300835.19
      2213715.47     13301045.36      2213689.97     13301216.87
      2213719.06     13301416.07      2213755.25     13301453.41
      2213780.09     13301555.13      2213830.06     13301598.96
      2213961.51     13301623.04      2214044.16     13301673.38
      2214081.86     13301809.76      2214160.15     13301914.71
      2214214.05     13301879.86      2214249.74     13301899.86
      2214285.76     13301992.14      2214294.54     13302168.26

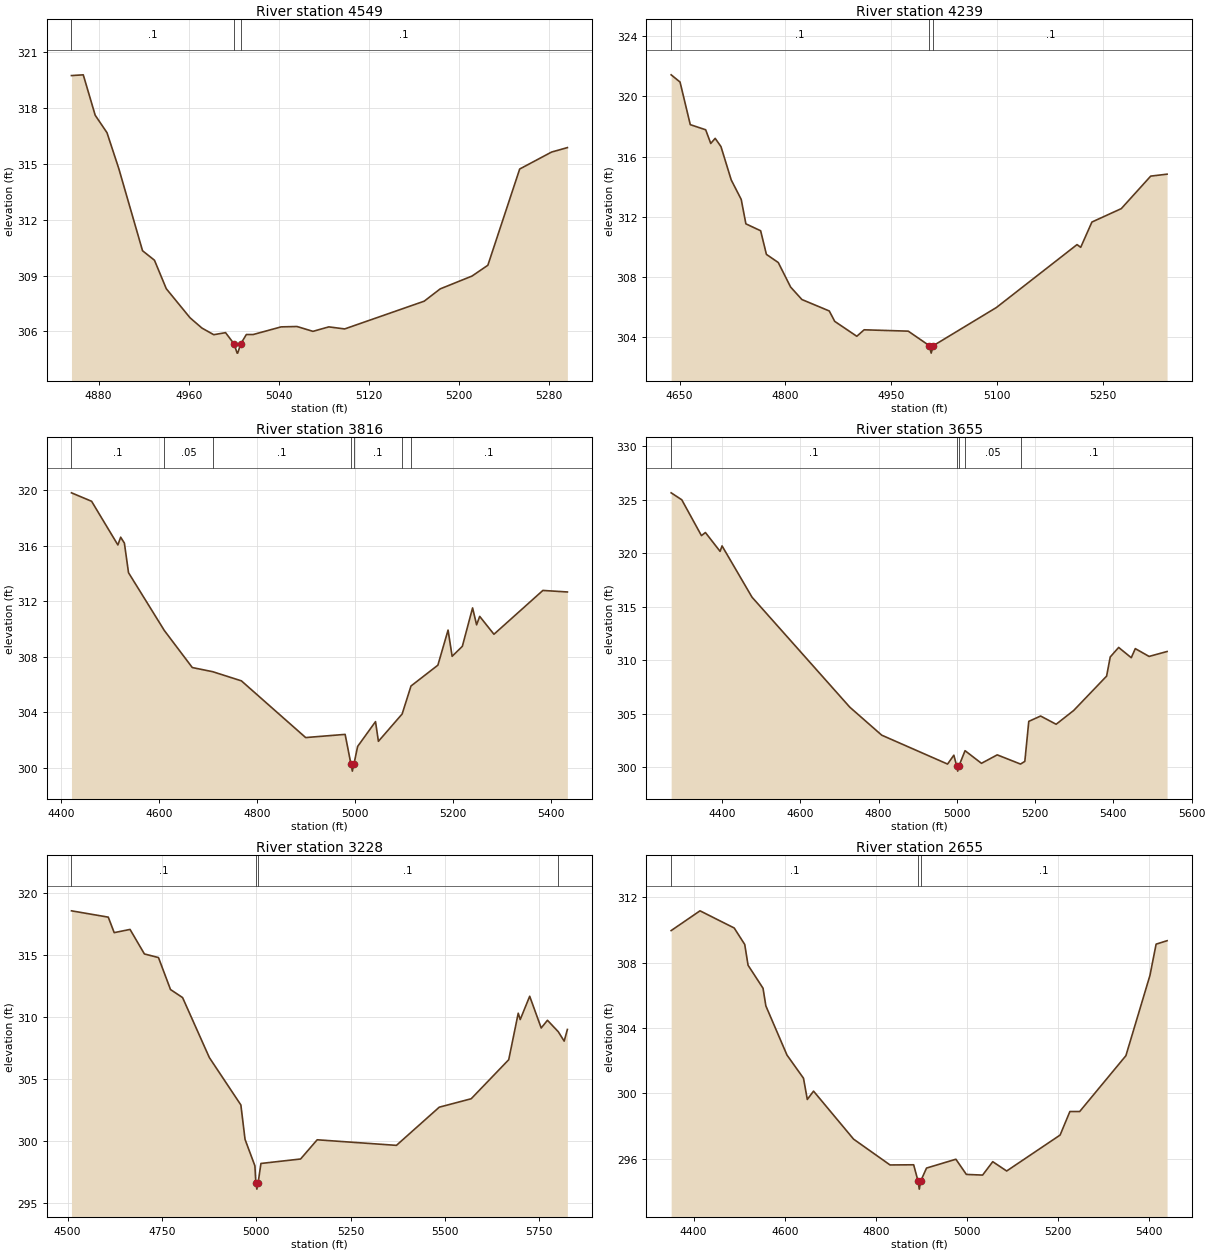
Type RM Length L Ch R = 1,4549,310,310,310
BEGIN DESCRIPTION:
UNT045 IN SPCR 8.0
END DESCRIPTION:
XS GIS Cut Line= 3
      2213037.75     13298846.85      2213187.72     13298796.85
      2213387.70     13298596.88
#Sta/Elev= 30
  4855.8  319.74  4866.3  319.78  4876.9  317.61  4887.4  316.67  4897.9  314.74
  4919.0  310.33  4929.6  309.82  4940.1  308.29  4961.2  306.73  4971.7  306.18
  4982.3  305.82  4992.8  305.93  5000.3  305.33  5003.1  304.83  5003.6  304.83
  5006.3  305.33  5011.3  305.83  5017.4  305.83  5042.2  306.24  5056.3  306.26
  5070.5  306.00  5084.6  306.24  5098.7  306.13  5169.4  307.62  5183.6  308.28
  5211.9  308.97  5226.0  309.55  5254.3  314.72  5282.6  315.63  5296.7  315.87
#Mann=3,-1,0
  4855.8     0.1       0  5000.3    0.07       0  5006.3     0.1       0
Bank Sta=5000.3,5006.3
Exp/Cntr=0.3,0.1

Type RM Length L Ch R = 1,4239,423,423,423
BEGIN DESCRIPTION:
UNT045 IN SPCR 7.0
END DESCRIPTION:
XS GIS Cut Line= 3
      2213028.97     13299017.08      2213141.86     13299103.91
      2213680.02     13298947.67
#Sta/Elev= 30
  4638.0  321.43  4650.6  320.95  4665.1  318.12  4686.9  317.78  4694.1  316.87
  4700.4  317.21  4708.6  316.66  4723.1  314.45  4737.3  313.15  4743.9  311.53
  4764.8  311.07  4773.0  309.50  4789.8  308.96  4807.3  307.33  4823.3  306.50
  4862.1  305.74  4869.8  305.05  4901.1  304.06  4911.5  304.49  4974.0  304.40
  5003.7  303.44  5006.5  302.94  5009.7  303.44  5098.9  305.97  5213.2  310.15
  5218.4  309.97  5234.3  311.65  5275.9  312.54  5317.6  314.70  5340.8  314.83
#Mann=3,-1,0
  4638.0     0.1       0  5003.7    0.07       0  5009.7     0.1       0
Bank Sta=5003.7,5009.7
Exp/Cntr=0.3,0.1

Type RM Length L Ch R = 1,3816,161,161,161
BEGIN DESCRIPTION:
UNT045 IN SPCR 6.0
END DESCRIPTION:
XS GIS Cut Line= 4
      2212914.45     13299072.69      2213062.75     13299336.89
      2213454.66     13299474.54      2213632.06     13299240.91
#Sta/Elev= 30
  4421.4  319.83  4462.5  319.22  4516.1  316.07  4521.8  316.63  4529.4  316.20
  4537.8  314.07  4610.9  309.90  4667.9  307.23  4709.6  306.93  4768.1  306.27
  4899.2  302.18  4979.7  302.41  4991.6  300.26  4994.4  299.76  4997.6  300.26
  5005.2  301.54  5041.7  303.33  5047.6  301.91  5096.0  303.88  5114.1  305.90
  5168.9  307.40  5189.7  309.93  5198.0  308.04  5218.8  308.76  5239.7  311.53
  5247.9  310.31  5254.2  310.92  5283.3  309.63  5383.1  312.79  5433.1  312.68
#Mann=7,-1,0
  4421.4     0.1       0  4610.9    0.05       0  4709.6     0.1       0
  4991.6    0.07       0  4997.6     0.1       0  5096.0    0.05       0
  5114.1     0.1       0
Bank Sta=4991.6,4997.6
Exp/Cntr=0.3,0.1

Type RM Length L Ch R = 1,3655,427,427,427
BEGIN DESCRIPTION:
Mapping XS 4c119ffb
END DESCRIPTION:
XS GIS Cut Line= 3
      2212520.85     13299476.45      2213497.06     13299595.57
      2213600.55     13299331.68
#Sta/Elev= 30
  4270.3  325.64  4297.4  324.99  4347.7  321.64  4357.8  321.93  4395.3  320.17
  4400.3  320.68  4476.8  315.89  4726.6  305.61  4808.2  302.99  4976.4  300.29
  4992.5  301.12  4999.6  300.13  5002.3  299.63  5005.6  300.13  5021.1  301.54
  5063.0  300.36  5103.3  301.15  5162.8  300.29  5173.8  300.54  5183.9  304.28
  5214.1  304.78  5253.8  304.01  5298.7  305.30  5382.7  308.51  5392.0  310.30
  5413.5  311.19  5445.7  310.23  5456.0  311.08  5491.2  310.35  5537.2  310.81
#Mann=5,-1,0
  4270.3     0.1       0  4999.6    0.07       0  5005.6     0.1       0
  5021.1    0.05       0  5162.8     0.1       0
Bank Sta=4999.6,5005.6
Exp/Cntr=0.3,0.1

Type RM Length L Ch R = 1,3228,573,573,573
BEGIN DESCRIPTION:
UNT045 IN SPCR 5.0
END DESCRIPTION:
XS GIS Cut Line= 4
      2212640.00     13300072.01      2213341.70     13299844.15
      2213554.03     13299582.62      2213636.90     13299357.32
#Sta/Elev= 30
  4510.1  318.56  4607.7  318.05  4623.4  316.80  4665.4  317.06  4703.5  315.08
  4740.8  314.79  4772.7  312.21  4804.7  311.56  4875.7  306.72  4959.2  302.90
  4970.3  300.12  4996.4  297.99  4998.9  296.61  5001.6  296.11  5004.9  296.61
  5012.4  298.18  5117.5  298.54  5161.5  300.09  5371.6  299.64  5485.1  302.72
  5569.8  303.40  5669.3  306.55  5694.5  310.30  5699.8  309.79  5724.9  311.67
  5755.4  309.11  5772.0  309.73  5800.6  308.81  5816.3  308.05  5824.8  308.99
#Mann=4,-1,0
  4510.1     0.1       0  4998.9    0.07       0  5004.9     0.1       0
  5800.6    0.05       0
Bank Sta=4998.9,5004.9
Exp/Cntr=0.3,0.1

Type RM Length L Ch R = 1,2655,313,313,313
BEGIN DESCRIPTION:
UNT045 IN SPCR 4.0
END DESCRIPTION:
XS GIS Cut Line= 3
      2213033.43     13300417.13      2213294.56     13300300.31
      2213988.56     13299894.90
#Sta/Elev= 30
  4350.5  309.97  4413.9  311.18  4489.0  310.13  4512.2  309.12  4519.5  307.85
  4552.4  306.44  4558.6  305.36  4605.0  302.35  4641.3  300.93  4649.7  299.63
  4663.4  300.14  4751.4  297.20  4831.5  295.62  4883.4  295.63  4893.0  294.64
  4895.8  294.14  4899.0  294.64  4911.7  295.43  4976.2  295.97  4999.2  295.04
  5034.9  295.00  5057.2  295.82  5087.8  295.25  5205.2  297.45  5226.7  298.89
  5248.2  298.89  5349.8  302.31  5402.7  307.23  5416.2  309.14  5440.3  309.35
#Mann=3,-1,0
  4350.5     0.1       0  4893.0    0.07       0  4899.0     0.1       0
Bank Sta=4893,4899
Exp/Cntr=0.3,0.1

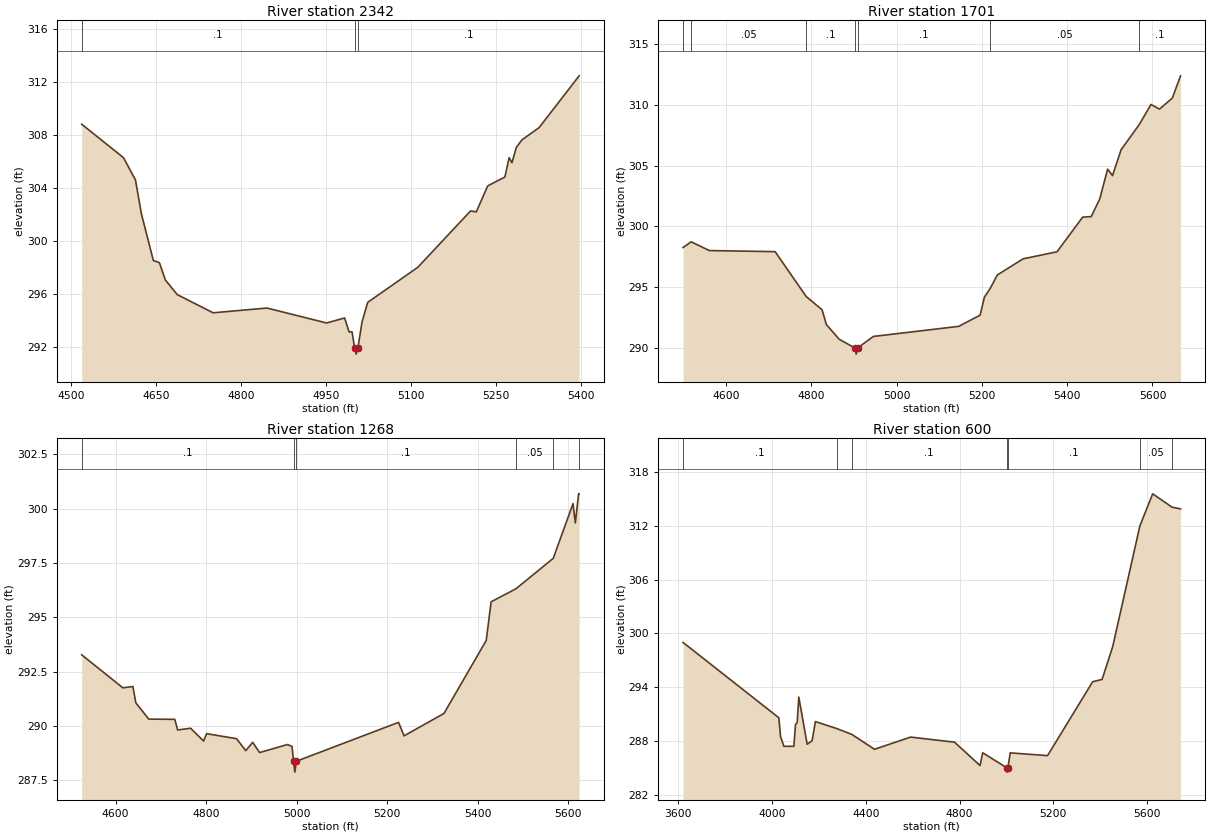
Type RM Length L Ch R = 1,2342,641,641,641
BEGIN DESCRIPTION:
UNT045 IN SPCR 3.0
END DESCRIPTION:
XS GIS Cut Line= 3
      2213337.70     13300496.86      2213787.72     13300346.85
      2214187.74     13300296.85
#Sta/Elev= 30
  4519.2  308.82  4593.0  306.29  4614.1  304.61  4624.6  302.05  4645.7  298.52
  4656.3  298.37  4666.8  297.06  4687.9  295.95  4751.1  294.58  4846.0  294.94
  4951.4  293.81  4983.0  294.19  4990.9  293.14  4996.1  293.14  5000.6  291.96
  5003.4  291.46  5006.6  291.96  5013.7  293.88  5023.8  295.37  5112.0  298.01
  5205.2  302.27  5215.3  302.20  5235.4  304.16  5265.7  304.83  5273.2  306.29
  5278.3  305.91  5285.8  307.06  5295.9  307.64  5326.1  308.56  5396.7  312.47
#Mann=3,-1,0
  4519.2     0.1       0  5000.6    0.07       0  5006.6     0.1       0
Bank Sta=5000.6,5006.6
Exp/Cntr=0.3,0.1

Type RM Length L Ch R = 1,1701,433,433,433
BEGIN DESCRIPTION:
UNT045 IN SPCR 2.0
END DESCRIPTION:
XS GIS Cut Line= 3
      2213356.41     13300822.50      2213507.55     13300911.81
      2214496.92     13300863.72
#Sta/Elev= 30
  4499.7  298.27  4518.7  298.74  4561.3  298.02  4715.5  297.93  4788.5  294.24
  4825.6  293.16  4835.6  291.95  4865.7  290.74  4902.7  290.02  4905.5  289.52
  4908.7  290.02  4945.7  290.97  5146.0  291.80  5196.0  292.72  5206.1  294.20
  5220.0  294.93  5236.1  296.01  5296.7  297.34  5376.3  297.92  5436.3  300.76
  5456.4  300.81  5476.4  302.25  5494.8  304.70  5506.4  304.17  5526.4  306.29
  5569.4  308.38  5596.5  310.01  5616.5  309.63  5646.6  310.54  5665.8  312.36
#Mann=7,-1,0
  4499.7     0.1       0  4518.7    0.05       0  4788.5     0.1       0
  4902.7    0.07       0  4908.7     0.1       0  5220.0    0.05       0
  5569.4     0.1       0
Bank Sta=4902.7,4908.7
Exp/Cntr=0.3,0.1

Type RM Length L Ch R = 1,1268,668,668,668
BEGIN DESCRIPTION:
Mapping XS ba28d34b
END DESCRIPTION:
XS GIS Cut Line= 3
      2213307.44     13301118.14      2213547.05     13301316.08
      2214317.85     13301149.42
#Sta/Elev= 30
  4525.0  293.27  4616.2  291.75  4638.2  291.81  4644.7  291.06  4673.3  290.31
  4730.7  290.30  4737.2  289.81  4765.8  289.89  4794.5  289.30  4801.0  289.64
  4867.2  289.41  4887.6  288.86  4903.0  289.24  4918.3  288.77  4979.7  289.14
  4989.9  289.05  4993.4  288.37  4996.1  287.87  4999.4  288.37  5225.3  290.16
  5237.5  289.54  5325.7  290.57  5419.1  293.93  5429.9  295.71  5484.8  296.31
  5567.2  297.71  5610.9  300.23  5616.0  299.34  5623.2  300.68  5624.4  300.68
#Mann=6,-1,0
  4525.0     0.1       0  4993.4    0.07       0  4999.4     0.1       0
  5484.8    0.05       0  5567.2     0.1       0  5623.2    0.05       0
Bank Sta=4993.4,4999.4
Exp/Cntr=0.3,0.1

Type RM Length L Ch R = 1,600,0,0,0
BEGIN DESCRIPTION:
UNT045 IN SPCR 1.0
END DESCRIPTION:
XS GIS Cut Line= 4
      2212977.48     13301039.32      2213463.57     13301560.13
      2213942.74     13301782.36      2214769.16     13301476.79
#Sta/Elev= 30
  3620.9  298.99  4029.5  290.58  4036.8  288.47  4051.0  287.40  4093.5  287.40
  4100.3  289.81  4107.7  290.07  4114.5  292.89  4150.2  287.63  4171.2  288.02
  4185.3  290.16  4275.3  289.39  4339.9  288.74  4437.5  287.07  4591.4  288.43
  4778.8  287.86  4887.3  285.26  4898.8  286.68  5000.6  285.02  5003.3  284.52
  5006.6  285.02  5016.1  286.67  5175.4  286.36  5367.9  294.61  5408.0  294.86
  5453.2  298.51  5569.2  311.99  5623.8  315.57  5706.5  314.08  5742.6  313.89
#Mann=7,-1,0
  3620.9     0.1       0  4275.3    0.05       0  4339.9     0.1       0
  5000.6    0.07       0  5006.6     0.1       0  5569.2    0.05       0
  5706.5     0.1       0
Bank Sta=5000.6,5006.6
Exp/Cntr=0.3,0.1

Chan Stop Cuts=-1