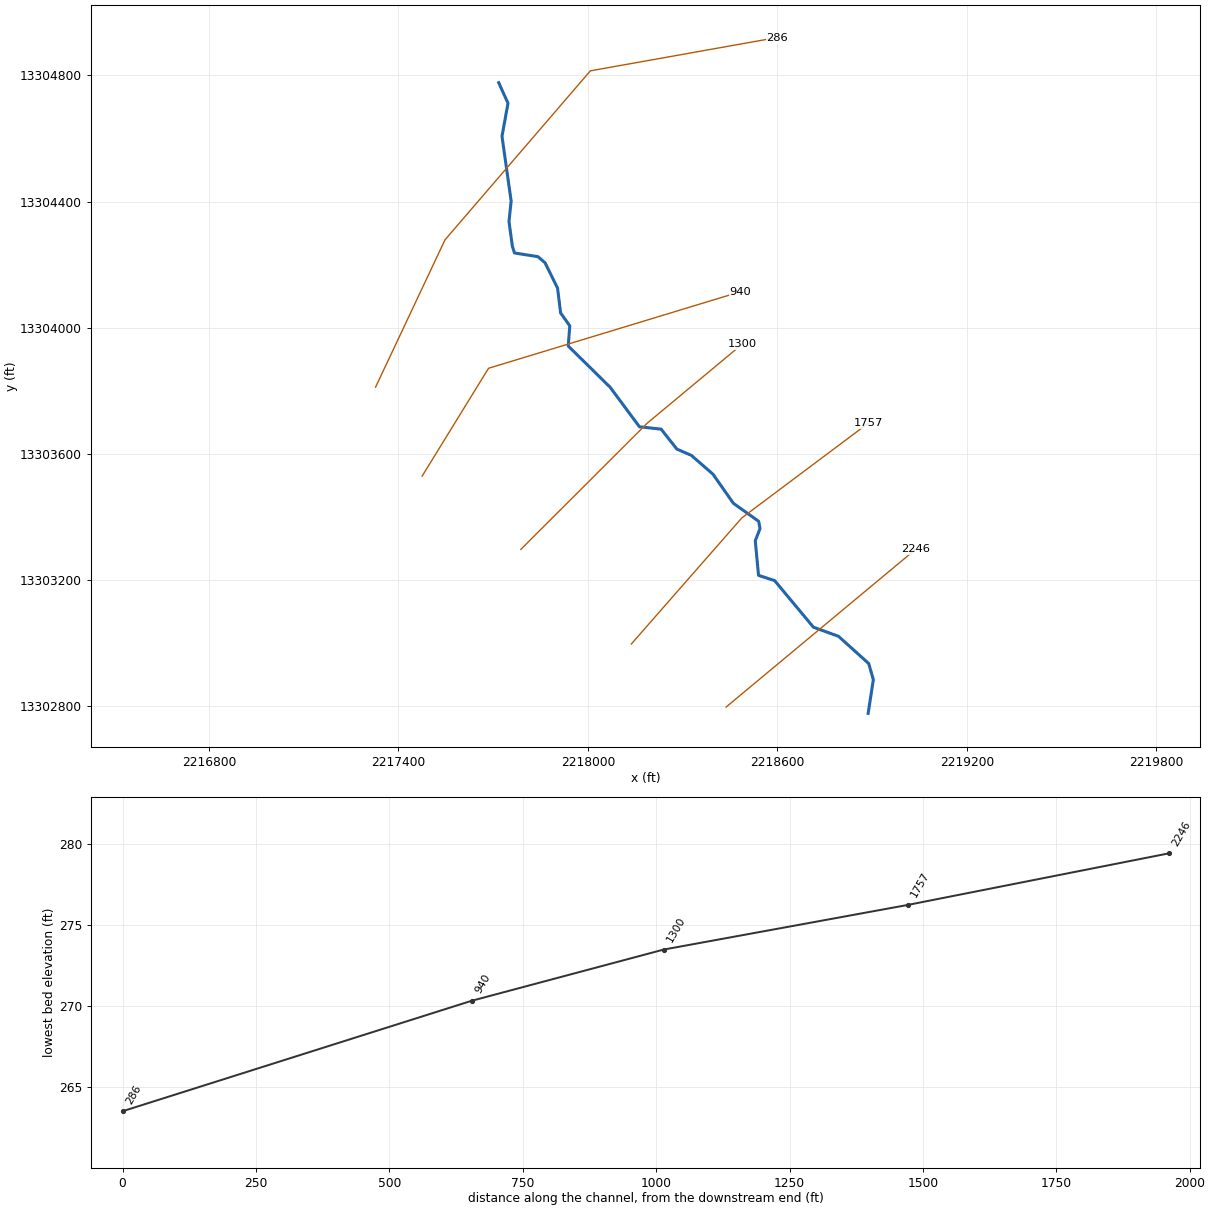
--- UNT046 IN SPCR.prj (project) ---

Proj Title=UNT046 IN SPCR Base Level Engineering
Current Plan=p01
Default Exp/Contr=0.3,0.1
English Units
Geom File=g01
Flow File=f01
Plan File=p01
BEGIN DESCRIPTION:
UNT046 IN SPCR
END DESCRIPTION:

--- UNT046 IN SPCR.p01 (plan) ---

Plan Title=Multiple Run
Short Identifier=Multiple
Geom File=g01
Flow File=f01
Subcritical Flow
K Sum by GR= 0
Std Step Tol= 0.01
Critical Tol= 0.01
Num of Std Step Trials= 20
Max Error Tol= 0.3
Flow Tol Ratio= 0.001
Split Flow NTrial= 30
Split Flow Tol= 0.02
Split Flow Ratio= 0.02
Log Output Level= 0
Friction Slope Method= 1
Unsteady Friction Slope Method= 2
Unsteady Bridges Friction Slope Method= 1
Parabolic Critical Depth
Global Vel Dist=  1 , 1 , 1
Global Log Level= 0
CheckData=True
Encroach Param= -1, 0, 0, 0
BEGIN DESCRIPTION:
Multiple Run
END DESCRIPTION:

--- UNT046 IN SPCR.f01 (steady flow) ---

Flow Title=Multiple
Number of Profiles=7
Profile Names=10-year,25-year,50-year,1pct_min,100-year,1pct_plu,500-year
River Rch & RM= UNT046 IN SPCR,Reach-1,2246
     193     265     324     292     395     534     594
River Rch & RM= UNT046 IN SPCR,Reach-1,1757
     247     344     424     385     520     703     796
Boundary for River Rch & Prof#=UNT046 IN SPCR,Reach-1,1
Up Type=0
Dn Type=3
Dn Slope=0.005
Boundary for River Rch & Prof#=UNT046 IN SPCR,Reach-1,2
Up Type=0
Dn Type=3
Dn Slope=0.005
Boundary for River Rch & Prof#=UNT046 IN SPCR,Reach-1,3
Up Type=0
Dn Type=3
Dn Slope=0.005
Boundary for River Rch & Prof#=UNT046 IN SPCR,Reach-1,4
Up Type=0
Dn Type=3
Dn Slope=0.005
Boundary for River Rch & Prof#=UNT046 IN SPCR,Reach-1,5
Up Type=0
Dn Type=3
Dn Slope=0.005
Boundary for River Rch & Prof#=UNT046 IN SPCR,Reach-1,6
Up Type=0
Dn Type=3
Dn Slope=0.005
Boundary for River Rch & Prof#=UNT046 IN SPCR,Reach-1,7
Up Type=0
Dn Type=3
Dn Slope=0.005

--- UNT046 IN SPCR.g01 (geometry) ---

Geom Title=Existing Conditions

River Reach=UNT046 IN SPCR,Reach-1
Reach XY= 30
      2218887.72     13302776.85      2218904.07     13302883.84
      2218889.48     13302934.88      2218793.65     13303021.34
      2218714.34     13303050.11      2218591.71     13303197.74
      2218540.50     13303214.55      2218530.18     13303324.39
      2218545.30     13303362.73      2218540.85     13303386.05
      2218460.78     13303443.09      2218396.31     13303535.32
      2218327.74     13303595.06      2218281.95     13303614.88
      2218232.09     13303678.16      2218163.41     13303685.77
      2218070.05     13303811.67      2217937.90     13303941.74
      2217942.81     13304005.78      2217913.74     13304046.78
      2217904.03     13304125.65      2217864.43     13304205.75
      2217842.15     13304225.11      2217767.72     13304236.85
      2217761.05     13304257.71      2217750.27     13304336.84
      2217757.06     13304401.47      2217728.12     13304607.06
      2217747.14     13304711.71      2217717.72     13304776.85

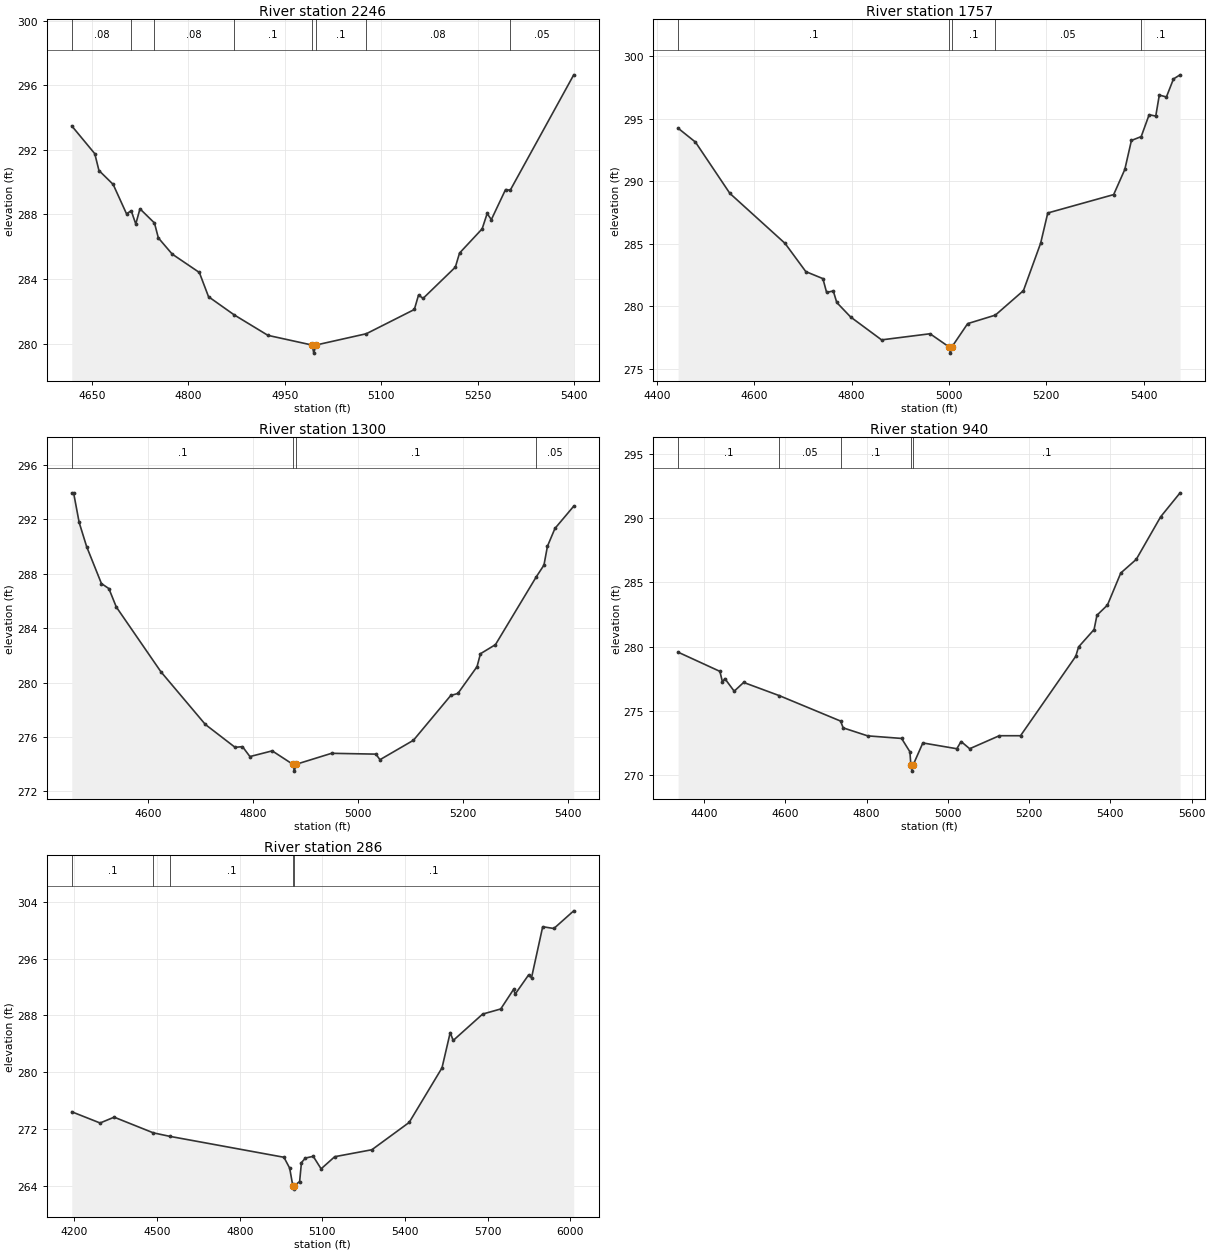
Type RM Length L Ch R = 1,2246,489,489,489
BEGIN DESCRIPTION:
UNT046 IN SPCR 5.0
END DESCRIPTION:
XS GIS Cut Line= 3
      2218437.74     13302796.87      2218737.72     13303046.85
      2219037.72     13303296.86
#Sta/Elev= 30
  4618.4  293.48  4654.2  291.76  4660.7  290.72  4682.8  289.86  4703.6  288.04
  4710.9  288.23  4718.0  287.41  4724.5  288.35  4747.1  287.47  4753.1  286.55
  4774.6  285.55  4816.9  284.41  4831.2  282.91  4871.0  281.79  4923.6  280.52
  4992.2  279.92  4995.0  279.42  4998.2  279.92  5076.7  280.62  5151.4  282.12
  5157.9  283.01  5165.1  282.81  5215.2  284.74  5221.7  285.61  5256.9  287.11
  5264.7  288.06  5271.2  287.68  5293.3  289.54  5300.6  289.50  5399.4  296.64
#Mann=8,-1,0
  4618.4    0.08       0  4710.9     0.1       0  4747.1    0.08       0
  4871.0     0.1       0  4992.2    0.07       0  4998.2     0.1       0
  5076.7    0.08       0  5300.6    0.05       0
Bank Sta=4992.2,4998.2
Exp/Cntr=0.3,0.1

Type RM Length L Ch R = 1,1757,457,457,457
BEGIN DESCRIPTION:
UNT046 IN SPCR 4.0
END DESCRIPTION:
XS GIS Cut Line= 3
      2218137.73     13302996.87      2218487.72     13303396.85
      2218887.73     13303696.86
#Sta/Elev= 30
  4443.4  294.23  4479.0  293.12  4549.7  289.02  4663.1  285.02  4705.8  282.76
  4740.9  282.20  4748.5  281.10  4762.3  281.21  4769.4  280.29  4797.9  279.13
  4861.5  277.30  4961.1  277.79  5000.0  276.74  5002.8  276.24  5006.0  276.74
  5038.4  278.60  5095.3  279.28  5153.0  281.24  5188.4  285.04  5203.0  287.45
  5338.4  288.92  5361.3  290.93  5374.9  293.25  5395.0  293.56  5411.3  295.31
  5424.9  295.20  5432.2  296.88  5446.8  296.73  5461.3  298.17  5474.9  298.50
#Mann=5,-1,0
  4443.4     0.1       0  5000.0    0.07       0  5006.0     0.1       0
  5095.3    0.05       0  5395.0     0.1       0
Bank Sta=5000,5006
Exp/Cntr=0.3,0.1

Type RM Length L Ch R = 1,1300,360,360,360
BEGIN DESCRIPTION:
UNT046 IN SPCR 3.0
END DESCRIPTION:
XS GIS Cut Line= 3
      2217787.74     13303296.87      2218187.72     13303696.85
      2218487.74     13303946.87
#Sta/Elev= 30
  4455.1  293.95  4458.6  293.95  4469.2  291.77  4483.4  290.00  4511.6  287.28
  4525.8  286.91  4539.9  285.56  4624.8  280.80  4709.6  276.92  4766.2  275.24
  4780.3  275.29  4794.5  274.56  4836.9  274.98  4876.3  273.99  4879.1  273.49
  4882.3  273.99  4950.0  274.80  5034.4  274.74  5042.2  274.33  5106.0  275.76
  5177.0  279.05  5190.6  279.20  5227.1  281.17  5233.6  282.12  5262.2  282.79
  5339.4  287.74  5354.6  288.64  5361.2  290.02  5375.5  291.33  5411.3  292.97
#Mann=4,-1,0
  4455.1     0.1       0  4876.3    0.07       0  4882.3     0.1       0
  5339.4    0.05       0
Bank Sta=4876.3,4882.3
Exp/Cntr=0.3,0.1

Type RM Length L Ch R = 1,940,654,654,654
BEGIN DESCRIPTION:
UNT046 IN SPCR 2.0
END DESCRIPTION:
XS GIS Cut Line= 3
      2217475.24     13303529.32      2217685.51     13303871.20
      2218483.41     13304114.04
#Sta/Elev= 30
  4336.2  279.57  4439.0  278.08  4445.4  277.25  4451.2  277.52  4474.2  276.54
  4497.5  277.22  4585.6  276.19  4736.0  274.22  4742.5  273.69  4802.6  273.07
  4886.2  272.87  4906.7  271.83  4908.9  270.83  4911.7  270.33  4914.9  270.83
  4938.5  272.52  5022.1  272.07  5032.6  272.63  5053.8  272.07  5126.6  273.08
  5178.9  273.08  5314.8  279.25  5321.8  279.98  5359.9  281.33  5367.0  282.44
  5392.8  283.23  5425.6  285.72  5463.7  286.78  5523.8  290.09  5571.6  291.95
#Mann=5,-1,0
  4336.2     0.1       0  4585.6    0.05       0  4736.0     0.1       0
  4908.9    0.07       0  4914.9     0.1       0
Bank Sta=4908.9,4914.9
Exp/Cntr=0.3,0.1

Type RM Length L Ch R = 1,286,0,0,0
BEGIN DESCRIPTION:
UNT046 IN SPCR 1.0
END DESCRIPTION:
XS GIS Cut Line= 5
      2217327.75     13303811.31      2217547.62     13304278.54
      2218007.97     13304814.46      2218585.12     13304917.53
      2218598.86     13304917.53
#Sta/Elev= 30
  4190.1  274.42  4292.9  272.84  4344.1  273.66  4486.4  271.45  4547.2  270.95
  4960.6  268.01  4981.4  266.48  4992.7  264.02  4995.5  263.52  4998.7  264.02
  5017.6  264.59  5024.2  267.26  5038.5  267.90  5067.0  268.14  5095.6  266.38
  5145.0  268.09  5279.9  269.07  5415.4  272.92  5534.6  280.61  5564.4  285.58
  5575.3  284.47  5682.2  288.19  5747.9  288.91  5795.0  291.70  5800.1  290.99
  5848.8  293.69  5859.7  293.31  5900.3  300.50  5940.9  300.25  6013.0  302.74
#Mann=5,-1,0
  4190.1     0.1       0  4486.4    0.05       0  4547.2     0.1       0
  4992.7    0.07       0  4998.7     0.1       0
Bank Sta=4992.7,4998.7
Exp/Cntr=0.3,0.1

Chan Stop Cuts=-1