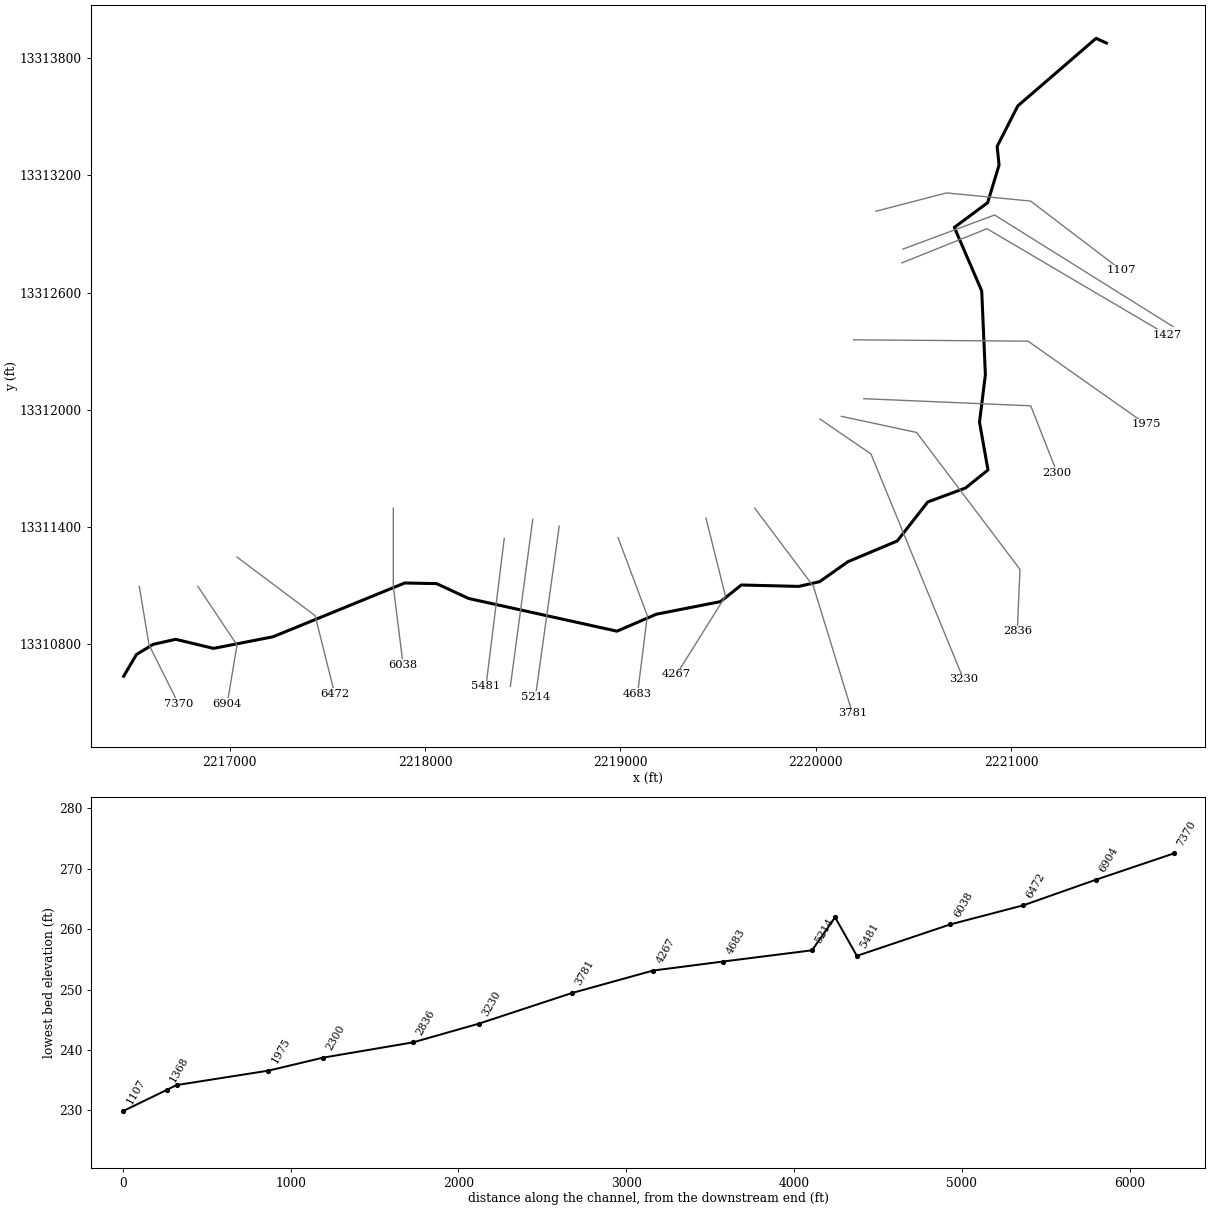
--- UNT047 IN SPCR.prj (project) ---

Proj Title=UNT047 IN SPCR Base Level Engineering
Current Plan=p01
Default Exp/Contr=0.3,0.1
English Units
Geom File=g01
Flow File=f01
Plan File=p01
BEGIN DESCRIPTION:
UNT047 IN SPCR
END DESCRIPTION:

--- UNT047 IN SPCR.p01 (plan) ---

Plan Title=Multiple Run
Short Identifier=Multiple
Geom File=g01
Flow File=f01
Subcritical Flow
K Sum by GR= 0
Std Step Tol= 0.01
Critical Tol= 0.01
Num of Std Step Trials= 20
Max Error Tol= 0.3
Flow Tol Ratio= 0.001
Split Flow NTrial= 30
Split Flow Tol= 0.02
Split Flow Ratio= 0.02
Log Output Level= 0
Friction Slope Method= 1
Unsteady Friction Slope Method= 2
Unsteady Bridges Friction Slope Method= 1
Parabolic Critical Depth
Global Vel Dist=  1 , 1 , 1
Global Log Level= 0
CheckData=True
Encroach Param= -1, 0, 0, 0
BEGIN DESCRIPTION:
Multiple Run
END DESCRIPTION:

--- UNT047 IN SPCR.f01 (steady flow) ---

Flow Title=Multiple
Number of Profiles=7
Profile Names=10-year,25-year,50-year,1pct_min,100-year,1pct_plu,500-year
River Rch & RM= UNT047 IN SPCR,Reach-1,7370
     214     297     367     333     450     609     690
River Rch & RM= UNT047 IN SPCR,Reach-1,6472
     255     356     440     400     541     732     832
Boundary for River Rch & Prof#=UNT047 IN SPCR,Reach-1,1
Up Type=0
Dn Type=3
Dn Slope=0.005
Boundary for River Rch & Prof#=UNT047 IN SPCR,Reach-1,2
Up Type=0
Dn Type=3
Dn Slope=0.005
Boundary for River Rch & Prof#=UNT047 IN SPCR,Reach-1,3
Up Type=0
Dn Type=3
Dn Slope=0.005
Boundary for River Rch & Prof#=UNT047 IN SPCR,Reach-1,4
Up Type=0
Dn Type=3
Dn Slope=0.005
Boundary for River Rch & Prof#=UNT047 IN SPCR,Reach-1,5
Up Type=0
Dn Type=3
Dn Slope=0.005
Boundary for River Rch & Prof#=UNT047 IN SPCR,Reach-1,6
Up Type=0
Dn Type=3
Dn Slope=0.005
Boundary for River Rch & Prof#=UNT047 IN SPCR,Reach-1,7
Up Type=0
Dn Type=3
Dn Slope=0.005

--- UNT047 IN SPCR.g01 (geometry) ---

Geom Title=Existing Conditions

River Reach=UNT047 IN SPCR,Reach-1
Reach XY= 30
      2216457.72     13310636.85      2216523.11     13310748.29
      2216608.65     13310800.09      2216724.01     13310825.95
      2216917.47     13310779.45      2217222.29     13310838.98
      2217895.94     13311114.16      2218058.96     13311111.03
      2218223.02     13311034.99      2218982.53     13310867.61
      2219183.79     13310954.34      2219512.68     13311018.96
      2219618.58     13311103.90      2219912.74     13311096.72
      2220019.66     13311120.99      2220164.50     13311223.12
      2220416.92     13311329.26      2220572.86     13311528.82
      2220766.24     13311600.27      2220881.21     13311692.66
      2220837.80     13311937.00      2220867.85     13312180.33
      2220849.07     13312608.95      2220708.96     13312933.95
      2220879.50     13313060.64      2220937.83     13313253.01
      2220928.11     13313348.84      2221033.67     13313555.78
      2221434.36     13313901.62      2221487.35     13313877.60

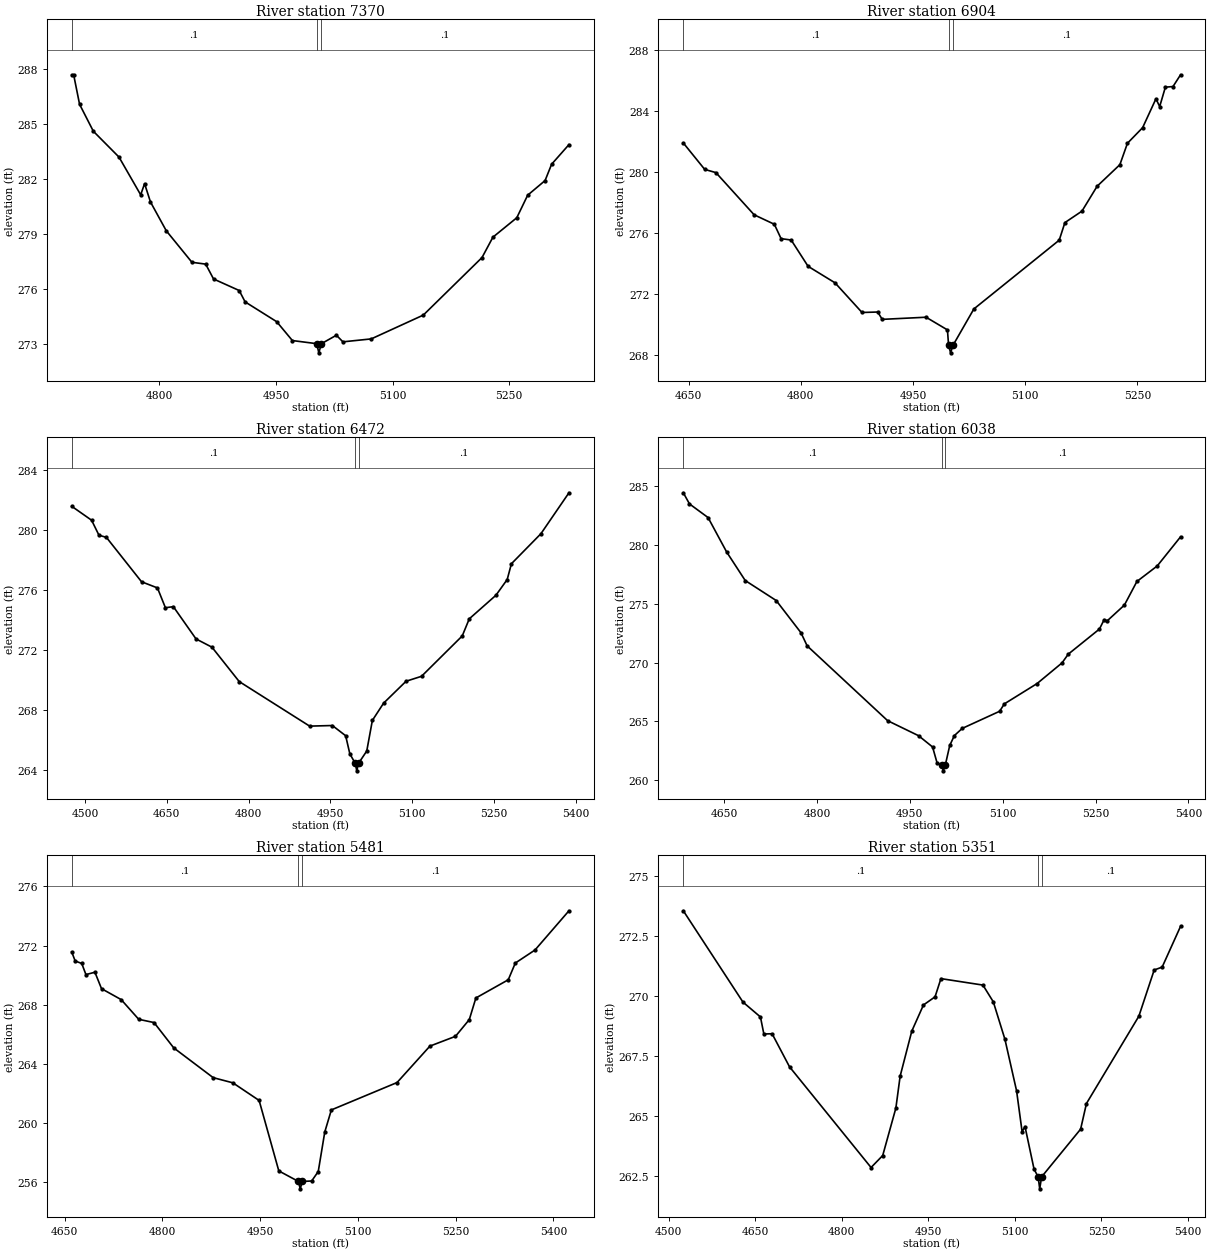
Type RM Length L Ch R = 1,7370,466,466,466
BEGIN DESCRIPTION:
UNT047 IN SPCR 11.0
END DESCRIPTION:
XS GIS Cut Line= 3
      2216537.73     13311096.82      2216587.72     13310796.85
      2216737.72     13310496.87
#Sta/Elev= 30
  4687.4  287.70  4689.9  287.70  4697.5  286.09  4715.2  284.62  4748.2  283.21
  4776.1  281.15  4781.1  281.76  4788.7  280.76  4809.0  279.19  4842.0  277.47
  4859.7  277.37  4869.8  276.56  4902.8  275.93  4910.4  275.31  4951.0  274.23
  4971.2  273.20  5002.5  273.03  5005.2  272.53  5008.5  273.03  5027.8  273.49
  5036.2  273.13  5072.6  273.29  5139.6  274.59  5215.1  277.73  5229.1  278.84
  5259.8  279.90  5273.8  281.13  5296.2  281.93  5304.6  282.82  5326.9  283.89
#Mann=3,-1,0
  4687.4     0.1       0  5002.5    0.07       0  5008.5     0.1       0
Bank Sta=5002.5,5008.5
Exp/Cntr=0.3,0.1

Type RM Length L Ch R = 1,6904,432,432,432
BEGIN DESCRIPTION:
UNT047 IN SPCR 10.0
END DESCRIPTION:
XS GIS Cut Line= 3
      2216837.71     13311096.87      2217037.72     13310796.85
      2216987.72     13310496.86
#Sta/Elev= 30
  4642.9  281.89  4671.5  280.16  4686.5  279.95  4737.6  277.19  4764.6  276.57
  4773.6  275.63  4787.1  275.54  4809.7  273.82  4845.7  272.74  4881.8  270.80
  4902.8  270.83  4908.8  270.35  4967.4  270.49  4996.0  269.66  4997.5  268.66
  5000.2  268.16  5003.5  268.66  5031.3  271.03  5145.4  275.53  5153.0  276.68
  5175.8  277.43  5196.1  279.06  5226.5  280.47  5236.6  281.87  5256.9  282.89
  5274.7  284.78  5279.7  284.27  5287.3  285.54  5297.5  285.58  5307.6  286.35
#Mann=3,-1,0
  4642.9     0.1       0  4997.5    0.07       0  5003.5     0.1       0
Bank Sta=4997.5,5003.5
Exp/Cntr=0.3,0.1

Type RM Length L Ch R = 1,6472,434,434,434
BEGIN DESCRIPTION:
UNT047 IN SPCR 9.0
END DESCRIPTION:
XS GIS Cut Line= 3
      2217037.70     13311246.87      2217437.72     13310946.85
      2217537.71     13310546.89
#Sta/Elev= 30
  4475.6  281.56  4512.1  280.63  4525.6  279.63  4539.2  279.49  4603.7  276.53
  4632.9  276.12  4647.5  274.80  4662.1  274.87  4703.7  272.72  4732.9  272.17
  4782.9  269.88  4912.1  266.91  4953.8  266.95  4978.2  266.27  4985.9  265.06
  4995.8  264.43  4998.6  263.93  5001.8  264.43  5016.9  265.25  5027.2  267.29
  5047.8  268.44  5089.0  269.90  5117.4  270.23  5192.1  272.92  5205.0  274.06
  5253.9  275.63  5274.6  276.68  5282.3  277.73  5336.4  279.73  5387.9  282.46
#Mann=3,-1,0
  4475.6     0.1       0  4995.8    0.07       0  5001.8     0.1       0
Bank Sta=4995.8,5001.8
Exp/Cntr=0.3,0.1

Type RM Length L Ch R = 1,6038,557,557,557
BEGIN DESCRIPTION:
UNT047 IN SPCR 8.0
END DESCRIPTION:
XS GIS Cut Line= 3
      2217837.72     13311496.89      2217837.72     13311096.85
      2217887.71     13310696.90
#Sta/Elev= 30
  4584.2  284.45  4594.2  283.50  4624.2  282.34  4654.2  279.41  4684.2  276.98
  4734.2  275.28  4774.2  272.54  4784.2  271.42  4914.2  265.05  4964.2  263.77
  4986.8  262.81  4994.3  261.41  5001.4  261.28  5004.1  260.78  5007.4  261.28
  5014.5  262.94  5022.0  263.78  5034.6  264.39  5095.1  265.85  5102.7  266.48
  5155.6  268.21  5195.9  269.97  5205.9  270.71  5256.3  272.85  5263.9  273.65
  5268.9  273.55  5296.6  274.89  5316.8  276.90  5349.6  278.22  5387.3  280.70
#Mann=3,-1,0
  4584.2     0.1       0  5001.4    0.07       0  5007.4     0.1       0
Bank Sta=5001.4,5007.4
Exp/Cntr=0.3,0.1

Type RM Length L Ch R = 1,5481,130,130,130
BEGIN DESCRIPTION:
UNT047 IN SPCR 7.0
END DESCRIPTION:
XS GIS Cut Line= 2
      2218405.56     13311342.16      2218311.81     13310585.14
#Sta/Elev= 30
  4661.0  271.57  4666.3  270.96  4676.4  270.79  4682.8  270.04  4696.6  270.20
  4706.7  269.09  4736.9  268.35  4763.8  267.02  4787.3  266.80  4817.5  265.09
  4878.0  263.08  4908.2  262.73  4948.5  261.54  4978.7  256.78  5008.8  256.07
  5011.5  255.57  5014.8  256.07  5029.1  256.10  5039.2  256.74  5049.2  259.41
  5059.3  260.90  5160.1  262.75  5210.5  265.21  5249.7  265.87  5270.9  267.00
  5281.0  268.46  5330.7  269.69  5341.5  270.82  5371.7  271.70  5423.8  274.35
#Mann=3,-1,0
  4661.0     0.1       0  5008.8    0.07       0  5014.8     0.1       0
Bank Sta=5008.8,5014.8
Exp/Cntr=0.3,0.1

Type RM Length L Ch R = 1,5351,137,137,137
BEGIN DESCRIPTION:
Mapping XS 6de58fbb
END DESCRIPTION:
XS GIS Cut Line= 2
      2218551.39     13311439.35      2218436.81     13310585.20
#Sta/Elev= 30
  4525.3  273.56  4628.7  269.75  4659.0  269.13  4664.9  268.42  4679.2  268.43
  4709.4  267.05  4850.7  262.85  4870.9  263.35  4893.7  265.33  4901.1  266.66
  4921.3  268.54  4941.5  269.63  4961.6  269.97  4971.8  270.73  5044.6  270.46
  5062.6  269.76  5082.7  268.20  5102.9  266.05  5112.5  264.34  5117.5  264.56
  5133.2  262.78  5140.3  262.46  5143.0  261.96  5146.3  262.46  5213.9  264.45
  5224.0  265.52  5314.8  269.16  5341.4  271.09  5355.2  271.21  5387.1  272.91
#Mann=3,-1,0
  4525.3     0.1       0  5140.3    0.07       0  5146.3     0.1       0
Bank Sta=5140.3,5146.3
Exp/Cntr=0.3,0.1

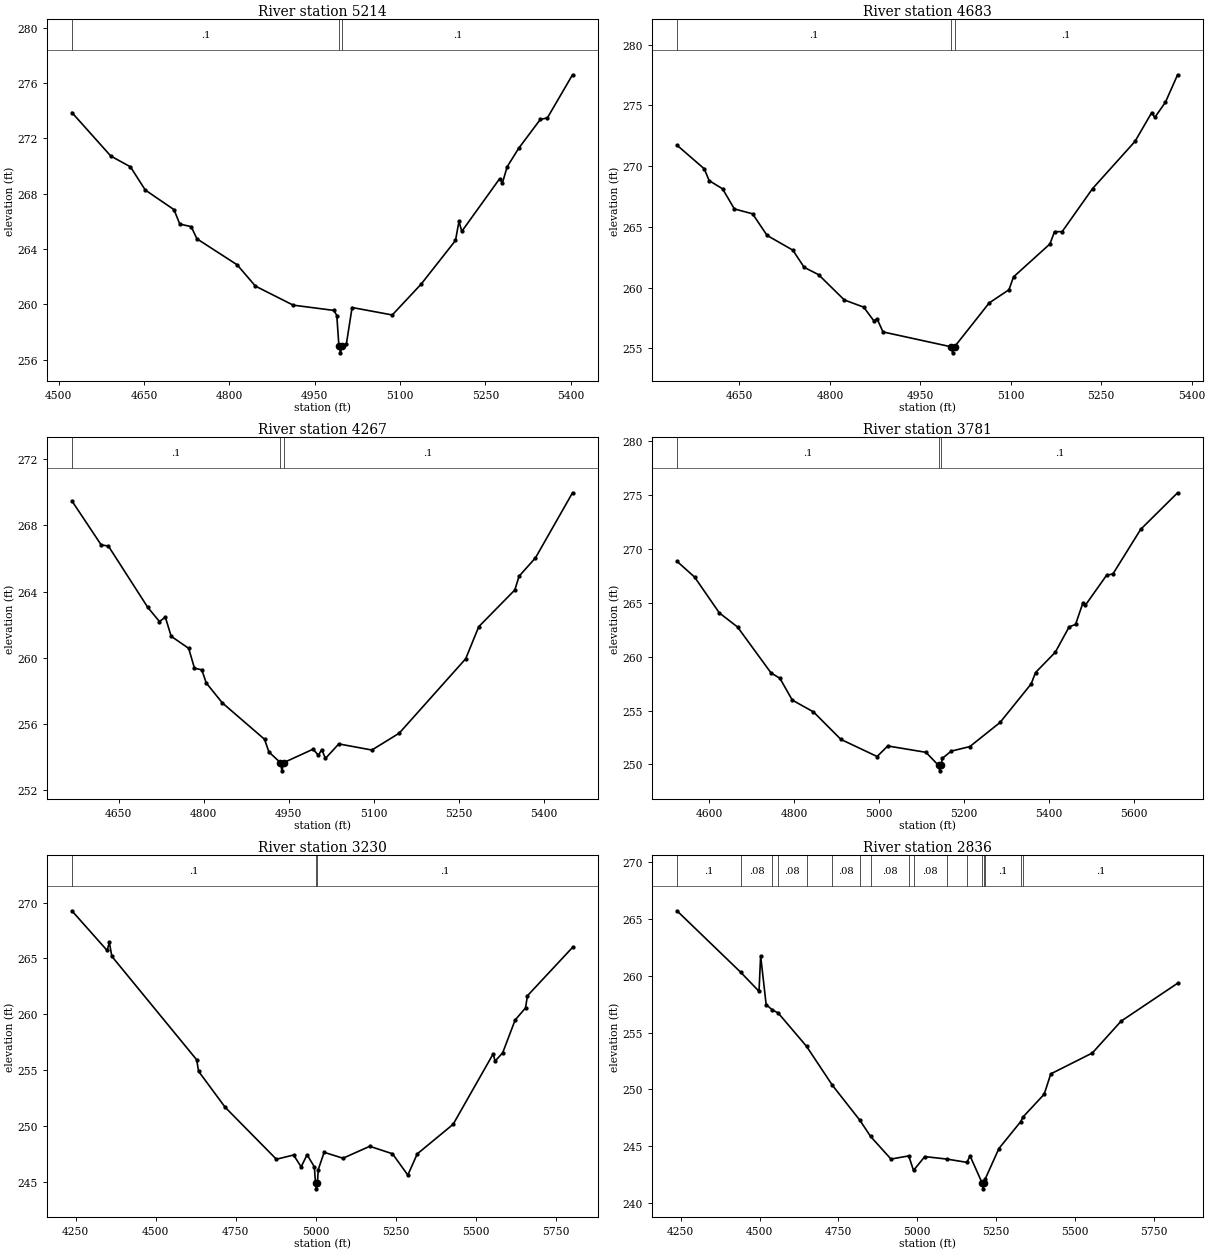
Type RM Length L Ch R = 1,5214,531,531,531
BEGIN DESCRIPTION:
UNT047 IN SPCR 6.0
END DESCRIPTION:
XS GIS Cut Line= 2
      2218686.81     13311404.59      2218565.29     13310533.13
#Sta/Elev= 30
  4523.1  273.88  4591.5  270.73  4626.0  269.95  4652.1  268.27  4702.6  266.85
  4712.7  265.81  4732.8  265.62  4742.9  264.74  4813.6  262.86  4845.6  261.32
  4912.1  259.94  4983.7  259.56  4988.7  259.19  4992.4  256.99  4995.1  256.49
  4998.4  256.99  5005.5  257.13  5015.6  259.77  5086.2  259.23  5136.9  261.46
  5197.3  264.62  5203.4  266.00  5208.4  265.28  5274.9  269.09  5279.9  268.80
  5288.2  269.96  5308.4  271.29  5346.4  273.38  5358.8  273.49  5403.0  276.61
#Mann=3,-1,0
  4523.1     0.1       0  4992.4    0.07       0  4998.4     0.1       0
Bank Sta=4992.4,4998.4
Exp/Cntr=0.3,0.1

Type RM Length L Ch R = 1,4683,416,416,416
BEGIN DESCRIPTION:
UNT047 IN SPCR 5.0
END DESCRIPTION:
XS GIS Cut Line= 3
      2218987.74     13311346.81      2219137.72     13310946.85
      2219087.72     13310546.82
#Sta/Elev= 30
  4546.3  271.72  4591.6  269.77  4599.7  268.80  4621.9  268.13  4641.5  266.47
  4671.7  266.07  4695.8  264.29  4738.5  263.08  4757.2  261.67  4781.2  261.06
  4823.9  258.98  4856.0  258.39  4872.9  257.26  4878.2  257.43  4888.0  256.35
  5000.7  255.13  5003.4  254.63  5006.7  255.13  5064.2  258.74  5096.9  259.82
  5104.5  260.88  5164.9  263.59  5172.5  264.60  5185.1  264.60  5235.5  268.14
  5306.0  272.03  5333.7  274.40  5338.8  274.00  5356.4  275.25  5376.6  277.51
#Mann=3,-1,0
  4546.3     0.1       0  5000.7    0.07       0  5006.7     0.1       0
Bank Sta=5000.7,5006.7
Exp/Cntr=0.3,0.1

Type RM Length L Ch R = 1,4267,486,486,486
BEGIN DESCRIPTION:
UNT047 IN SPCR 4.0
END DESCRIPTION:
XS GIS Cut Line= 3
      2219437.71     13311446.89      2219537.72     13311046.85
      2219287.75     13310646.89
#Sta/Elev= 30
  4567.1  269.49  4618.7  266.83  4631.6  266.75  4701.1  263.04  4721.8  262.18
  4732.1  262.45  4742.4  261.29  4773.3  260.56  4783.6  259.35  4796.5  259.26
  4804.2  258.47  4832.6  257.26  4907.3  255.05  4915.0  254.28  4935.2  253.64
  4938.0  253.14  4941.2  253.64  4993.0  254.45  5002.4  254.08  5008.3  254.43
  5014.8  253.89  5038.4  254.77  5096.8  254.40  5145.1  255.42  5262.5  259.93
  5285.5  261.87  5349.1  264.09  5356.8  264.93  5385.7  266.04  5451.1  269.98
#Mann=3,-1,0
  4567.1     0.1       0  4935.2    0.07       0  4941.2     0.1       0
Bank Sta=4935.2,4941.2
Exp/Cntr=0.3,0.1

Type RM Length L Ch R = 1,3781,551,551,551
BEGIN DESCRIPTION:
UNT047 IN SPCR 3.0
END DESCRIPTION:
XS GIS Cut Line= 3
      2219687.74     13311496.82      2219987.72     13311096.85
      2220187.71     13310446.89
#Sta/Elev= 30
  4523.3  268.86  4564.9  267.39  4623.3  264.06  4666.0  262.76  4745.1  258.49
  4766.0  257.99  4795.1  255.97  4845.1  254.87  4909.7  252.32  4995.1  250.73
  5020.1  251.71  5110.2  251.12  5139.9  249.90  5142.7  249.40  5145.9  249.90
  5148.8  250.56  5169.7  251.23  5213.5  251.65  5284.8  253.89  5358.1  257.47
  5368.5  258.53  5415.0  260.41  5447.7  262.77  5462.7  262.99  5480.3  265.01
  5485.6  264.76  5535.9  267.56  5551.0  267.69  5616.4  271.83  5703.3  275.22
#Mann=3,-1,0
  4523.3     0.1       0  5139.9    0.07       0  5145.9     0.1       0
Bank Sta=5139.9,5145.9
Exp/Cntr=0.3,0.1

Type RM Length L Ch R = 1,3230,394,394,394
BEGIN DESCRIPTION:
UNT047 IN SPCR 2.0
END DESCRIPTION:
XS GIS Cut Line= 3
      2220021.15     13311953.28      2220282.23     13311774.65
      2220756.01     13310621.09
#Sta/Elev= 30
  4238.6  269.26  4348.5  265.71  4355.6  266.42  4363.4  265.18  4628.2  255.92
  4634.4  254.88  4717.1  251.67  4877.2  247.01  4930.9  247.39  4954.5  246.33
  4973.1  247.41  4995.8  246.33  4999.4  244.86  5002.2  244.36  5005.4  244.86
  5007.9  246.08  5026.4  247.63  5085.2  247.10  5168.8  248.17  5239.8  247.50
  5287.7  245.59  5317.1  247.49  5429.2  250.14  5554.5  256.46  5559.9  255.79
  5583.9  256.54  5622.8  259.48  5655.2  260.56  5661.2  261.65  5802.0  265.98
#Mann=3,-1,0
  4238.6     0.1       0  4999.4    0.07       0  5005.4     0.1       0
Bank Sta=4999.4,5005.4
Exp/Cntr=0.3,0.1

Type RM Length L Ch R = 1,2836,536,536,536
BEGIN DESCRIPTION:
Mapping XS dc12c81a
END DESCRIPTION:
XS GIS Cut Line= 4
      2220131.11     13311967.03      2220515.84     13311884.58
      2221044.89     13311183.76      2221031.15     13310867.72
#Sta/Elev= 30
  4237.9  265.73  4439.6  260.33  4498.2  258.64  4503.3  261.76  4520.8  257.47
  4540.6  257.00  4559.0  256.73  4648.8  253.80  4731.1  250.36  4818.5  247.27
  4852.1  245.86  4916.7  243.87  4973.1  244.15  4988.2  242.87  5023.9  244.09
  5094.0  243.87  5157.9  243.58  5167.3  244.16  5206.1  241.75  5208.9  241.25
  5212.1  241.75  5215.0  242.08  5259.1  244.80  5327.7  247.15  5335.9  247.59
  5402.7  249.58  5423.5  251.37  5555.4  253.21  5646.5  256.01  5825.8  259.35
#Mann=17,-1,0
  4237.9     0.1       0  4439.6    0.08       0  4540.6    0.05       0
  4559.0    0.08       0  4648.8    0.05       0  4731.1    0.08       0
  4818.5    0.05       0  4852.1    0.08       0  4973.1     0.1       0
  4988.2    0.08       0  5094.0     0.1       0  5157.9    0.08       0
  5206.1    0.07       0  5212.1    0.08       0  5215.0     0.1       0
  5327.7    0.08       0  5335.9     0.1       0
Bank Sta=5206.1,5212.1
Exp/Cntr=0.3,0.1

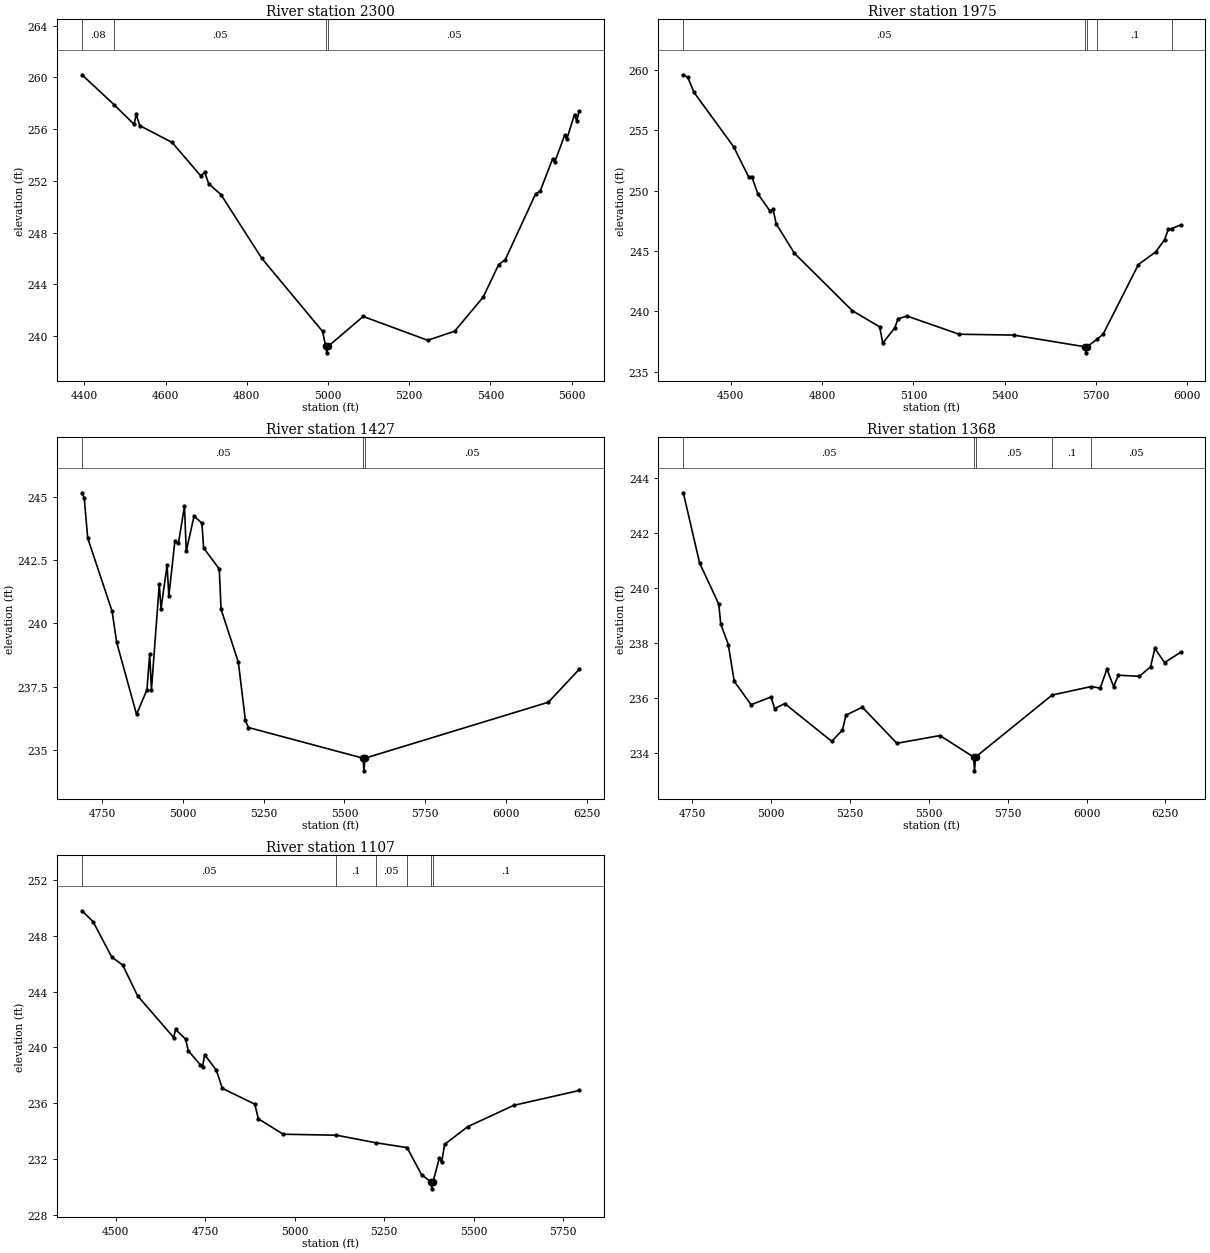
Type RM Length L Ch R = 1,2300,325,325,325
BEGIN DESCRIPTION:
Mapping XS d429559f
END DESCRIPTION:
XS GIS Cut Line= 3
      2220245.83     13312057.40      2221100.00     13312020.94
      2221235.42     13311677.20
#Sta/Elev= 30
  4394.2  260.20  4472.9  257.90  4522.7  256.37  4527.7  257.15  4536.2  256.28
  4616.3  254.97  4686.4  252.40  4696.4  252.66  4706.4  251.77  4736.4  250.95
  4836.5  246.04  4986.6  240.38  4994.4  239.22  4997.2  238.72  5000.4  239.22
  5086.7  241.53  5245.5  239.69  5311.9  240.39  5382.5  243.04  5420.2  245.54
  5436.3  245.90  5511.5  251.02  5522.2  251.19  5552.9  253.69  5558.3  253.46
  5582.7  255.52  5588.0  255.23  5607.0  257.13  5612.4  256.64  5618.6  257.40
#Mann=4,-1,0
  4394.2    0.08       0  4472.9    0.05       0  4994.4    0.03       0
  5000.4    0.05       0
Bank Sta=4994.4,5000.4
Exp/Cntr=0.3,0.1

Type RM Length L Ch R = 1,1975,548,548,548
BEGIN DESCRIPTION:
Mapping XS 65420327
END DESCRIPTION:
XS GIS Cut Line= 3
      2220192.87     13312358.67      2221086.12     13312351.80
      2221690.75     13311925.81
#Sta/Elev= 30
  4344.3  259.58  4359.2  259.36  4379.2  258.13  4509.2  253.64  4559.2  251.11
  4569.2  251.15  4589.2  249.72  4629.2  248.30  4639.2  248.44  4649.2  247.25
  4709.2  244.81  4899.2  240.06  4989.2  238.72  4999.2  237.37  5039.2  238.65
  5049.2  239.39  5079.2  239.61  5250.2  238.11  5428.8  238.04  5663.6  237.07
  5666.3  236.57  5669.6  237.07  5703.1  237.69  5723.2  238.13  5838.9  243.88
  5895.6  244.92  5924.6  245.92  5937.4  246.82  5947.6  246.85  5977.2  247.15
#Mann=5,-1,0
  4344.3    0.05       0  5663.6    0.03       0  5669.6    0.05       0
  5703.1     0.1       0  5947.6    0.05       0
Bank Sta=5663.6,5669.6
Exp/Cntr=0.3,0.1

Type RM Length L Ch R = 1,1427,59,59,59
BEGIN DESCRIPTION:
Mapping XS a33d9ec6
END DESCRIPTION:
XS GIS Cut Line= 3
      2220441.19     13312752.73      2220876.05     13312927.19
      2221797.05     13312384.78
#Sta/Elev= 30
  4688.4  245.16  4695.4  244.95  4706.2  243.37  4781.6  240.48  4795.6  239.26
  4857.1  236.41  4889.4  237.38  4897.8  238.79  4903.2  237.38  4927.4  241.54
  4932.8  240.59  4951.6  242.30  4957.0  241.08  4975.6  243.24  4986.6  243.16
  5005.4  244.63  5010.8  242.85  5035.0  244.24  5059.2  243.96  5064.6  242.98
  5113.0  242.15  5118.4  240.56  5171.9  238.47  5193.7  236.17  5203.2  235.89
  5557.4  234.68  5560.2  234.18  5563.4  234.68  6130.5  236.89  6225.8  238.19
#Mann=3,-1,0
  4688.4    0.05       0  5557.4    0.03       0  5563.4    0.05       0
Bank Sta=5557.4,5563.4
Exp/Cntr=0.3,0.1

Type RM Length L Ch R = 1,1368,261,261,261
BEGIN DESCRIPTION:
Mapping XS f1f5050f
END DESCRIPTION:
XS GIS Cut Line= 3
      2220446.35     13312823.02      2220915.11     13312997.50
      2221828.29     13312426.46
#Sta/Elev= 30
  4721.0  243.46  4772.7  240.91  4833.4  239.42  4839.8  238.70  4863.7  237.95
  4882.5  236.62  4935.9  235.77  4999.4  236.05  5010.6  235.63  5042.6  235.81
  5191.9  234.44  5225.7  234.85  5236.9  235.39  5288.8  235.68  5398.4  234.37
  5535.2  234.65  5641.9  233.87  5644.6  233.37  5647.9  233.87  5890.8  236.12
  6015.3  236.43  6043.4  236.37  6064.6  237.06  6085.8  236.43  6101.2  236.84
  6167.8  236.80  6203.2  237.15  6216.7  237.81  6247.4  237.30  6298.2  237.67
#Mann=5,-1,0
  4721.0    0.05       0  5641.9    0.03       0  5647.9    0.05       0
  5890.8     0.1       0  6015.3    0.05       0
Bank Sta=5641.9,5647.9
Exp/Cntr=0.3,0.1

Type RM Length L Ch R = 1,1107,0,0,0
BEGIN DESCRIPTION:
UNT047 IN SPCR 1.0
END DESCRIPTION:
XS GIS Cut Line= 4
      2220307.44     13313016.72      2220668.58     13313110.48
      2221099.13     13313068.81      2221563.60     13312715.26
#Sta/Elev= 30
  4405.6  249.81  4436.9  249.02  4488.5  246.50  4519.5  245.91  4560.9  243.71
  4661.9  240.71  4667.1  241.29  4695.2  240.60  4702.5  239.77  4736.5  238.75
  4743.0  238.63  4748.2  239.48  4780.8  238.38  4797.9  237.06  4888.4  235.93
  4898.4  234.88  4967.9  233.77  5116.6  233.70  5226.1  233.16  5314.1  232.81
  5354.4  230.87  5380.5  230.35  5383.3  229.85  5386.5  230.35  5404.3  232.07
  5410.6  231.76  5418.9  233.04  5483.3  234.31  5611.7  235.84  5795.0  236.91
#Mann=6,-1,0
  4405.6    0.05       0  5116.6     0.1       0  5226.1    0.05       0
  5314.1     0.1       0  5380.5    0.03       0  5386.5     0.1       0
Bank Sta=5380.5,5386.5
Exp/Cntr=0.3,0.1

Chan Stop Cuts=-1