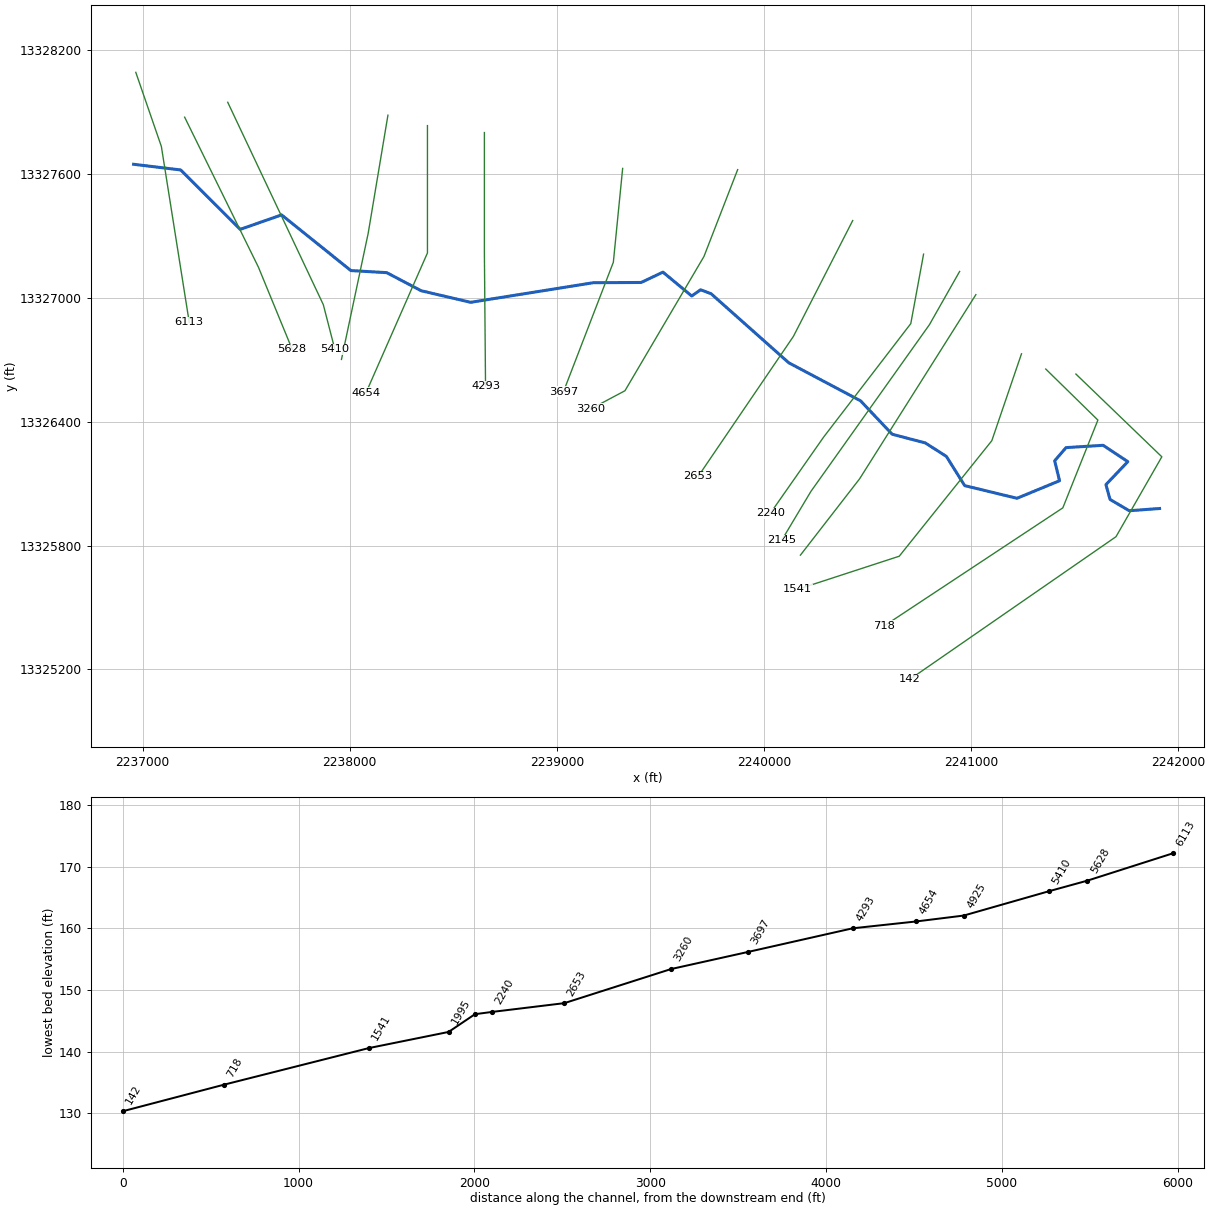
--- UNT049 IN SPCR.prj (project) ---

Proj Title=UNT049 IN SPCR Base Level Engineering
Current Plan=p01
Default Exp/Contr=0.3,0.1
English Units
Geom File=g01
Flow File=f01
Plan File=p01
BEGIN DESCRIPTION:
UNT049 IN SPCR
END DESCRIPTION:

--- UNT049 IN SPCR.p01 (plan) ---

Plan Title=Multiple Run
Short Identifier=Multiple
Geom File=g01
Flow File=f01
Subcritical Flow
K Sum by GR= 0
Std Step Tol= 0.01
Critical Tol= 0.01
Num of Std Step Trials= 20
Max Error Tol= 0.3
Flow Tol Ratio= 0.001
Split Flow NTrial= 30
Split Flow Tol= 0.02
Split Flow Ratio= 0.02
Log Output Level= 0
Friction Slope Method= 1
Unsteady Friction Slope Method= 2
Unsteady Bridges Friction Slope Method= 1
Parabolic Critical Depth
Global Vel Dist=  1 , 1 , 1
Global Log Level= 0
CheckData=True
Encroach Param= -1, 0, 0, 0
BEGIN DESCRIPTION:
Multiple Run
END DESCRIPTION:

--- UNT049 IN SPCR.f01 (steady flow) ---

Flow Title=Multiple
Number of Profiles=7
Profile Names=10-year,25-year,50-year,1pct_min,100-year,1pct_plu,500-year
River Rch & RM= UNT049 IN SPCR,Reach-1,6113
     324     460     576     531     719     972    1133
Boundary for River Rch & Prof#=UNT049 IN SPCR,Reach-1,1
Up Type=0
Dn Type=3
Dn Slope=0.005
Boundary for River Rch & Prof#=UNT049 IN SPCR,Reach-1,2
Up Type=0
Dn Type=3
Dn Slope=0.005
Boundary for River Rch & Prof#=UNT049 IN SPCR,Reach-1,3
Up Type=0
Dn Type=3
Dn Slope=0.005
Boundary for River Rch & Prof#=UNT049 IN SPCR,Reach-1,4
Up Type=0
Dn Type=3
Dn Slope=0.005
Boundary for River Rch & Prof#=UNT049 IN SPCR,Reach-1,5
Up Type=0
Dn Type=3
Dn Slope=0.005
Boundary for River Rch & Prof#=UNT049 IN SPCR,Reach-1,6
Up Type=0
Dn Type=3
Dn Slope=0.005
Boundary for River Rch & Prof#=UNT049 IN SPCR,Reach-1,7
Up Type=0
Dn Type=3
Dn Slope=0.005

--- UNT049 IN SPCR.g01 (geometry) ---

Geom Title=Existing Conditions

River Reach=UNT049 IN SPCR,Reach-1
Reach XY= 30
      2236955.90     13327647.69      2237183.31     13327620.13
      2237470.73     13327332.25      2237670.58     13327402.35
      2238005.23     13327132.56      2238178.28     13327122.46
      2238344.57     13327034.82      2238583.55     13326978.76
      2239176.12     13327073.76      2239407.02     13327074.90
      2239512.02     13327125.01      2239650.85     13327009.44
      2239693.82     13327039.39      2239744.17     13327020.73
      2240119.60     13326685.66      2240465.95     13326501.63
      2240618.75     13326339.47      2240778.59     13326297.47
      2240880.67     13326232.02      2240969.00     13326090.50
      2241221.63     13326029.03      2241427.09     13326114.14
      2241403.44     13326210.62      2241458.41     13326274.60
      2241637.58     13326285.80      2241756.73     13326206.59
      2241651.03     13326095.26      2241670.92     13326023.43
      2241763.35     13325968.78      2241910.04     13325979.49

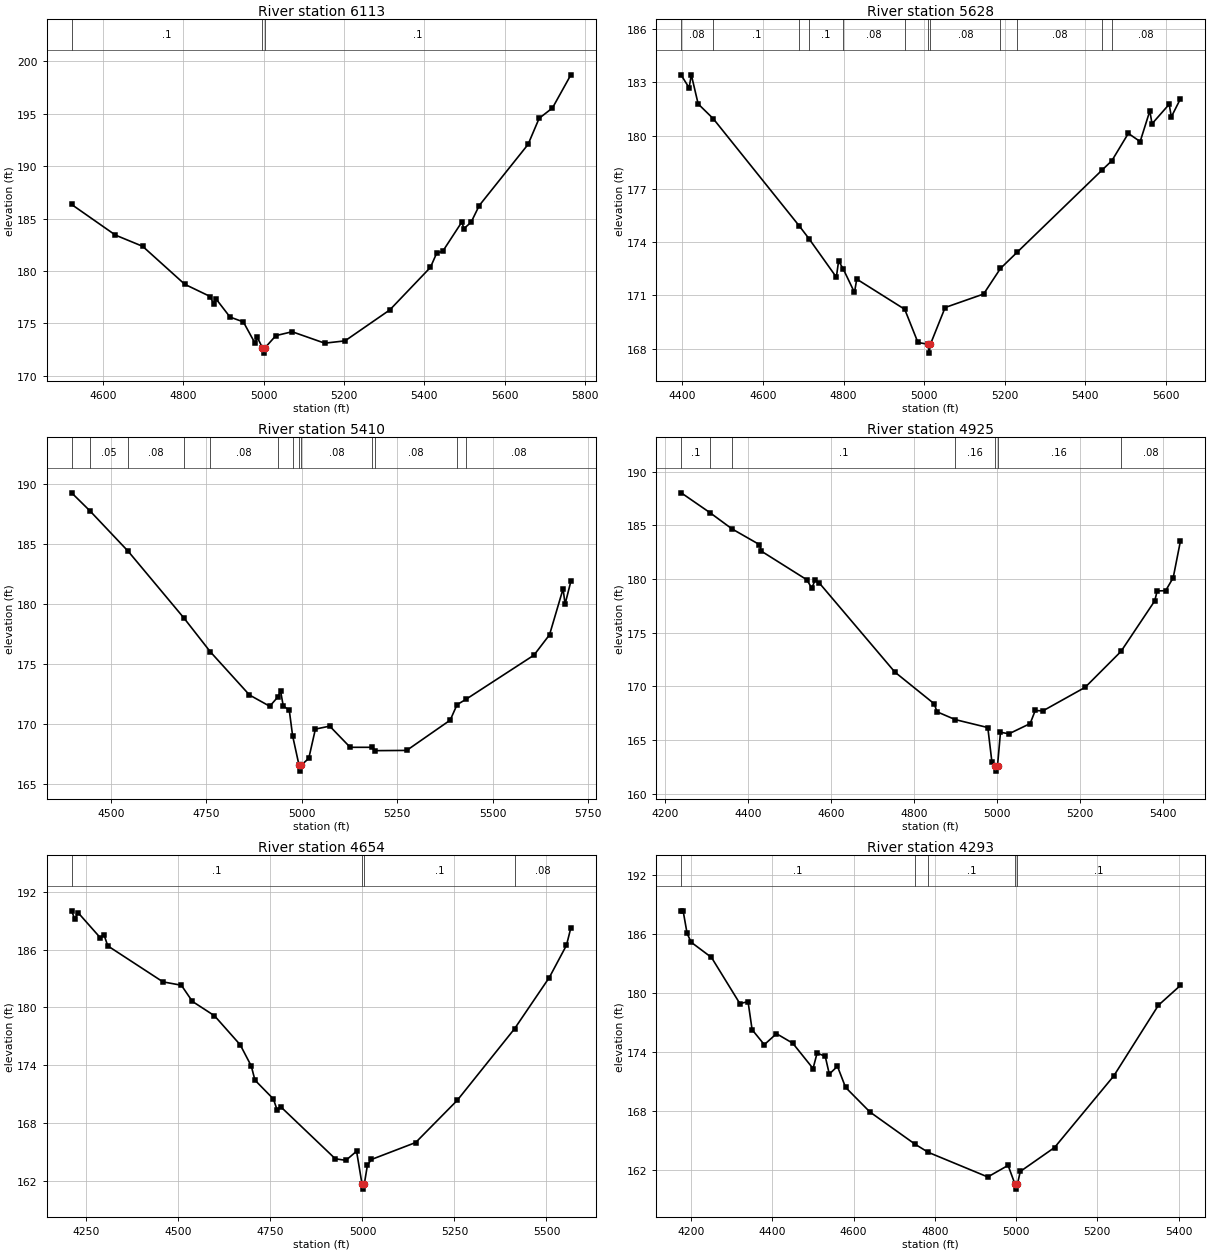
Type RM Length L Ch R = 1,6113,485,485,485
BEGIN DESCRIPTION:
UNT049 IN SPCR 12.0
END DESCRIPTION:
XS GIS Cut Line= 3
      2236966.66     13328093.09      2237090.08     13327734.06
      2237224.69     13326881.57
#Sta/Elev= 30
  4521.9  186.35  4630.9  183.43  4698.7  182.36  4803.4  178.74  4866.9  177.57
  4875.5  176.83  4880.8  177.37  4916.2  175.61  4949.3  175.15  4978.6  173.10
  4983.7  173.70  4997.0  172.67  4999.7  172.17  5003.0  172.67  5030.3  173.84
  5070.8  174.21  5151.8  173.12  5202.4  173.34  5313.8  176.29  5415.0  180.35
  5430.8  181.73  5445.4  181.87  5493.2  184.68  5498.3  184.04  5516.3  184.66
  5536.5  186.25  5658.0  192.08  5685.6  194.57  5718.8  195.56  5764.6  198.72
#Mann=3,-1,0
  4521.9     0.1       0  4997.0    0.07       0  5003.0     0.1       0
Bank Sta=4997,5003
Exp/Cntr=0.3,0.1

Type RM Length L Ch R = 1,5628,218,218,218
BEGIN DESCRIPTION:
Mapping XS 3defb85d
END DESCRIPTION:
XS GIS Cut Line= 3
      2237202.43     13327876.00      2237558.90     13327148.65
      2237721.49     13326751.44
#Sta/Elev= 30
  4397.1  183.41  4416.7  182.70  4422.2  183.43  4439.2  181.79  4476.6  180.96
  4690.7  174.90  4714.2  174.20  4782.2  172.03  4787.8  172.94  4799.1  172.50
  4827.2  171.17  4832.8  171.92  4951.9  170.22  4984.7  168.35  5009.7  168.25
  5012.5  167.75  5015.7  168.25  5052.2  170.32  5147.7  171.08  5189.5  172.52
  5231.7  173.45  5442.5  178.08  5466.0  178.59  5506.9  180.13  5536.3  179.67
  5560.3  181.40  5565.7  180.67  5608.3  181.77  5613.7  181.06  5636.3  182.08
#Mann=12,-1,0
  4397.1    0.08       0  4476.6     0.1       0  4690.7    0.08       0
  4714.2     0.1       0  4799.1    0.08       0  4951.9     0.1       0
  5009.7    0.07       0  5015.7    0.08       0  5189.5     0.1       0
  5231.7    0.08       0  5442.5     0.1       0  5466.0    0.08       0
Bank Sta=5009.7,5015.7
Exp/Cntr=0.3,0.1

Type RM Length L Ch R = 1,5410,485,485,485
BEGIN DESCRIPTION:
UNT049 IN SPCR 11.0
END DESCRIPTION:
XS GIS Cut Line= 3
      2237410.53     13327948.12      2237872.08     13326967.33
      2237927.60     13326751.41
#Sta/Elev= 30
  4397.5  189.29  4445.2  187.79  4545.7  184.40  4691.5  178.83  4760.8  176.00
  4863.1  172.40  4916.1  171.46  4937.8  172.25  4944.4  172.75  4951.5  171.48
  4967.2  171.14  4976.0  168.99  4992.7  166.54  4995.4  166.04  4998.7  166.54
  5018.3  167.11  5035.6  169.55  5073.1  169.80  5126.7  168.03  5184.0  168.03
  5191.2  167.75  5274.6  167.77  5388.5  170.30  5406.4  171.59  5430.3  172.05
  5607.8  175.73  5648.5  177.43  5684.0  181.27  5689.2  179.99  5704.4  181.90
#Mann=13,-1,0
  4397.5     0.1       0  4445.2    0.05       0  4545.7    0.08       0
  4691.5    0.05       0  4760.8    0.08       0  4937.8    0.05       0
  4976.0    0.08       0  4992.7    0.07       0  4998.7    0.08       0
  5184.0    0.16       0  5191.2    0.08       0  5406.4     0.1       0
  5430.3    0.08       0
Bank Sta=4992.7,4998.7
Exp/Cntr=0.3,0.1

Type RM Length L Ch R = 1,4925,271,271,271
BEGIN DESCRIPTION:
UNT049 IN SPCR 10.0
END DESCRIPTION:
XS GIS Cut Line= 3
      2238184.13     13327885.58      2238088.74     13327313.27
      2237959.73     13326701.84
#Sta/Elev= 30
  4238.0  188.02  4307.1  186.18  4360.6  184.66  4426.7  183.20  4431.7  182.58
  4540.8  179.93  4553.4  179.14  4561.1  179.89  4571.3  179.62  4753.7  171.32
  4848.8  168.36  4855.4  167.62  4899.5  166.89  4978.1  166.15  4987.9  162.97
  4995.5  162.59  4998.3  162.09  5001.5  162.59  5008.7  165.71  5029.2  165.57
  5080.3  166.52  5092.6  167.74  5110.9  167.70  5213.1  169.90  5299.5  173.24
  5381.0  177.95  5386.9  178.88  5407.3  178.90  5425.6  180.11  5443.1  183.54
#Mann=7,-1,0
  4238.0     0.1       0  4307.1    0.05       0  4360.6     0.1       0
  4899.5    0.16       0  4995.5    0.07       0  5001.5    0.16       0
  5299.5    0.08       0
Bank Sta=4995.5,5001.5
Exp/Cntr=0.3,0.1

Type RM Length L Ch R = 1,4654,361,361,361
BEGIN DESCRIPTION:
UNT049 IN SPCR 9.0
END DESCRIPTION:
XS GIS Cut Line= 3
      2238374.88     13327835.07      2238374.88     13327217.89
      2238078.13     13326540.41
#Sta/Elev= 30
  4209.6  190.04  4217.8  189.21  4227.8  189.82  4287.8  187.23  4297.8  187.53
  4307.8  186.40  4457.8  182.66  4507.8  182.31  4537.8  180.63  4597.8  179.14
  4667.8  176.12  4697.8  173.92  4707.8  172.45  4757.8  170.50  4767.8  169.39
  4777.8  169.69  4926.2  164.28  4955.1  164.12  4984.0  165.07  4998.9  161.63
  5001.6  161.13  5004.9  161.63  5013.5  163.63  5024.4  164.21  5144.5  165.97
  5257.5  170.35  5413.3  177.79  5507.7  183.11  5554.4  186.46  5566.4  188.28
#Mann=4,-1,0
  4209.6     0.1       0  4998.9    0.07       0  5004.9     0.1       0
  5413.3    0.08       0
Bank Sta=4998.9,5004.9
Exp/Cntr=0.3,0.1

Type RM Length L Ch R = 1,4293,596,596,596
BEGIN DESCRIPTION:
UNT049 IN SPCR 8.0
END DESCRIPTION:
XS GIS Cut Line= 3
      2238649.79     13327801.36      2238649.79     13327223.50
      2238655.40     13326572.68
#Sta/Elev= 30
  4175.9  188.38  4180.6  188.38  4190.4  186.08  4200.4  185.18  4250.4  183.63
  4320.4  178.92  4340.4  179.13  4350.4  176.27  4380.4  174.74  4410.4  175.86
  4450.4  174.89  4500.4  172.31  4510.4  173.89  4530.4  173.55  4540.4  171.74
  4560.4  172.54  4580.4  170.39  4640.4  167.88  4751.4  164.60  4784.0  163.77
  4930.4  161.26  4980.4  162.44  4997.4  160.52  5000.2  160.02  5003.4  160.52
  5010.4  161.82  5094.7  164.26  5240.4  171.55  5350.4  178.76  5404.6  180.78
#Mann=5,-1,0
  4175.9     0.1       0  4751.4    0.16       0  4784.0     0.1       0
  4997.4    0.07       0  5003.4     0.1       0
Bank Sta=4997.4,5003.4
Exp/Cntr=0.3,0.1

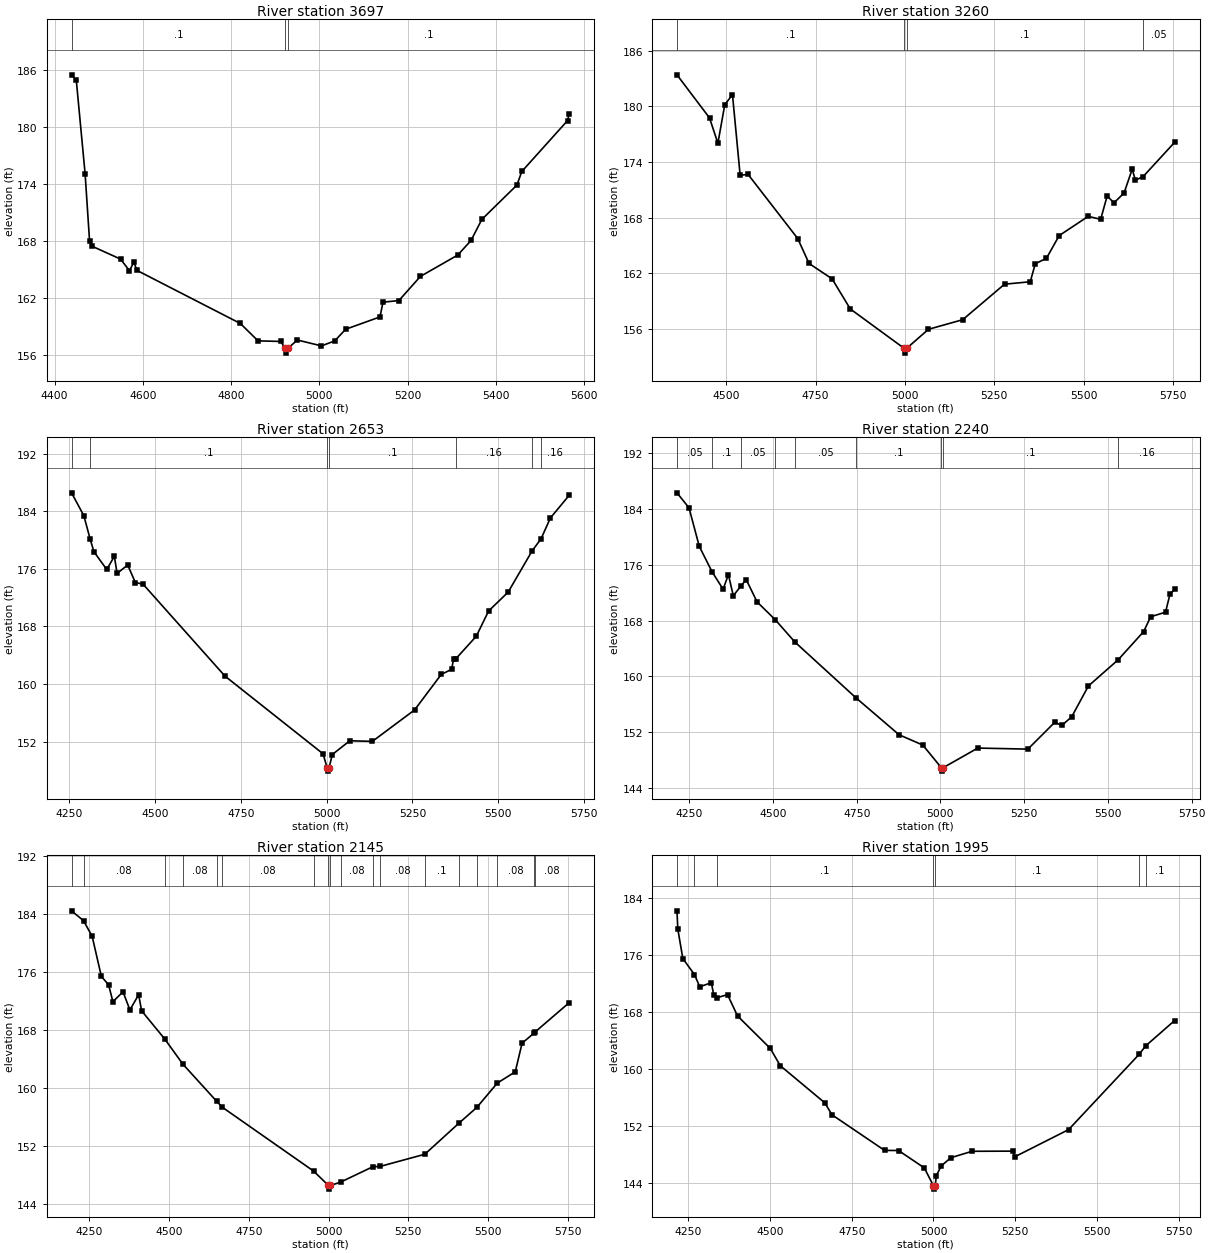
Type RM Length L Ch R = 1,3697,437,437,437
BEGIN DESCRIPTION:
UNT049 IN SPCR 7.0
END DESCRIPTION:
XS GIS Cut Line= 3
      2239317.43     13327627.46      2239272.55     13327173.01
      2239032.00     13326546.46
#Sta/Elev= 30
  4438.5  185.46  4449.2  184.91  4469.3  175.01  4479.3  167.99  4485.4  167.42
  4549.6  166.07  4569.7  164.85  4579.8  165.76  4586.5  164.89  4821.0  159.30
  4861.1  157.47  4912.5  157.41  4922.6  156.68  4925.3  156.18  4928.6  156.68
  4950.2  157.56  5004.9  156.94  5034.9  157.47  5059.6  158.69  5137.4  159.99
  5144.3  161.54  5180.3  161.71  5229.0  164.25  5313.7  166.50  5343.7  168.03
  5368.3  170.25  5447.7  173.86  5458.8  175.29  5562.4  180.64  5566.3  181.37
#Mann=3,-1,0
  4438.5     0.1       0  4922.6    0.07       0  4928.6     0.1       0
Bank Sta=4922.6,4928.6
Exp/Cntr=0.3,0.1

Type RM Length L Ch R = 1,3260,607,607,607
BEGIN DESCRIPTION:
UNT049 IN SPCR 6.0
END DESCRIPTION:
XS GIS Cut Line= 4
      2239872.85     13327621.82      2239710.16     13327201.06
      2239328.65     13326550.25      2239162.77     13326461.78
#Sta/Elev= 30
  4361.7  183.40  4452.8  178.76  4476.3  176.03  4495.5  180.17  4517.1  181.27
  4538.6  172.58  4560.8  172.67  4699.8  165.76  4731.6  163.07  4795.9  161.42
  4847.0  158.17  4998.4  153.91  5001.2  153.41  5004.4  153.91  5065.9  155.98
  5161.7  157.01  5278.9  160.84  5350.9  161.10  5364.9  163.04  5396.2  163.63
  5432.0  166.08  5513.2  168.15  5548.0  167.83  5566.3  170.35  5585.2  169.60
  5613.6  170.67  5636.3  173.23  5645.4  172.04  5667.1  172.44  5755.2  176.13
#Mann=4,-1,0
  4361.7     0.1       0  4998.4    0.07       0  5004.4     0.1       0
  5667.1    0.05       0
Bank Sta=4998.4,5004.4
Exp/Cntr=0.3,0.1

Type RM Length L Ch R = 1,2653,413,413,413
BEGIN DESCRIPTION:
UNT049 IN SPCR 5.0
END DESCRIPTION:
XS GIS Cut Line= 3
      2240428.32     13327375.02      2240142.17     13326813.94
      2239682.39     13326135.49
#Sta/Elev= 30
  4257.4  186.58  4293.2  183.40  4311.7  180.12  4322.7  178.38  4359.9  175.92
  4382.1  177.76  4390.0  175.37  4420.9  176.55  4443.2  174.10  4465.4  173.89
  4704.3  161.09  4989.8  150.29  5001.5  148.38  5004.3  147.88  5007.5  148.38
  5016.8  150.19  5067.7  152.10  5133.6  152.02  5256.4  156.39  5334.3  161.34
  5364.2  162.03  5370.2  163.52  5376.5  163.50  5436.1  166.64  5472.0  170.15
  5529.0  172.78  5599.1  178.54  5624.7  180.18  5651.8  183.08  5706.8  186.24
#Mann=7,-1,0
  4257.4    0.05       0  4311.7     0.1       0  5001.5    0.07       0
  5007.5     0.1       0  5376.5    0.16       0  5599.1     0.1       0
  5624.7    0.16       0
Bank Sta=5001.5,5007.5
Exp/Cntr=0.3,0.1

Type RM Length L Ch R = 1,2240,95,95,95
BEGIN DESCRIPTION:
Mapping XS 7addbb1a
END DESCRIPTION:
XS GIS Cut Line= 4
      2240770.53     13327212.26      2240708.82     13326875.66
      2240288.04     13326325.83      2240029.97     13325955.56
#Sta/Elev= 30
  4213.4  186.28  4249.4  184.13  4279.9  178.63  4318.4  174.96  4351.1  172.49
  4367.0  174.56  4381.6  171.55  4405.3  173.00  4420.1  173.86  4452.7  170.66
  4506.2  168.15  4565.4  164.93  4747.8  156.94  4876.7  151.65  4947.4  150.18
  5002.5  146.95  5005.3  146.45  5008.5  146.95  5111.5  149.75  5261.1  149.60
  5341.4  153.44  5362.4  152.99  5392.0  154.23  5441.8  158.64  5530.5  162.38
  5606.7  166.42  5627.6  168.54  5672.1  169.20  5685.5  171.81  5699.3  172.46
#Mann=9,-1,0
  4213.4    0.05       0  4318.4     0.1       0  4405.3    0.05       0
  4506.2     0.1       0  4565.4    0.05       0  4747.8     0.1       0
  5002.5    0.07       0  5008.5     0.1       0  5530.5    0.16       0
Bank Sta=5002.5,5008.5
Exp/Cntr=0.3,0.1

Type RM Length L Ch R = 1,2145,150,150,150
BEGIN DESCRIPTION:
Mapping XS a00d76ec
END DESCRIPTION:
XS GIS Cut Line= 4
      2240944.48     13327128.16      2240798.59     13326870.05
      2240226.32     13326062.14      2240086.04     13325826.47
#Sta/Elev= 30
  4193.9  184.40  4231.5  183.04  4258.5  180.89  4287.3  175.39  4310.3  174.19
  4323.5  171.89  4355.3  173.25  4376.9  170.76  4404.3  172.85  4413.6  170.64
  4485.7  166.78  4543.1  163.29  4649.4  158.16  4666.7  157.36  4953.1  148.57
  4999.6  146.59  5002.3  146.09  5005.6  146.59  5037.5  147.05  5138.6  149.17
  5161.1  149.21  5301.7  150.89  5408.3  155.15  5464.7  157.33  5529.2  160.69
  5585.4  162.24  5606.8  166.18  5645.7  167.62  5646.2  167.67  5754.7  171.76
#Mann=18,-1,0
  4193.9    0.05       0  4231.5    0.08       0  4485.7     0.1       0
  4543.1    0.08       0  4649.4    0.05       0  4666.7    0.08       0
  4953.1     0.1       0  4999.6    0.07       0  5005.6     0.1       0
  5037.5    0.08       0  5138.6     0.1       0  5161.1    0.08       0
  5301.7     0.1       0  5408.3    0.08       0  5464.7     0.1       0
  5529.2    0.08       0  5645.7    0.16       0  5646.2    0.08       0
Bank Sta=4999.6,5005.6
Exp/Cntr=0.3,0.1

Type RM Length L Ch R = 1,1995,454,454,454
BEGIN DESCRIPTION:
Mapping XS 81f5f59d
END DESCRIPTION:
XS GIS Cut Line= 3
      2241023.00     13327015.90      2240461.96     13326123.86
      2240175.81     13325753.54
#Sta/Elev= 30
  4215.7  182.26  4218.3  179.70  4233.6  175.57  4269.3  173.31  4285.4  171.60
  4320.9  172.18  4327.9  170.50  4338.3  170.07  4370.3  170.50  4400.9  167.51
  4501.0  162.96  4531.6  160.53  4668.2  155.30  4689.4  153.65  4850.7  148.64
  4893.1  148.63  4972.0  146.19  4999.6  143.71  5002.4  143.21  5005.6  143.71
  5008.5  145.08  5023.8  146.47  5053.3  147.62  5118.1  148.52  5242.3  148.54
  5248.8  147.75  5413.2  151.56  5628.6  162.11  5648.9  163.31  5737.5  166.87
#Mann=7,-1,0
  4215.7    0.05       0  4269.3    0.08       0  4338.3     0.1       0
  4999.6    0.07       0  5005.6     0.1       0  5628.6    0.08       0
  5648.9     0.1       0
Bank Sta=4999.6,5005.6
Exp/Cntr=0.3,0.1

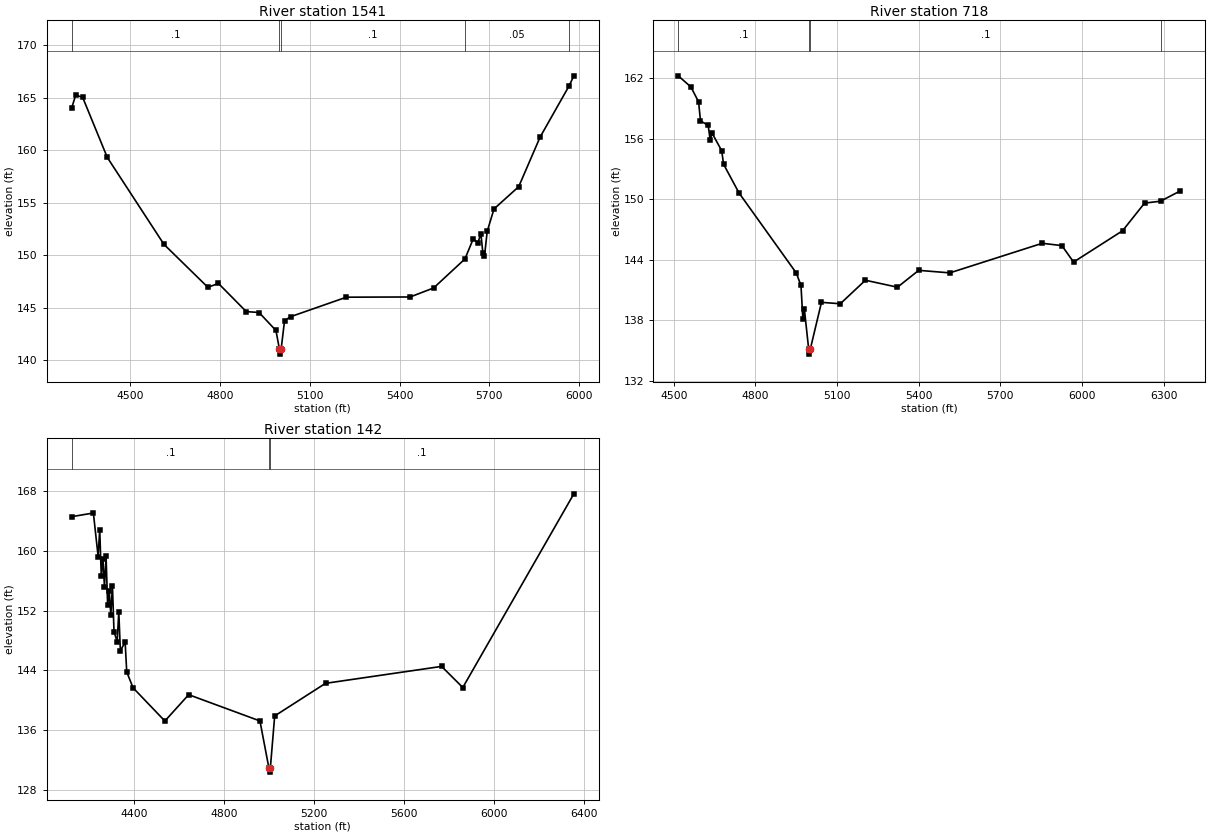
Type RM Length L Ch R = 1,1541,823,823,823
BEGIN DESCRIPTION:
UNT049 IN SPCR 3.0
END DESCRIPTION:
XS GIS Cut Line= 4
      2241243.30     13326729.27      2241100.06     13326308.22
      2240653.01     13325748.33      2240162.64     13325587.77
#Sta/Elev= 30
  4305.1  164.05  4318.2  165.24  4341.3  165.04  4423.8  159.31  4613.0  151.04
  4759.8  146.95  4795.0  147.32  4887.9  144.64  4930.7  144.55  4987.2  142.84
  4998.6  141.09  5001.3  140.59  5004.6  141.09  5016.0  143.79  5036.8  144.16
  5222.5  146.01  5435.5  146.03  5514.0  146.89  5618.5  149.65  5646.6  151.59
  5661.3  151.17  5671.8  152.05  5678.5  150.18  5683.8  149.92  5692.9  152.28
  5715.6  154.41  5798.1  156.53  5869.6  161.25  5966.4  166.12  5982.3  167.08
#Mann=5,-1,0
  4305.1     0.1       0  4998.6    0.07       0  5004.6     0.1       0
  5618.5    0.05       0  5966.4     0.1       0
Bank Sta=4998.6,5004.6
Exp/Cntr=0.3,0.1

Type RM Length L Ch R = 1,718,576,576,576
BEGIN DESCRIPTION:
UNT049 IN SPCR 2.0
END DESCRIPTION:
XS GIS Cut Line= 4
      2241360.50     13326655.43      2241612.21     13326408.05
      2241442.94     13325982.70      2240580.78     13325410.82
#Sta/Elev= 30
  4516.1  162.23  4562.6  161.13  4590.9  159.65  4597.9  157.76  4626.2  157.33
  4633.4  155.88  4640.4  156.56  4675.8  154.81  4682.8  153.47  4739.4  150.63
  4949.9  142.70  4967.2  141.46  4974.2  138.13  4979.6  139.14  4995.5  135.16
  4998.2  134.66  5001.5  135.16  5042.5  139.79  5111.8  139.65  5204.0  141.98
  5321.9  141.29  5399.9  142.96  5514.2  142.71  5854.0  145.64  5926.2  145.41
  5969.1  143.78  6149.1  146.88  6230.0  149.62  6288.7  149.81  6361.4  150.83
#Mann=4,-1,0
  4516.1     0.1       0  4995.5    0.07       0  5001.5     0.1       0
  6288.7    0.05       0
Bank Sta=4995.5,5001.5
Exp/Cntr=0.3,0.1

Type RM Length L Ch R = 1,142,0,0,0
BEGIN DESCRIPTION:
UNT049 IN SPCR 1.0
END DESCRIPTION:
XS GIS Cut Line= 4
      2241506.09     13326631.10      2241920.92     13326230.10
      2241699.66     13325842.90      2240704.25     13325151.65
#Sta/Elev= 30
  4122.0  164.59  4218.2  165.08  4239.3  159.25  4246.4  162.86  4253.4  156.61
  4260.6  158.98  4267.5  155.17  4274.7  159.26  4281.7  152.69  4288.9  154.57
  4295.8  151.39  4303.0  155.32  4310.0  149.18  4324.1  147.83  4331.3  151.87
  4338.3  146.63  4359.6  147.77  4366.6  143.78  4394.9  141.65  4536.4  137.20
  4642.4  140.73  4959.6  137.21  4999.8  130.85  5002.5  130.35  5005.8  130.85
  5025.2  137.88  5251.4  142.25  5768.2  144.52  5862.5  141.69  6356.8  167.65
#Mann=3,-1,0
  4122.0     0.1       0  4999.8    0.07       0  5005.8     0.1       0
Bank Sta=4999.8,5005.8
Exp/Cntr=0.3,0.1

Chan Stop Cuts=-1