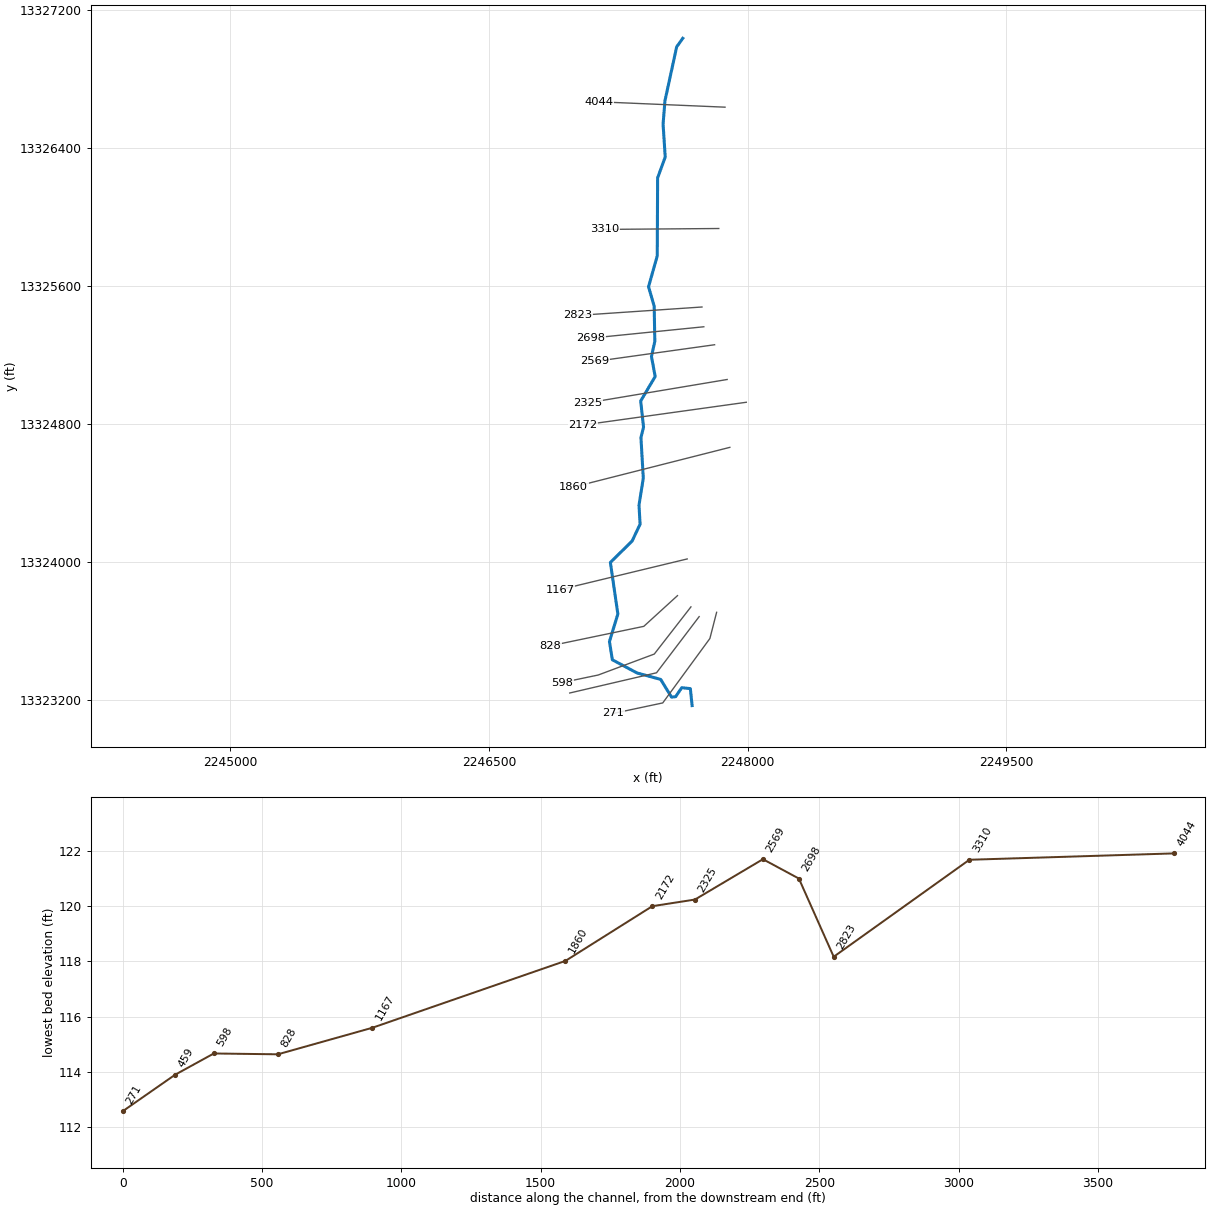
--- UNT050 IN SPCR.prj (project) ---

Proj Title=UNT050 IN SPCR Base Level Engineering
Current Plan=p01
Default Exp/Contr=0.3,0.1
English Units
Geom File=g01
Flow File=f01
Plan File=p01
BEGIN DESCRIPTION:
UNT050 IN SPCR
END DESCRIPTION:

--- UNT050 IN SPCR.p01 (plan) ---

Plan Title=Multiple Run
Short Identifier=Multiple
Geom File=g01
Flow File=f01
Subcritical Flow
K Sum by GR= 0
Std Step Tol= 0.01
Critical Tol= 0.01
Num of Std Step Trials= 20
Max Error Tol= 0.3
Flow Tol Ratio= 0.001
Split Flow NTrial= 30
Split Flow Tol= 0.02
Split Flow Ratio= 0.02
Log Output Level= 0
Friction Slope Method= 1
Unsteady Friction Slope Method= 2
Unsteady Bridges Friction Slope Method= 1
Parabolic Critical Depth
Global Vel Dist=  1 , 1 , 1
Global Log Level= 0
CheckData=True
Encroach Param= -1, 0, 0, 0
BEGIN DESCRIPTION:
Multiple Run
END DESCRIPTION:

--- UNT050 IN SPCR.f01 (steady flow) ---

Flow Title=Multiple
Number of Profiles=7
Profile Names=10-year,25-year,50-year,1pct_min,100-year,1pct_plu,500-year
River Rch & RM= UNT050 IN SPCR,Reach-1,4044
     179     244     296     266     359     486     534
River Rch & RM= UNT050 IN SPCR,Reach-1,3310
     266     369     455     412     558     754     851
Boundary for River Rch & Prof#=UNT050 IN SPCR,Reach-1,1
Up Type=0
Dn Type=3
Dn Slope=0.005
Boundary for River Rch & Prof#=UNT050 IN SPCR,Reach-1,2
Up Type=0
Dn Type=3
Dn Slope=0.005
Boundary for River Rch & Prof#=UNT050 IN SPCR,Reach-1,3
Up Type=0
Dn Type=3
Dn Slope=0.005
Boundary for River Rch & Prof#=UNT050 IN SPCR,Reach-1,4
Up Type=0
Dn Type=3
Dn Slope=0.005
Boundary for River Rch & Prof#=UNT050 IN SPCR,Reach-1,5
Up Type=0
Dn Type=3
Dn Slope=0.005
Boundary for River Rch & Prof#=UNT050 IN SPCR,Reach-1,6
Up Type=0
Dn Type=3
Dn Slope=0.005
Boundary for River Rch & Prof#=UNT050 IN SPCR,Reach-1,7
Up Type=0
Dn Type=3
Dn Slope=0.005

--- UNT050 IN SPCR.g01 (geometry) ---

Geom Title=Existing Conditions

River Reach=UNT050 IN SPCR,Reach-1
Reach XY= 30
      2247624.12     13327033.92      2247588.78     13326984.60
      2247520.82     13326671.94      2247509.97     13326536.53
      2247522.33     13326345.91      2247478.28     13326225.33
      2247476.11     13325773.07      2247425.59     13325594.34
      2247458.32     13325481.84      2247462.05     13325277.93
      2247442.52     13325190.26      2247464.22     13325073.94
      2247380.02     13324932.45      2247396.60     13324780.97
      2247381.50     13324720.03      2247395.16     13324485.02
      2247370.29     13324328.67      2247376.60     13324218.08
      2247330.12     13324120.35      2247204.17     13323996.69
      2247247.61     13323697.85      2247198.84     13323537.92
      2247215.77     13323432.45      2247358.48     13323356.23
      2247495.98     13323318.73      2247559.17     13323215.96
      2247582.78     13323218.73      2247618.20     13323270.82
      2247668.20     13323265.26      2247678.38     13323167.20

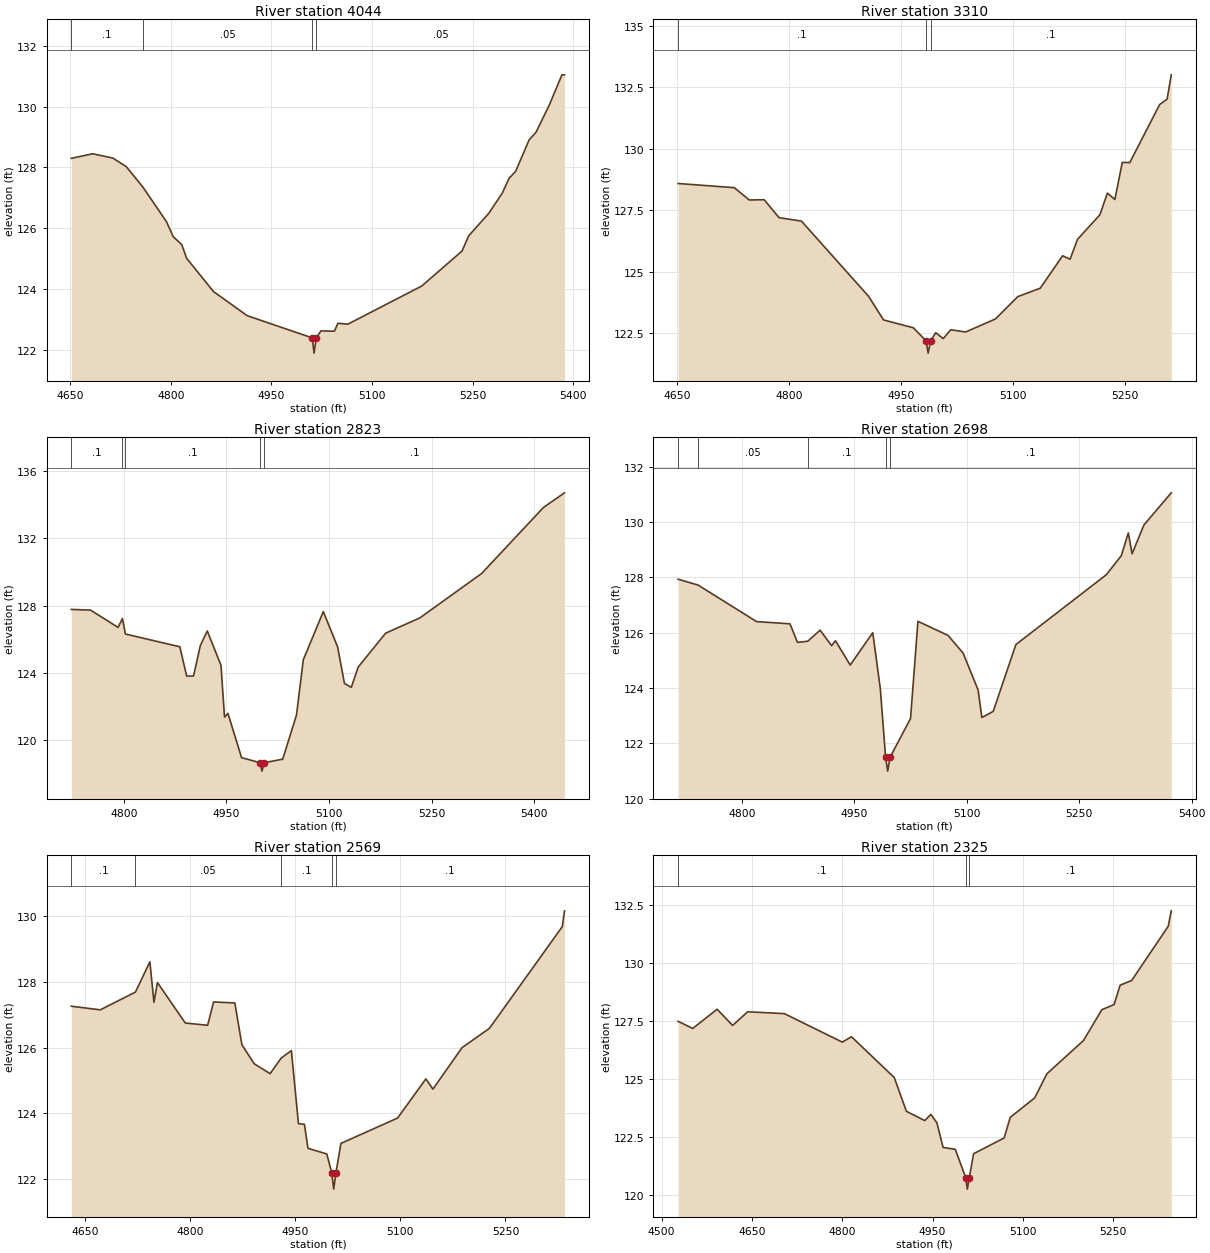
Type RM Length L Ch R = 1,4044,734,734,734
BEGIN DESCRIPTION:
UNT050 IN SPCR 3.0
END DESCRIPTION:
XS GIS Cut Line= 2
      2247869.47     13326634.96      2247135.13     13326666.20
#Sta/Elev= 30
  4651.9  128.30  4683.7  128.45  4713.7  128.31  4733.7  128.03  4758.8  127.35
  4793.8  126.22  4803.8  125.73  4816.5  125.47  4823.8  125.02  4863.8  123.93
  4913.9  123.14  5011.0  122.41  5013.7  121.91  5017.0  122.41  5024.0  122.64
  5044.0  122.63  5049.2  122.89  5064.0  122.86  5174.1  124.11  5234.2  125.26
  5244.2  125.76  5274.2  126.50  5294.2  127.16  5304.2  127.64  5314.2  127.88
  5334.3  128.91  5344.3  129.15  5364.3  130.05  5383.1  131.04  5386.9  131.04
#Mann=4,-1,0
  4651.9     0.1       0  4758.8    0.05       0  5011.0    0.03       0
  5017.0    0.05       0
Bank Sta=5011,5017
Exp/Cntr=0.3,0.1

Type RM Length L Ch R = 1,3310,487,487,487
BEGIN DESCRIPTION:
UNT050 IN SPCR 2.0
END DESCRIPTION:
XS GIS Cut Line= 2
      2247833.01     13325931.83      2247172.13     13325926.63
#Sta/Elev= 30
  4651.7  128.58  4727.0  128.41  4747.0  127.91  4767.0  127.92  4787.0  127.19
  4817.0  127.05  4907.0  123.99  4927.0  123.03  4967.0  122.71  4984.0  122.18
  4986.8  121.68  4990.0  122.18  4997.0  122.51  5007.0  122.27  5017.0  122.63
  5037.0  122.54  5077.0  123.07  5107.0  123.98  5137.0  124.32  5167.0  125.64
  5177.0  125.50  5187.0  126.31  5217.0  127.31  5227.0  128.19  5237.0  127.93
  5247.0  129.44  5257.0  129.43  5297.0  131.79  5307.0  132.01  5312.6  133.00
#Mann=3,-1,0
  4651.7     0.1       0  4984.0    0.07       0  4990.0     0.1       0
Bank Sta=4984,4990
Exp/Cntr=0.3,0.1

Type RM Length L Ch R = 1,2823,125,125,125
BEGIN DESCRIPTION:
Mapping XS d63ce02f
END DESCRIPTION:
XS GIS Cut Line= 2
      2247735.83     13325476.97      2247017.08     13325428.36
#Sta/Elev= 30
  4723.5  127.78  4751.7  127.74  4791.8  126.71  4798.1  127.24  4802.5  126.32
  4882.0  125.56  4892.0  123.82  4902.0  123.82  4912.0  125.64  4922.1  126.50
  4942.1  124.46  4947.3  121.38  4952.3  121.60  4972.2  118.97  4999.2  118.67
  5002.0  118.17  5005.2  118.67  5032.3  118.88  5052.4  121.50  5062.4  124.79
  5091.6  127.65  5112.5  125.55  5122.5  123.38  5132.5  123.15  5142.6  124.36
  5182.7  126.37  5232.8  127.28  5323.0  129.92  5413.2  133.84  5443.9  134.71
#Mann=5,-1,0
  4723.5     0.1       0  4798.1    0.05       0  4802.5     0.1       0
  4999.2    0.07       0  5005.2     0.1       0
Bank Sta=4999.2,5005.2
Exp/Cntr=0.3,0.1

Type RM Length L Ch R = 1,2698,129,129,129
BEGIN DESCRIPTION:
Mapping XS 62673d1d
END DESCRIPTION:
XS GIS Cut Line= 2
      2247746.26     13325362.39      2247091.36     13325296.55
#Sta/Elev= 30
  4714.6  127.93  4741.2  127.72  4819.3  126.40  4863.9  126.32  4873.9  125.65
  4887.6  125.69  4904.1  126.09  4919.5  125.53  4924.6  125.71  4944.3  124.83
  4974.4  126.00  4984.5  123.97  4991.5  121.50  4994.3  121.00  4997.5  121.50
  5024.8  122.90  5034.7  126.41  5074.9  125.90  5095.0  125.26  5115.0  123.93
  5120.0  122.94  5125.2  123.01  5135.2  123.16  5165.4  125.57  5286.0  128.09
  5306.1  128.78  5315.5  129.60  5320.5  128.85  5336.3  129.89  5372.8  131.05
#Mann=5,-1,0
  4714.6     0.1       0  4741.2    0.05       0  4887.6     0.1       0
  4991.5    0.07       0  4997.5     0.1       0
Bank Sta=4991.5,4997.5
Exp/Cntr=0.3,0.1

Type RM Length L Ch R = 1,2569,244,244,244
BEGIN DESCRIPTION:
Mapping XS 53b14611
END DESCRIPTION:
XS GIS Cut Line= 2
      2247808.75     13325258.22      2247111.78     13325161.13
#Sta/Elev= 30
  4630.6  127.26  4671.9  127.15  4722.1  127.69  4742.7  128.61  4748.5  127.38
  4753.5  127.98  4793.2  126.75  4825.1  126.68  4833.6  127.39  4863.9  127.36
  4874.0  126.09  4891.6  125.51  4914.3  125.21  4929.9  125.68  4944.6  125.91
  4954.7  123.69  4963.2  123.67  4968.3  122.94  4995.1  122.77  5002.2  122.20
  5005.0  121.70  5008.2  122.20  5015.3  123.09  5096.1  123.86  5136.5  125.05
  5146.6  124.74  5188.1  126.00  5227.3  126.59  5331.2  129.68  5334.3  130.16
#Mann=5,-1,0
  4630.6     0.1       0  4722.1    0.05       0  4929.9     0.1       0
  5002.2    0.07       0  5008.2     0.1       0
Bank Sta=5002.2,5008.2
Exp/Cntr=0.3,0.1

Type RM Length L Ch R = 1,2325,153,153,153
BEGIN DESCRIPTION:
Mapping XS 38c136fa
END DESCRIPTION:
XS GIS Cut Line= 2
      2247881.66     13325056.83      2247073.99     13324921.65
#Sta/Elev= 30
  4527.5  127.49  4551.8  127.18  4592.3  128.01  4618.0  127.31  4643.0  127.90
  4703.9  127.82  4800.1  126.59  4815.4  126.82  4886.4  125.06  4906.6  123.60
  4937.1  123.20  4947.2  123.47  4957.3  123.10  4967.5  122.04  4987.7  121.96
  5005.0  120.74  5007.8  120.24  5011.0  120.74  5018.2  121.77  5068.9  122.45
  5079.0  123.34  5119.6  124.18  5139.8  125.22  5200.7  126.66  5231.1  127.99
  5251.4  128.21  5261.5  129.05  5280.6  129.25  5341.3  131.59  5346.4  132.26
#Mann=3,-1,0
  4527.5     0.1       0  5005.0    0.07       0  5011.0     0.1       0
Bank Sta=5005,5011
Exp/Cntr=0.3,0.1

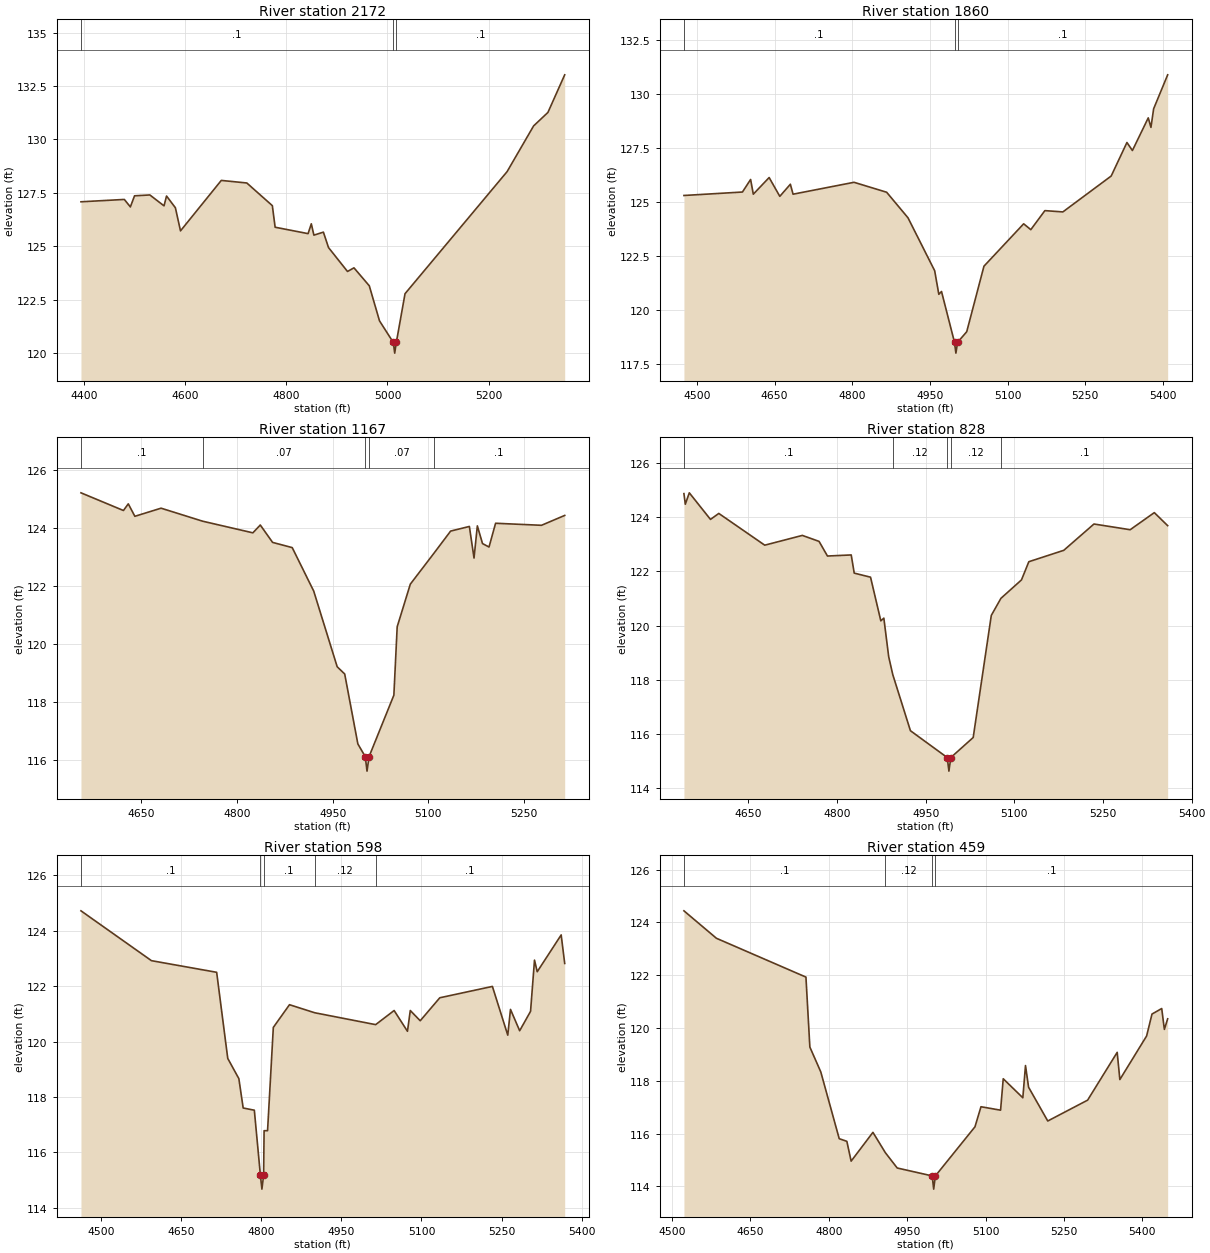
Type RM Length L Ch R = 1,2172,312,312,312
BEGIN DESCRIPTION:
Mapping XS f9eef597
END DESCRIPTION:
XS GIS Cut Line= 2
      2247992.71     13324924.88      2247044.85     13324792.94
#Sta/Elev= 30
  4393.7  127.08  4479.5  127.19  4491.4  126.84  4499.7  127.36  4530.0  127.40
  4558.0  126.89  4563.0  127.35  4580.5  126.80  4590.6  125.72  4671.3  128.08
  4721.8  127.96  4772.3  126.90  4777.8  125.89  4843.0  125.59  4849.4  126.05
  4854.5  125.52  4873.3  125.66  4883.4  124.94  4921.0  123.82  4933.8  123.99
  4964.1  123.15  4984.3  121.51  5011.6  120.50  5014.4  120.00  5017.6  120.50
  5034.8  122.78  5236.7  128.49  5289.2  130.63  5317.5  131.26  5350.7  133.02
#Mann=3,-1,0
  4393.7     0.1       0  5011.6    0.07       0  5017.6     0.1       0
Bank Sta=5011.6,5017.6
Exp/Cntr=0.3,0.1

Type RM Length L Ch R = 1,1860,693,693,693
BEGIN DESCRIPTION:
Mapping XS f0b32845
END DESCRIPTION:
XS GIS Cut Line= 2
      2247897.28     13324663.61      2246991.45     13324433.90
#Sta/Elev= 30
  4474.8  125.31  4587.8  125.47  4603.6  126.05  4608.8  125.37  4639.4  126.14
  4660.0  125.27  4680.4  125.83  4685.6  125.37  4803.4  125.92  4866.4  125.46
  4907.6  124.28  4959.2  121.83  4967.2  120.74  4972.4  120.87  4997.5  118.52
  5000.2  118.02  5003.5  118.52  5021.1  119.01  5054.4  122.04  5131.1  124.00
  5144.9  123.73  5172.1  124.61  5206.8  124.55  5300.2  126.21  5330.6  127.76
  5341.2  127.39  5371.8  128.90  5377.0  128.46  5382.2  129.32  5409.3  130.89
#Mann=3,-1,0
  4474.8     0.1       0  4997.5    0.07       0  5003.5     0.1       0
Bank Sta=4997.5,5003.5
Exp/Cntr=0.3,0.1

Type RM Length L Ch R = 1,1167,339,339,339
BEGIN DESCRIPTION:
Mapping XS 55fc0f8a
END DESCRIPTION:
XS GIS Cut Line= 2
      2247649.83     13324016.89      2246912.37     13323839.03
#Sta/Elev= 30
  4555.1  125.20  4621.7  124.59  4629.3  124.82  4639.6  124.39  4680.7  124.67
  4746.1  124.22  4824.7  123.82  4836.3  124.09  4855.6  123.49  4886.4  123.31
  4920.1  121.81  4956.9  119.20  4968.7  118.95  4989.3  116.54  5000.9  116.10
  5003.7  115.60  5006.9  116.10  5045.8  118.22  5051.0  120.58  5071.6  122.05
  5108.1  123.10  5134.8  123.88  5164.2  124.04  5171.5  122.95  5176.7  124.06
  5184.8  123.45  5195.0  123.33  5205.3  124.15  5277.3  124.08  5313.7  124.42
#Mann=5,-1,0
  4555.1     0.1       0  4746.1    0.07       0  5000.9    0.07       0
  5006.9    0.07       0  5108.1     0.1       0
Bank Sta=5000.9,5006.9
Exp/Cntr=0.3,0.1

Type RM Length L Ch R = 1,828,230,230,230
BEGIN DESCRIPTION:
Mapping XS 928bd800
END DESCRIPTION:
XS GIS Cut Line= 3
      2247593.47     13323804.25      2247398.13     13323626.28
      2246855.60     13323513.43
#Sta/Elev= 30
  4541.0  124.87  4543.3  124.48  4550.1  124.90  4585.9  123.92  4600.0  124.14
  4677.7  122.97  4741.3  123.33  4769.6  123.11  4783.8  122.57  4824.0  122.61
  4829.1  121.94  4856.7  121.79  4874.1  120.18  4879.2  120.28  4887.4  118.86
  4894.3  118.20  4924.2  116.13  4986.5  115.14  4989.3  114.64  4992.5  115.14
  5030.4  115.88  5061.0  120.38  5077.3  121.01  5112.1  121.69  5124.5  122.36
  5183.6  122.78  5234.7  123.75  5296.0  123.54  5336.8  124.17  5359.4  123.69
#Mann=5,-1,0
  4541.0     0.1       0  4894.3    0.12       0  4986.5    0.07       0
  4992.5    0.12       0  5077.3     0.1       0
Bank Sta=4986.5,4992.5
Exp/Cntr=0.3,0.1

Type RM Length L Ch R = 1,598,139,139,139
BEGIN DESCRIPTION:
Mapping XS 920a63e4
END DESCRIPTION:
XS GIS Cut Line= 4
      2247671.54     13323739.09      2247458.89     13323465.68
      2247133.37     13323344.16      2246925.07     13323300.76
#Sta/Elev= 30
  4461.8  124.72  4593.9  122.92  4716.1  122.50  4736.9  119.39  4757.7  118.66
  4765.8  117.60  4786.7  117.52  4798.1  115.17  4800.9  114.67  4804.1  115.17
  4805.0  116.78  4811.5  116.78  4822.3  120.51  4852.6  121.33  4899.7  121.04
  5014.1  120.61  5048.7  121.12  5073.7  120.37  5079.0  121.12  5097.6  120.75
  5134.3  121.58  5232.9  121.99  5261.7  120.23  5266.8  121.16  5284.0  120.39
  5304.4  121.09  5311.8  122.94  5316.9  122.52  5361.8  123.85  5368.4  122.82
#Mann=5,-1,0
  4461.8     0.1       0  4798.1    0.07       0  4804.1     0.1       0
  4899.7    0.12       0  5014.1     0.1       0
Bank Sta=4798.1,4804.1
Exp/Cntr=0.3,0.1

Type RM Length L Ch R = 1,459,188,188,188
BEGIN DESCRIPTION:
Mapping XS 5ce8c131
END DESCRIPTION:
XS GIS Cut Line= 3
      2247719.34     13323682.73      2247471.91     13323357.18
      2246968.48     13323240.00
#Sta/Elev= 30
  4522.8  124.44  4585.0  123.40  4756.3  121.93  4763.8  119.28  4784.7  118.34
  4820.0  115.81  4834.6  115.71  4842.8  114.96  4884.5  116.05  4908.3  115.28
  4931.0  114.70  4998.0  114.40  5000.8  113.90  5004.0  114.40  5079.8  116.26
  5091.3  117.02  5128.8  116.89  5133.9  118.08  5171.4  117.36  5176.5  118.58
  5182.4  117.76  5219.1  116.48  5295.4  117.27  5352.0  119.08  5357.1  118.05
  5408.3  119.70  5418.6  120.53  5437.2  120.74  5442.3  119.95  5448.6  120.35
#Mann=4,-1,0
  4522.8     0.1       0  4908.3    0.12       0  4998.0    0.07       0
  5004.0     0.1       0
Bank Sta=4998,5004
Exp/Cntr=0.3,0.1

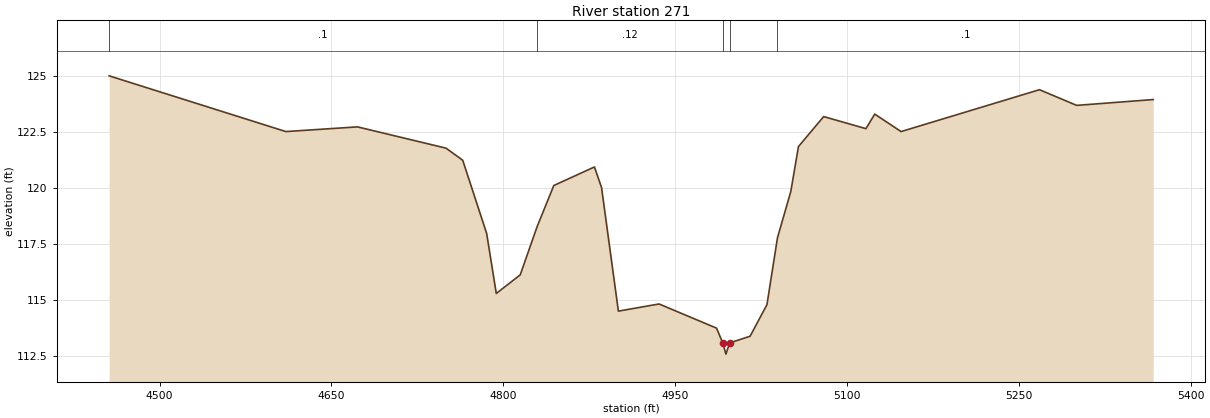
Type RM Length L Ch R = 1,271,0,0,0
BEGIN DESCRIPTION:
UNT050 IN SPCR 1.0
END DESCRIPTION:
XS GIS Cut Line= 4
      2247820.52     13323707.67      2247781.46     13323555.79
      2247508.03     13323182.53      2247222.40     13323121.94
#Sta/Elev= 30
  4455.9  125.01  4610.2  122.52  4672.7  122.73  4750.0  121.78  4764.6  121.24
  4785.5  117.97  4793.9  115.29  4814.8  116.12  4829.6  118.28  4844.1  120.11
  4879.6  120.94  4885.8  120.02  4900.5  114.50  4936.0  114.82  4986.2  113.74
  4991.6  113.08  4994.4  112.58  4997.6  113.08  5015.5  113.38  5030.2  114.79
  5039.4  117.78  5051.0  119.84  5057.7  121.85  5079.7  123.19  5116.6  122.65
  5124.3  123.30  5147.3  122.52  5268.1  124.39  5300.6  123.69  5367.4  123.95
#Mann=5,-1,0
  4455.9     0.1       0  4829.6    0.12       0  4991.6    0.07       0
  4997.6    0.12       0  5039.4     0.1       0
Bank Sta=4991.6,4997.6
Exp/Cntr=0.3,0.1

Chan Stop Cuts=-1