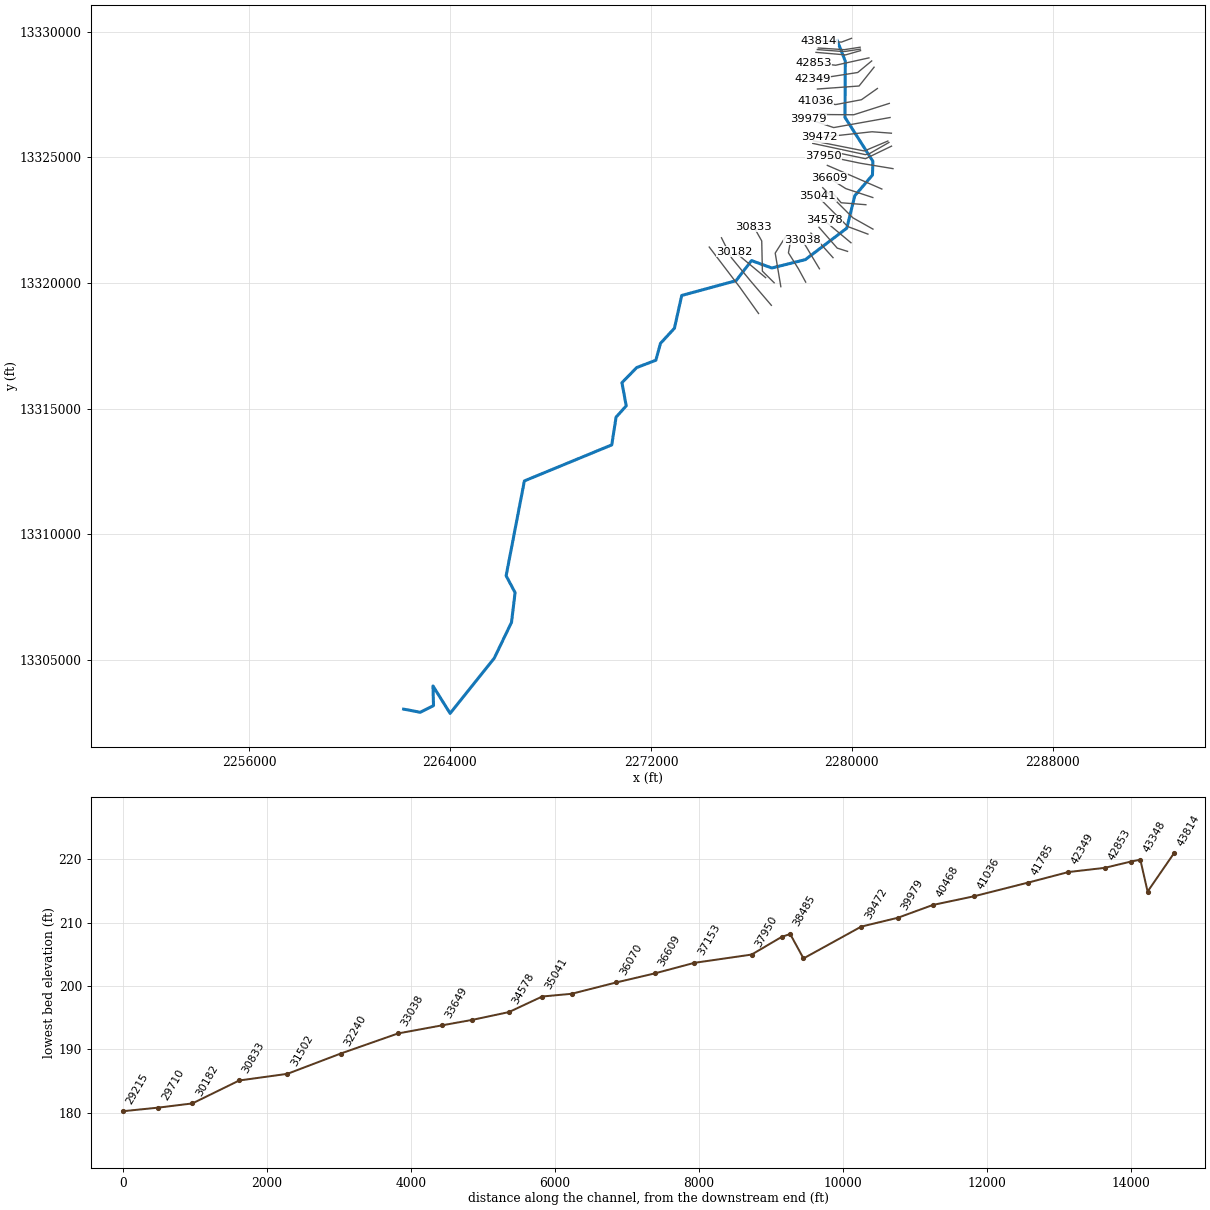
--- UNT051 IN SPCR.prj (project) ---

Proj Title=UNT051 IN SPCR Base Level Engineering
Current Plan=p01
Default Exp/Contr=0.3,0.1
English Units
Geom File=g01
Flow File=f01
Plan File=p01
Y Axis Title=Elevation
X Axis Title(PF)=Main Channel Distance
X Axis Title(XS)=Station
BEGIN DESCRIPTION:
UNT051 IN SPCR
END DESCRIPTION:
DSS Export Rating Curves= 0
DSS Export Rating Curve Sorted= 0
DSS Export Volume Flow Curves= 0
DXF OffsetX= 0
DXF OffsetY= 0
DXF ScaleX= 1
DXF ScaleY= 10

--- UNT051 IN SPCR.p01 (plan) ---

Plan Title=Multiple Run
Short Identifier=Multiple
Geom File=g01
Flow File=f01
Subcritical Flow
K Sum by GR= 0
Std Step Tol= 0.01
Critical Tol= 0.01
Num of Std Step Trials= 20
Max Error Tol= 0.3
Flow Tol Ratio= 0.001
Split Flow NTrial= 30
Split Flow Tol= 0.02
Split Flow Ratio= 0.02
Log Output Level= 0
Friction Slope Method= 1
Unsteady Friction Slope Method= 2
Unsteady Bridges Friction Slope Method= 1
Parabolic Critical Depth
Global Vel Dist=  1 , 1 , 1
Global Log Level= 0
CheckData=True
Encroach Param= -1, 0, 0, 0
BEGIN DESCRIPTION:
Multiple Run
END DESCRIPTION:

--- UNT051 IN SPCR.f01 (steady flow) ---

Flow Title=Multiple
Number of Profiles=7
Profile Names=10-year,25-year,50-year,1pct_min,100-year,1pct_plu,500-year
River Rch & RM= UNT051 IN SPCR,Reach-1,43814
     195     263     319     284     384     519     565
River Rch & RM= UNT051 IN SPCR,Reach-1,39472
     300     415     510     461     623     843     943
River Rch & RM= UNT051 IN SPCR,Reach-1,35450
     365     508     627     569     769    1041    1175
River Rch & RM= UNT051 IN SPCR,Reach-1,30833
     439     617     766     699     945    1278    1458
River Rch & RM= UNT051 IN SPCR,Reach-1,27916
     460     647     804     733     992    1341    1532
River Rch & RM= UNT051 IN SPCR,Reach-1,21578
     597     851    1066     979    1324    1791    2075
River Rch & RM= UNT051 IN SPCR,Reach-1,12803
     715    1025    1290    1189    1608    2175    2539
River Rch & RM= UNT051 IN SPCR,Reach-1,8226
     739    1062    1339    1237    1673    2262    2650
River Rch & RM= UNT051 IN SPCR,Reach-1,684
     824    1189    1503    1392    1883    2546    2998
Boundary for River Rch & Prof#=UNT051 IN SPCR,Reach-1,1
Up Type=0
Dn Type=3
Dn Slope=0.005
Boundary for River Rch & Prof#=UNT051 IN SPCR,Reach-1,2
Up Type=0
Dn Type=3
Dn Slope=0.005
Boundary for River Rch & Prof#=UNT051 IN SPCR,Reach-1,3
Up Type=0
Dn Type=3
Dn Slope=0.005
Boundary for River Rch & Prof#=UNT051 IN SPCR,Reach-1,4
Up Type=0
Dn Type=3
Dn Slope=0.005
Boundary for River Rch & Prof#=UNT051 IN SPCR,Reach-1,5
Up Type=0
Dn Type=3
Dn Slope=0.005
Boundary for River Rch & Prof#=UNT051 IN SPCR,Reach-1,6
Up Type=0
Dn Type=3
Dn Slope=0.005
Boundary for River Rch & Prof#=UNT051 IN SPCR,Reach-1,7
Up Type=0
Dn Type=3
Dn Slope=0.005

--- UNT051 IN SPCR.g01 (geometry) ---

Geom Title=Existing Conditions

River Reach=UNT051 IN SPCR,Reach-1
Reach XY= 30
      2279414.30     13329661.25      2279736.83     13328836.50
      2279724.32     13326598.69      2280836.20     13324845.50
      2280818.03     13324301.52      2280113.60     13323473.61
      2279797.18     13322185.80      2278146.06     13320930.72
      2276812.80     13320597.21      2276003.31     13320892.44
      2275386.94     13320091.33      2273225.44     13319503.07
      2272935.19     13318197.86      2272380.24     13317595.81
      2272194.73     13316922.40      2271435.06     13316631.97
      2270844.92     13316028.62      2271015.65     13315105.19
      2270611.83     13314655.40      2270440.00     13313549.98
      2266961.52     13312115.28      2266234.81     13308336.78
      2266591.58     13307664.91      2266449.22     13306480.88
      2265762.69     13305054.23      2264004.78     13302854.21
      2263322.70     13303946.88      2263344.04     13303164.49
      2262817.89     13302897.86      2262154.24     13303023.63

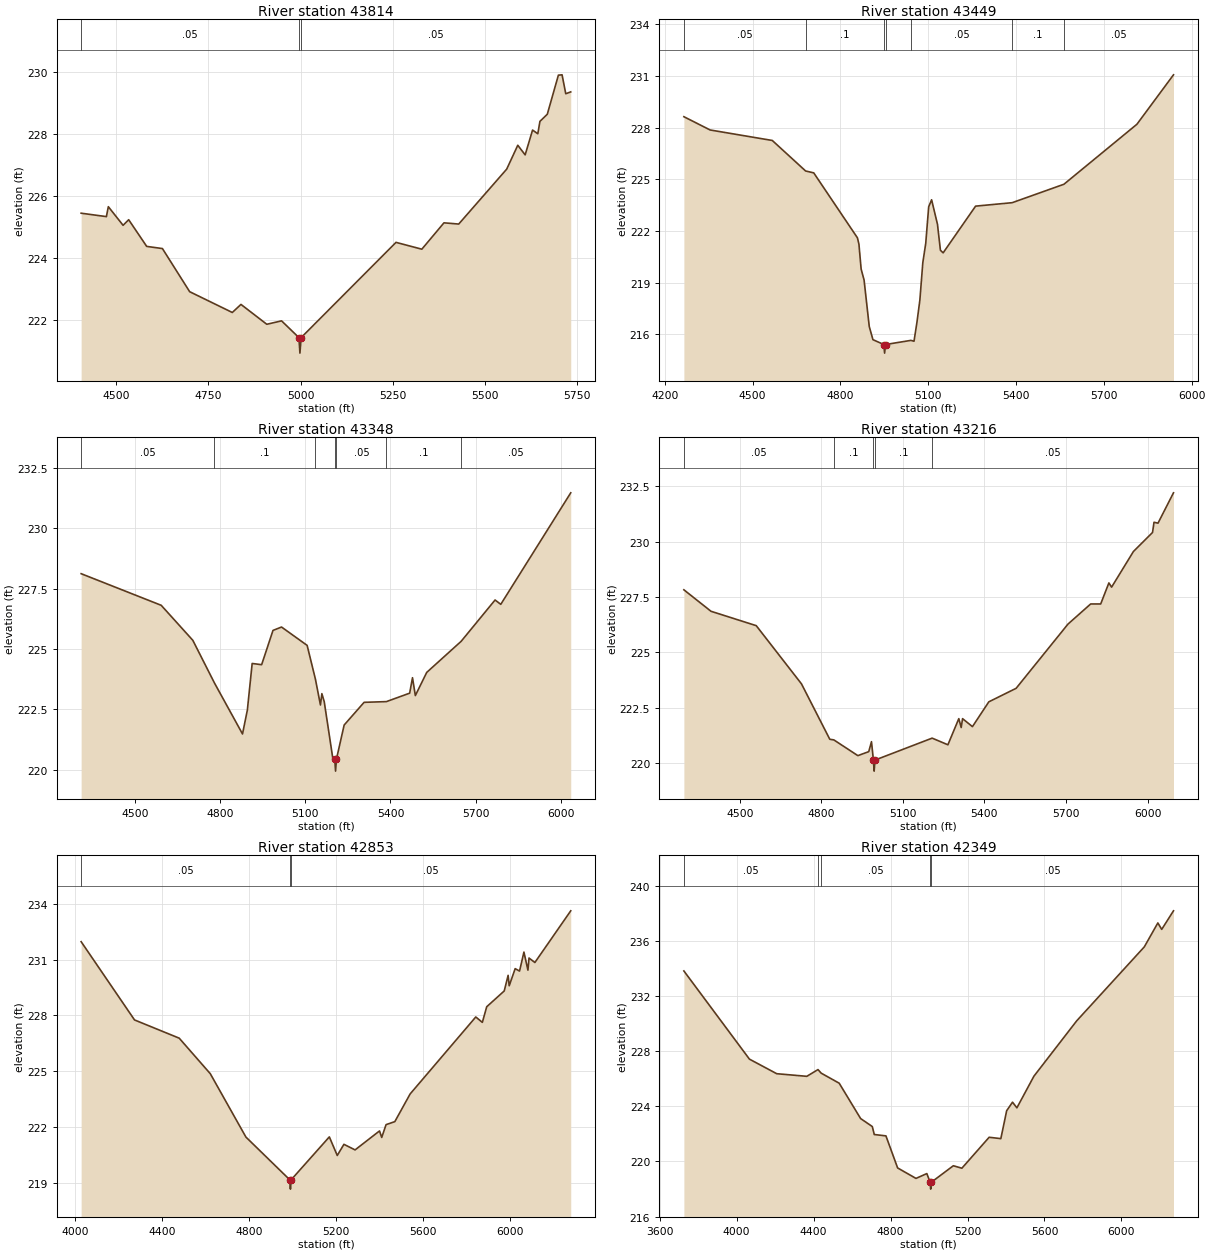
Type RM Length L Ch R = 1,43814,365,365,365
BEGIN DESCRIPTION:
UNT051 IN SPCR 62.0
END DESCRIPTION:
XS GIS Cut Line= 3
      2279984.25     13329746.85      2279584.25     13329596.85
      2278684.24     13329646.86
#Sta/Elev= 30
  4404.7  225.44  4473.2  225.33  4478.5  225.65  4518.5  225.05  4533.7  225.23
  4582.6  224.37  4625.3  224.30  4699.2  222.91  4814.9  222.24  4838.4  222.50
  4908.5  221.86  4948.6  221.97  4995.7  221.43  4998.4  220.93  5001.7  221.43
  5259.1  224.50  5329.2  224.28  5389.3  225.13  5429.3  225.09  5559.5  226.86
  5589.6  227.63  5609.6  227.32  5629.7  228.12  5643.9  228.00  5649.7  228.40
  5669.7  228.63  5699.8  229.89  5709.8  229.90  5719.8  229.29  5733.3  229.35
#Mann=3,-1,0
  4404.7    0.05       0  4995.7    0.03       0  5001.7    0.05       0
Bank Sta=4995.7,5001.7
Exp/Cntr=0.3,0.1

Type RM Length L Ch R = 1,43449,101,101,101
BEGIN DESCRIPTION:
Mapping XS 1fa71036
END DESCRIPTION:
XS GIS Cut Line= 3
      2280326.23     13329392.91      2279697.74     13329295.68
      2278663.00     13329361.65
#Sta/Elev= 30
  4265.1  228.63  4354.7  227.86  4567.2  227.25  4681.0  225.48  4708.8  225.37
  4858.1  221.60  4863.2  221.23  4870.7  219.79  4880.8  219.15  4898.5  216.45
  4911.1  215.69  4948.2  215.41  4950.9  214.91  4954.2  215.41  5040.8  215.65
  5051.4  215.60  5061.4  216.70  5071.4  217.99  5081.4  220.15  5091.5  221.29
  5101.5  223.40  5111.5  223.81  5131.5  222.39  5141.6  220.88  5150.9  220.73
  5261.8  223.44  5386.8  223.64  5563.6  224.71  5812.9  228.19  5937.9  231.06
#Mann=7,-1,0
  4265.1    0.05       0  4681.0     0.1       0  4948.2    0.07       0
  4954.2     0.1       0  5040.8    0.05       0  5386.8     0.1       0
  5563.6    0.05       0
Bank Sta=4948.2,4954.2
Exp/Cntr=0.3,0.1

Type RM Length L Ch R = 1,43348,132,132,132
BEGIN DESCRIPTION:
Mapping XS 79fcc830
END DESCRIPTION:
XS GIS Cut Line= 4
      2280336.59     13329316.51      2279739.41     13329226.24
      2279617.88     13329222.76      2278622.04     13329299.10
#Sta/Elev= 30
  4310.6  228.12  4592.6  226.81  4703.9  225.36  4780.2  223.59  4878.9  221.48
  4896.0  222.47  4912.9  224.40  4946.3  224.35  4986.3  225.77  5016.3  225.91
  5106.5  225.15  5135.7  223.75  5153.4  222.68  5158.4  223.15  5166.7  222.82
  5196.8  220.48  5203.8  220.44  5206.6  219.94  5209.8  220.44  5236.9  221.85
  5307.1  222.79  5385.6  222.82  5467.6  223.17  5477.6  223.81  5487.6  223.07
  5527.7  224.03  5649.1  225.32  5768.4  227.03  5788.5  226.85  6034.9  231.47
#Mann=7,-1,0
  4310.6    0.05       0  4780.2     0.1       0  5135.7    0.05       0
  5203.8    0.07       0  5209.8    0.05       0  5385.6     0.1       0
  5649.1    0.05       0
Bank Sta=5203.8,5209.8
Exp/Cntr=0.3,0.1

Type RM Length L Ch R = 1,43216,363,363,363
BEGIN DESCRIPTION:
Mapping XS 30ca1b57
END DESCRIPTION:
XS GIS Cut Line= 3
      2280343.60     13329257.49      2279749.82     13329087.35
      2278570.98     13329187.90
#Sta/Elev= 30
  4294.6  227.83  4394.3  226.86  4560.8  226.21  4727.2  223.58  4831.2  221.08
  4846.2  221.05  4934.5  220.34  4974.6  220.52  4984.6  220.97  4991.7  220.14
  4994.4  219.64  4997.7  220.14  5207.7  221.13  5265.7  220.83  5305.8  222.01
  5314.6  221.61  5319.6  222.01  5356.0  221.65  5416.2  222.77  5516.6  223.38
  5707.3  226.28  5790.8  227.19  5827.7  227.19  5857.8  228.14  5867.8  227.95
  5948.1  229.56  6018.4  230.42  6023.8  230.88  6038.5  230.84  6095.4  232.21
#Mann=5,-1,0
  4294.6    0.05       0  4846.2     0.1       0  4991.7    0.07       0
  4997.7     0.1       0  5207.7    0.05       0
Bank Sta=4991.7,4997.7
Exp/Cntr=0.3,0.1

Type RM Length L Ch R = 1,42853,504,504,504
BEGIN DESCRIPTION:
UNT051 IN SPCR 60.0
END DESCRIPTION:
XS GIS Cut Line= 3
      2280677.39     13328968.29      2279353.56     13328675.31
      2278463.76     13328772.97
#Sta/Elev= 30
  4027.7  231.96  4273.2  227.75  4478.6  226.77  4621.4  224.86  4785.3  221.45
  4987.1  219.15  4989.9  218.65  4993.1  219.15  5168.8  221.46  5205.2  220.46
  5235.9  221.06  5287.1  220.76  5399.5  221.78  5409.6  221.43  5429.7  222.12
  5469.9  222.28  5540.3  223.77  5842.1  227.91  5872.3  227.62  5892.4  228.46
  5972.9  229.31  5990.8  230.15  5995.8  229.59  6023.2  230.51  6043.3  230.38
  6063.5  231.40  6081.9  230.43  6086.9  231.08  6113.8  230.84  6278.7  233.62
#Mann=3,-1,0
  4027.7    0.05       0  4987.1    0.03       0  4993.1    0.05       0
Bank Sta=4987.1,4993.1
Exp/Cntr=0.3,0.1

Type RM Length L Ch R = 1,42349,564,564,564
BEGIN DESCRIPTION:
UNT051 IN SPCR 59.0
END DESCRIPTION:
XS GIS Cut Line= 4
      2280787.71     13328846.84      2280230.55     13328385.62
      2279002.71     13328195.47      2278426.84     13328141.14
#Sta/Elev= 30
  3726.1  233.85  4066.7  227.44  4208.6  226.38  4364.9  226.19  4423.0  226.68
  4439.6  226.42  4533.2  225.69  4644.5  223.12  4705.2  222.54  4715.4  221.96
  4776.1  221.86  4836.8  219.53  4932.2  218.77  4988.6  219.12  5005.8  218.49
  5008.6  217.99  5011.8  218.49  5126.3  219.69  5170.7  219.51  5312.4  221.76
  5373.1  221.66  5403.5  223.69  5433.8  224.31  5456.6  223.90  5545.1  226.20
  5767.2  230.22  6118.7  235.60  6189.1  237.34  6209.1  236.87  6270.3  238.22
#Mann=5,-1,0
  3726.1    0.05       0  4423.0     0.1       0  4439.6    0.05       0
  5005.8    0.03       0  5011.8    0.05       0
Bank Sta=5005.8,5011.8
Exp/Cntr=0.3,0.1

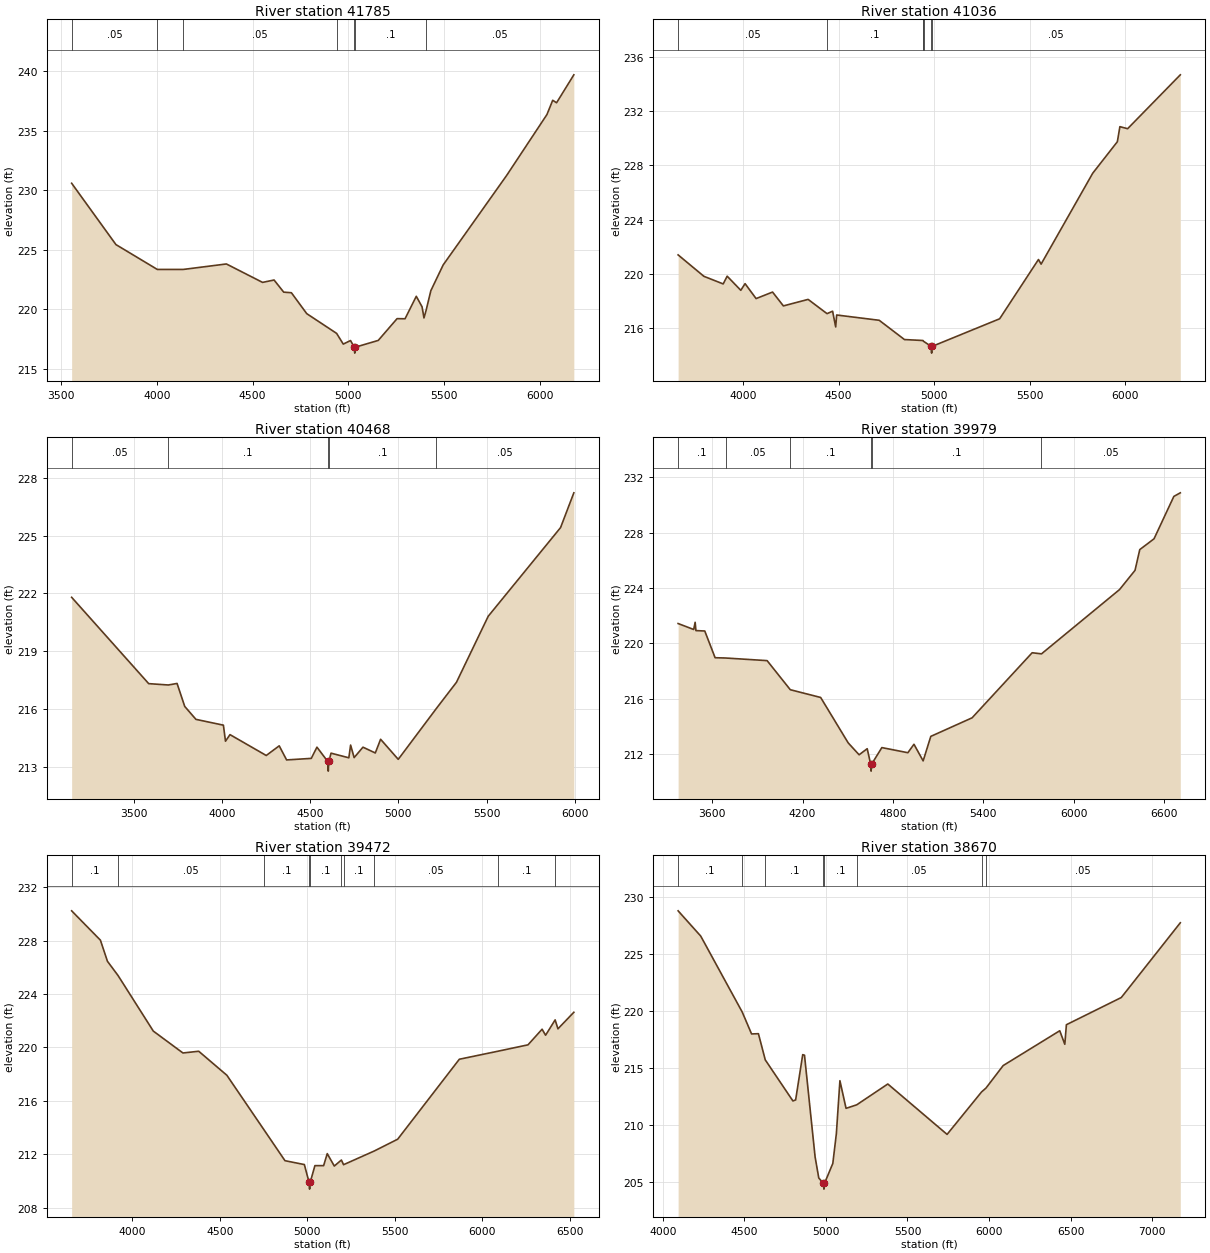
Type RM Length L Ch R = 1,41785,749,749,749
BEGIN DESCRIPTION:
UNT051 IN SPCR 58.0
END DESCRIPTION:
XS GIS Cut Line= 3
      2280882.53     13328597.53      2280284.88     13327847.76
      2278627.81     13327728.23
#Sta/Elev= 30
  3556.3  230.60  3787.4  225.44  4003.2  223.35  4139.1  223.35  4363.7  223.81
  4552.4  222.26  4612.5  222.46  4662.7  221.44  4702.8  221.39  4783.0  219.63
  4938.9  217.97  4973.5  217.07  5011.4  217.37  5030.6  216.81  5033.4  216.31
  5036.6  216.81  5156.1  217.38  5254.2  219.21  5295.8  219.20  5354.5  221.09
  5384.5  220.21  5394.6  219.27  5405.9  219.92  5430.4  221.56  5494.8  223.73
  5825.7  231.25  6036.2  236.38  6066.3  237.58  6086.4  237.37  6176.5  239.72
#Mann=7,-1,0
  3556.3    0.05       0  4003.2     0.1       0  4139.1    0.05       0
  4938.9     0.1       0  5030.6    0.07       0  5036.6     0.1       0
  5405.9    0.05       0
Bank Sta=5030.6,5036.6
Exp/Cntr=0.3,0.1

Type RM Length L Ch R = 1,41036,568,568,568
BEGIN DESCRIPTION:
UNT051 IN SPCR 57.0
END DESCRIPTION:
XS GIS Cut Line= 4
      2281014.35     13327748.82      2280378.91     13327300.89
      2279352.86     13327108.18      2278556.02     13327248.80
#Sta/Elev= 30
  3659.0  221.40  3794.1  219.82  3895.1  219.26  3916.0  219.83  3987.4  218.79
  4009.7  219.28  4067.5  218.18  4153.7  218.66  4210.4  217.64  4340.0  218.12
  4439.1  217.07  4468.2  217.25  4484.4  216.09  4489.5  216.97  4712.4  216.58
  4844.7  215.16  4941.8  215.09  4943.8  215.05  4944.7  215.03  4984.1  214.66
  4986.9  214.16  4990.1  214.66  5343.2  216.69  5546.6  221.06  5560.5  220.72
  5830.9  227.42  5959.9  229.74  5973.1  230.85  6013.7  230.70  6289.6  234.67
#Mann=7,-1,0
  3659.0    0.05       0  4439.1     0.1       0  4941.8    0.05       0
  4943.8     0.1       0  4944.7    0.05       0  4984.1    0.03       0
  4990.1    0.05       0
Bank Sta=4984.1,4990.1
Exp/Cntr=0.3,0.1

Type RM Length L Ch R = 1,40468,489,489,489
BEGIN DESCRIPTION:
UNT051 IN SPCR 56.0
END DESCRIPTION:
XS GIS Cut Line= 3
      2281488.25     13327155.04      2280071.61     13326701.93
      2278712.49     13326712.34
#Sta/Elev= 30
  3148.5  221.80  3585.2  217.33  3696.4  217.26  3746.0  217.34  3789.5  216.15
  3853.0  215.48  4008.6  215.18  4020.5  214.35  4046.0  214.69  4251.5  213.61
  4325.0  214.11  4366.9  213.38  4506.7  213.46  4538.9  214.04  4600.2  213.30
  4603.0  212.80  4606.2  213.30  4618.9  213.73  4719.7  213.49  4729.7  214.15
  4749.7  213.50  4799.7  214.04  4869.7  213.74  4899.7  214.45  4999.7  213.41
  5216.3  216.05  5329.7  217.40  5509.8  220.82  5919.8  225.41  5995.0  227.21
#Mann=5,-1,0
  3148.5    0.05       0  3696.4     0.1       0  4600.2    0.07       0
  4606.2     0.1       0  5216.3    0.05       0
Bank Sta=4600.2,4606.2
Exp/Cntr=0.3,0.1

Type RM Length L Ch R = 1,39979,507,507,507
BEGIN DESCRIPTION:
UNT051 IN SPCR 55.0
END DESCRIPTION:
XS GIS Cut Line= 3
      2281519.51     13326592.55      2279274.74     13326191.51
      2278274.97     13326526.48
#Sta/Elev= 30
  3373.6  221.43  3477.0  221.00  3486.7  221.52  3491.7  220.92  3550.7  220.89
  3619.2  218.96  3688.9  218.94  3964.6  218.75  4118.5  216.65  4320.1  216.09
  4503.0  212.81  4575.4  211.95  4629.2  212.39  4652.4  211.27  4655.1  210.77
  4658.4  211.27  4726.5  212.47  4899.2  212.10  4939.8  212.71  5000.7  211.51
  5051.5  213.28  5325.8  214.62  5724.6  219.32  5786.5  219.24  6304.6  223.88
  6407.6  225.27  6439.2  226.77  6533.9  227.55  6665.4  230.61  6708.3  230.87
#Mann=6,-1,0
  3373.6     0.1       0  3688.9    0.05       0  4118.5     0.1       0
  4652.4    0.07       0  4658.4     0.1       0  5786.5    0.05       0
Bank Sta=4652.4,4658.4
Exp/Cntr=0.3,0.1

Type RM Length L Ch R = 1,39472,802,802,802
BEGIN DESCRIPTION:
UNT051 IN SPCR 53.0
END DESCRIPTION:
XS GIS Cut Line= 3
      2281571.65     13325967.55      2280800.78     13326024.84
      2278717.41     13325796.85
#Sta/Elev= 30
  3654.2  230.23  3818.6  228.03  3858.7  226.45  3919.4  225.38  4120.7  221.22
  4289.9  219.58  4380.1  219.71  4540.9  217.91  4752.7  213.83  4872.9  211.51
  4983.6  211.22  5010.7  209.88  5013.5  209.38  5016.7  209.88  5043.9  211.14
  5093.7  211.14  5114.3  212.04  5154.6  211.11  5195.2  211.56  5207.5  211.21
  5383.5  212.24  5516.7  213.12  5868.8  219.11  6088.7  219.71  6261.1  220.19
  6341.6  221.36  6361.7  220.91  6416.2  222.06  6432.2  221.39  6523.0  222.63
#Mann=10,-1,0
  3654.2     0.1       0  3919.4    0.05       0  4752.7     0.1       0
  5010.7    0.07       0  5016.7     0.1       0  5195.2    0.05       0
  5207.5     0.1       0  5383.5    0.05       0  6088.7     0.1       0
  6416.2    0.05       0
Bank Sta=5010.7,5016.7
Exp/Cntr=0.3,0.1

Type RM Length L Ch R = 1,38670,185,185,185
BEGIN DESCRIPTION:
Mapping XS 8dd7e374
END DESCRIPTION:
XS GIS Cut Line= 3
      2281431.28     13325655.36      2280493.75     13325259.51
      2278472.94     13325660.55
#Sta/Elev= 30
  4094.2  228.82  4232.8  226.60  4487.3  219.92  4544.4  218.00  4586.4  218.02
  4628.3  215.72  4797.8  212.11  4814.5  212.20  4857.9  216.18  4868.8  216.13
  4933.9  207.18  4956.3  205.34  4985.2  204.86  4987.9  204.36  4991.2  204.86
  5042.4  206.62  5064.1  209.24  5085.9  213.89  5123.5  211.46  5188.9  211.77
  5379.4  213.60  5742.7  209.17  5953.9  212.90  5981.0  213.24  6086.5  215.22
  6433.2  218.28  6464.2  217.09  6474.0  218.81  6810.4  221.20  7172.1  227.77
#Mann=8,-1,0
  4094.2     0.1       0  4487.3    0.05       0  4628.3     0.1       0
  4985.2    0.07       0  4991.2     0.1       0  5188.9    0.05       0
  5953.9     0.1       0  5981.0    0.05       0
Bank Sta=4985.2,4991.2
Exp/Cntr=0.3,0.1

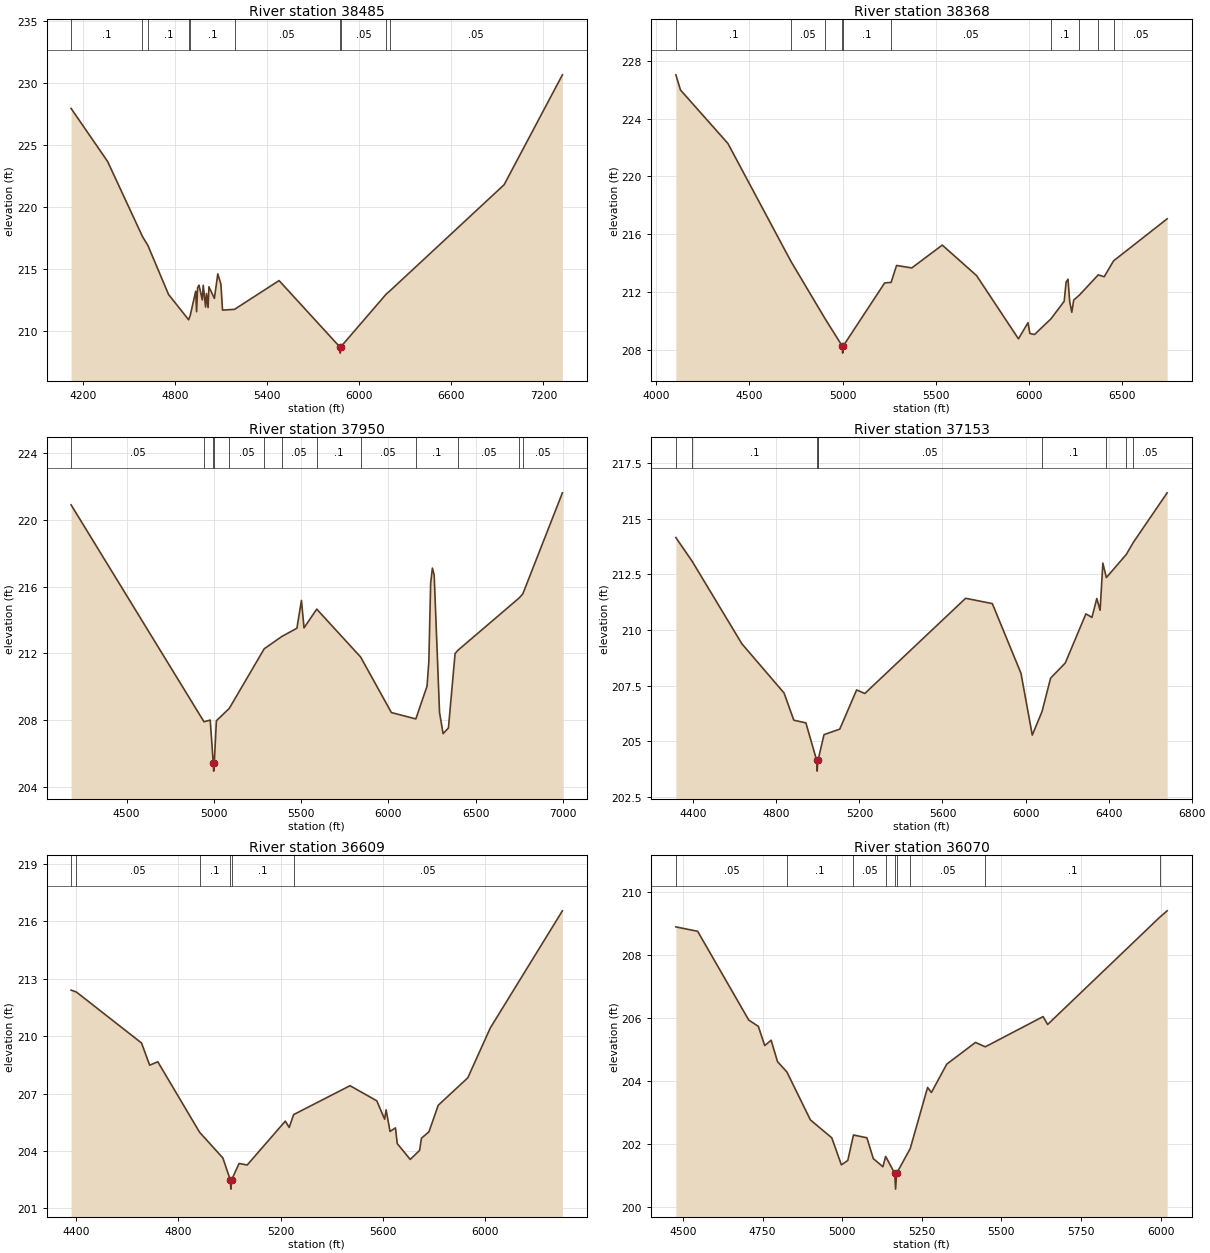
Type RM Length L Ch R = 1,38485,117,117,117
BEGIN DESCRIPTION:
Mapping XS d778e565
END DESCRIPTION:
XS GIS Cut Line= 4
      2281472.93     13325598.06      2280691.66     13325150.14
      2280535.41     13325113.68      2278442.19     13325561.48
#Sta/Elev= 30
  4122.0  227.94  4360.0  223.66  4586.8  217.62  4622.8  216.88  4757.0  212.94
  4887.9  210.90  4898.3  211.25  4933.9  213.20  4939.7  211.55  4946.4  213.50
  4955.5  213.69  4977.1  212.50  4982.8  213.68  4998.6  211.93  5004.4  213.02
  5014.5  211.88  5020.2  213.56  5055.6  212.62  5078.0  214.60  5098.2  213.77
  5108.8  211.68  5187.1  211.74  5477.2  214.06  5873.0  208.71  5875.8  208.21
  5879.0  208.71  6176.8  212.99  6197.9  213.21  6943.8  221.79  7323.6  230.65
#Mann=10,-1,0
  4122.0     0.1       0  4586.8    0.05       0  4622.8     0.1       0
  4887.9    0.05       0  4898.3     0.1       0  5187.1    0.05       0
  5873.0    0.07       0  5879.0    0.05       0  6176.8     0.1       0
  6197.9    0.05       0
Bank Sta=5873,5879
Exp/Cntr=0.3,0.1

Type RM Length L Ch R = 1,38368,418,418,418
BEGIN DESCRIPTION:
Mapping XS 24c9c41b
END DESCRIPTION:
XS GIS Cut Line= 3
      2281576.78     13325451.91      2280540.36     13324951.93
      2279087.22     13325259.22
#Sta/Elev= 30
  4105.2  227.03  4130.1  225.98  4384.4  222.28  4722.9  214.11  4905.6  210.15
  4997.4  208.26  5000.2  207.76  5003.4  208.26  5225.5  212.62  5260.2  212.66
  5289.3  213.83  5371.1  213.66  5534.6  215.24  5718.6  213.13  5943.4  208.75
  5994.5  209.87  6004.8  209.12  6029.6  209.05  6117.5  210.13  6188.7  211.35
  6199.0  212.68  6209.2  212.88  6218.3  211.32  6229.6  210.59  6239.8  211.44
  6270.4  211.78  6371.4  213.18  6403.4  213.05  6453.7  214.15  6741.2  217.06
#Mann=10,-1,0
  4105.2     0.1       0  4722.9    0.05       0  4905.6     0.1       0
  4997.4    0.07       0  5003.4     0.1       0  5260.2    0.05       0
  6117.5     0.1       0  6270.4    0.05       0  6371.4     0.1       0
  6453.7    0.05       0
Bank Sta=4997.4,5003.4
Exp/Cntr=0.3,0.1

Type RM Length L Ch R = 1,37950,797,797,797
BEGIN DESCRIPTION:
UNT051 IN SPCR 49.0
END DESCRIPTION:
XS GIS Cut Line= 3
      2281634.07     13324556.10      2280342.45     13324769.64
      2278868.50     13325076.93
#Sta/Elev= 30
  4181.9  220.88  4943.3  207.92  4978.9  208.02  4996.2  205.47  4998.9  204.97
  5002.2  205.47  5014.3  207.98  5088.2  208.72  5288.2  212.28  5388.3  213.01
  5475.6  213.51  5501.5  215.17  5516.3  213.53  5589.2  214.65  5840.5  211.79
  6016.9  208.47  6156.9  208.09  6221.2  210.05  6231.4  211.52  6241.8  216.19
  6251.8  217.10  6262.0  216.70  6292.7  208.48  6313.1  207.21  6343.7  207.55
  6381.7  211.99  6396.8  212.18  6749.2  215.32  6769.8  215.56  6996.7  221.60
#Mann=13,-1,0
  4181.9    0.05       0  4943.3     0.1       0  4996.2    0.07       0
  5002.2     0.1       0  5088.2    0.05       0  5288.2     0.1       0
  5388.3    0.05       0  5589.2     0.1       0  5840.5    0.05       0
  6156.9     0.1       0  6396.8    0.05       0  6749.2     0.1       0
  6769.8    0.05       0
Bank Sta=4996.2,5002.2
Exp/Cntr=0.3,0.1

Type RM Length L Ch R = 1,37153,544,544,544
BEGIN DESCRIPTION:
UNT051 IN SPCR 48.0
END DESCRIPTION:
XS GIS Cut Line= 3
      2281191.42     13323743.59      2280071.61     13324233.18
      2279021.16     13324685.60
#Sta/Elev= 30
  4316.1  214.16  4395.5  213.08  4633.7  209.39  4837.3  207.17  4884.1  205.95
  4942.2  205.83  4993.8  204.16  4996.6  203.66  4999.8  204.16  5001.1  204.16
  5029.6  205.30  5105.5  205.55  5186.6  207.31  5226.0  207.15  5711.6  211.43
  5840.1  211.19  5978.0  208.06  6032.5  205.28  6079.5  206.34  6120.7  207.84
  6191.3  208.52  6290.8  210.73  6319.8  210.57  6343.3  211.42  6359.1  210.89
  6372.3  213.01  6389.2  212.36  6485.2  213.40  6518.9  213.94  6682.0  216.17
#Mann=9,-1,0
  4316.1    0.05       0  4395.5     0.1       0  4993.8    0.07       0
  4999.8     0.1       0  5001.1    0.05       0  6079.5     0.1       0
  6389.2    0.05       0  6485.2     0.1       0  6518.9    0.05       0
Bank Sta=4993.8,4999.8
Exp/Cntr=0.3,0.1

Type RM Length L Ch R = 1,36609,539,539,539
BEGIN DESCRIPTION:
UNT051 IN SPCR 46.0
END DESCRIPTION:
XS GIS Cut Line= 3
      2280832.06     13323405.04      2279759.11     13323759.22
      2279092.52     13324180.78
#Sta/Elev= 30
  4381.8  212.40  4402.6  212.30  4656.8  209.64  4688.6  208.48  4720.3  208.66
  4883.5  204.98  4974.3  203.64  5003.0  202.51  5005.8  202.01  5009.0  202.51
  5037.8  203.35  5069.5  203.27  5218.3  205.56  5233.5  205.23  5250.7  205.90
  5471.0  207.41  5575.6  206.62  5606.1  205.66  5612.0  206.15  5627.3  205.02
  5648.5  205.21  5655.3  204.39  5706.1  203.56  5742.6  204.03  5750.0  204.67
  5779.1  205.00  5815.5  206.39  5930.8  207.82  6019.0  210.43  6300.4  216.54
#Mann=6,-1,0
  4381.8     0.1       0  4402.6    0.05       0  4883.5     0.1       0
  5003.0    0.07       0  5009.0     0.1       0  5250.7    0.05       0
Bank Sta=5003,5009
Exp/Cntr=0.3,0.1

Type RM Length L Ch R = 1,36070,620,620,620
BEGIN DESCRIPTION:
UNT051 IN SPCR 45.0
END DESCRIPTION:
XS GIS Cut Line= 3
      2280555.99     13323118.59      2279571.61     13323196.72
      2279209.34     13323618.13
#Sta/Elev= 30
  4477.4  208.90  4545.9  208.76  4706.4  205.94  4736.5  205.74  4756.5  205.13
  4776.6  205.30  4796.7  204.62  4826.3  204.29  4899.9  202.77  4967.2  202.20
  4997.3  201.34  5017.4  201.48  5035.3  202.29  5077.5  202.20  5097.6  201.54
  5127.7  201.28  5136.4  201.61  5164.8  201.07  5167.6  200.57  5170.8  201.07
  5213.6  201.86  5268.1  203.80  5280.1  203.64  5328.3  204.54  5418.6  205.23
  5449.2  205.09  5630.9  206.05  5645.2  205.80  5997.6  209.21  6020.6  209.41
#Mann=9,-1,0
  4477.4    0.05       0  4826.3     0.1       0  5035.3    0.05       0
  5136.4     0.1       0  5164.8    0.07       0  5170.8     0.1       0
  5213.6    0.05       0  5449.2     0.1       0  5997.6    0.05       0
Bank Sta=5164.8,5170.8
Exp/Cntr=0.3,0.1

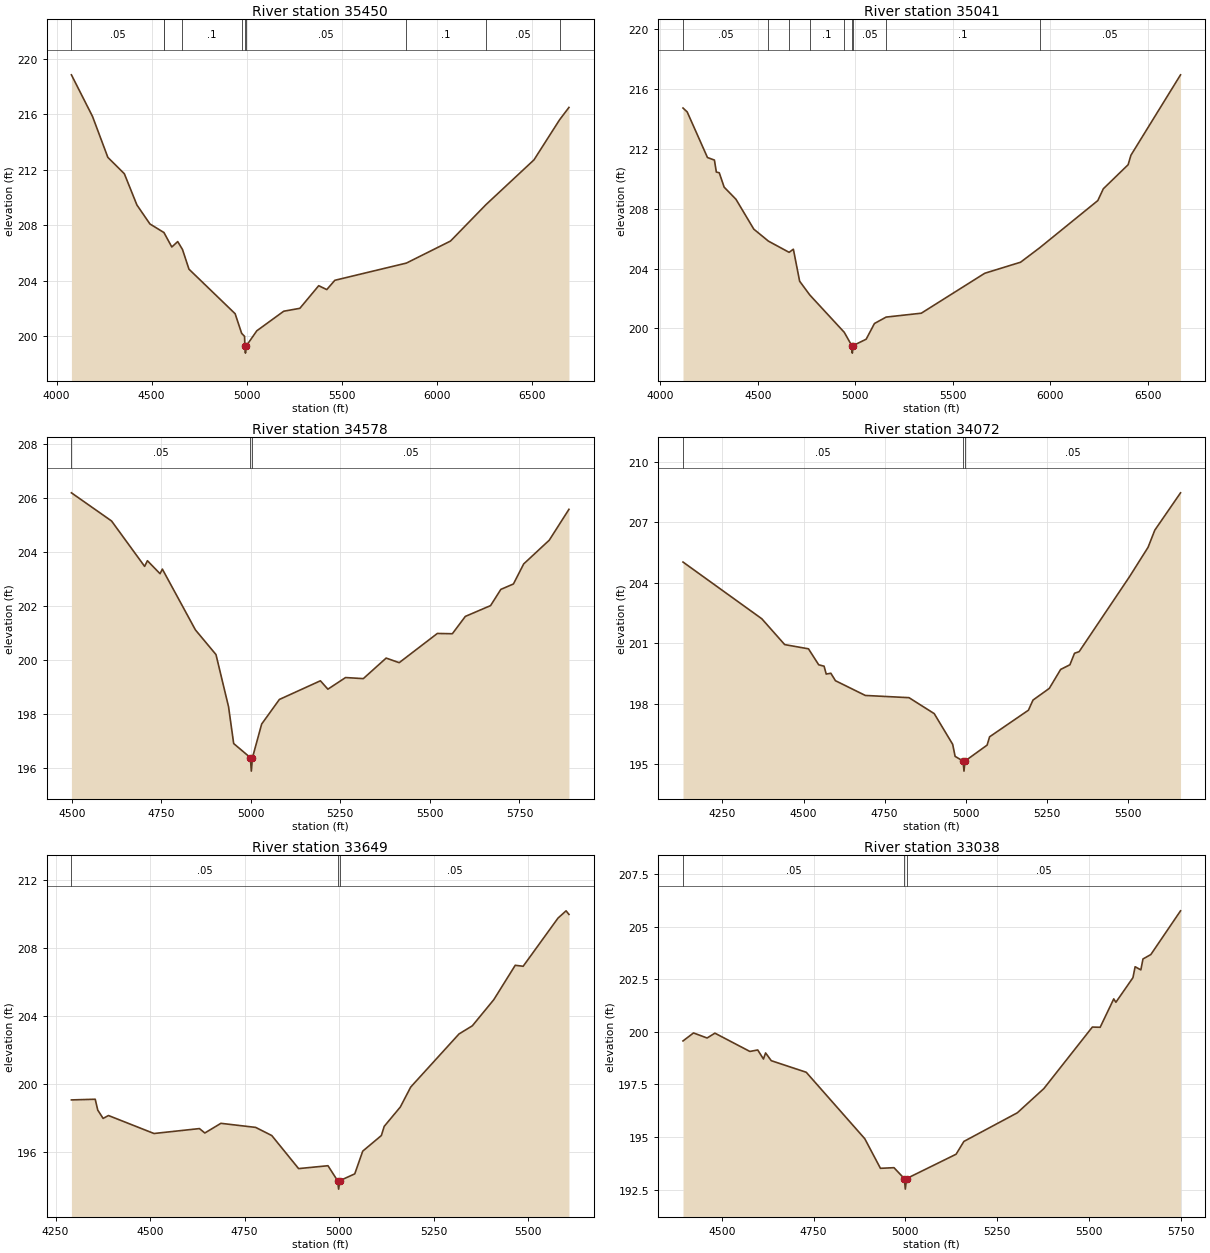
Type RM Length L Ch R = 1,35450,409,409,409
BEGIN DESCRIPTION:
UNT051 IN SPCR 44.0
END DESCRIPTION:
XS GIS Cut Line= 3
      2280837.69     13322146.87      2280037.72     13322596.85
      2278837.72     13323796.85
#Sta/Elev= 30
  4078.4  218.84  4189.0  215.85  4269.9  212.89  4356.6  211.71  4422.6  209.46
  4491.1  208.09  4562.6  207.49  4564.4  207.48  4606.1  206.43  4637.1  206.82
  4662.2  206.25  4696.3  204.83  4938.9  201.62  4973.0  200.21  4988.3  199.99
  4990.4  199.28  4993.1  198.78  4996.4  199.28  5052.8  200.39  5194.2  201.80
  5279.1  202.01  5378.1  203.64  5420.5  203.36  5462.9  204.03  5839.0  205.27
  6071.0  206.86  6257.7  209.49  6509.5  212.71  6644.1  215.60  6693.3  216.49
#Mann=10,-1,0
  4078.4    0.05       0  4562.6     0.1       0  4564.4    0.08       0
  4662.2     0.1       0  4973.0    0.05       0  4990.4   0.035       0
  4996.4    0.05       0  5839.0     0.1       0  6257.7    0.05       0
  6644.1     0.1       0
Bank Sta=4990.4,4996.4
Exp/Cntr=0.3,0.1

Type RM Length L Ch R = 1,35041,463,463,463
BEGIN DESCRIPTION:
UNT051 IN SPCR 43.0
END DESCRIPTION:
XS GIS Cut Line= 3
      2280637.72     13321946.85      2279837.72     13322246.85
      2278637.69     13323446.88
#Sta/Elev= 30
  4117.0  214.74  4138.4  214.48  4242.5  211.43  4278.1  211.26  4287.9  210.46
  4303.0  210.41  4327.9  209.45  4388.5  208.64  4480.1  206.64  4555.0  205.84
  4661.1  205.09  4683.0  205.30  4715.1  203.16  4767.1  202.24  4944.1  199.74
  4982.5  198.85  4985.3  198.35  4988.5  198.85  5056.3  199.28  5098.7  200.33
  5158.7  200.76  5339.1  201.02  5664.4  203.69  5848.2  204.43  5945.7  205.39
  6244.2  208.55  6272.5  209.34  6399.8  210.95  6413.9  211.58  6668.5  216.96
#Mann=9,-1,0
  4117.0    0.05       0  4555.0     0.1       0  4661.1    0.08       0
  4767.1     0.1       0  4944.1    0.05       0  4982.5   0.035       0
  4988.5    0.05       0  5158.7     0.1       0  5945.7    0.05       0
Bank Sta=4982.5,4988.5
Exp/Cntr=0.3,0.1

Type RM Length L Ch R = 1,34578,506,506,506
BEGIN DESCRIPTION:
UNT051 IN SPCR 42.0
END DESCRIPTION:
XS GIS Cut Line= 2
      2279962.22     13321602.99      2278895.59     13322492.71
#Sta/Elev= 30
  4499.2  206.18  4611.2  205.14  4703.6  203.46  4711.4  203.67  4746.6  203.19
  4753.1  203.36  4845.5  201.11  4902.8  200.20  4937.9  198.27  4952.2  196.91
  4998.7  196.39  5001.5  195.89  5004.7  196.39  5030.3  197.63  5079.8  198.54
  5194.3  199.23  5215.2  198.92  5264.6  199.35  5314.1  199.31  5377.9  200.07
  5414.3  199.90  5520.8  200.98  5562.7  200.97  5598.9  201.61  5669.4  202.01
  5698.1  202.61  5733.2  202.81  5761.8  203.55  5833.3  204.43  5888.2  205.57
#Mann=3,-1,0
  4499.2    0.05       0  4998.7   0.035       0  5004.7    0.05       0
Bank Sta=4998.7,5004.7
Exp/Cntr=0.3,0.1

Type RM Length L Ch R = 1,34072,423,423,423
BEGIN DESCRIPTION:
UNT051 IN SPCR 41.0
END DESCRIPTION:
XS GIS Cut Line= 3
      2279826.81     13321259.22      2279415.36     13321389.43
      2278689.20     13322220.12
#Sta/Elev= 30
  4128.2  205.03  4371.3  202.22  4441.9  200.94  4515.3  200.73  4546.8  199.94
  4563.4  199.87  4570.0  199.48  4584.3  199.52  4598.5  199.15  4690.6  198.42
  4825.4  198.31  4903.2  197.52  4960.1  196.00  4967.7  195.40  4992.3  195.17
  4995.0  194.67  4998.3  195.17  5066.4  195.96  5074.0  196.37  5193.9  197.69
  5207.9  198.19  5258.2  198.77  5293.3  199.71  5321.8  199.94  5336.0  200.51
  5350.3  200.59  5505.9  204.31  5562.9  205.76  5583.7  206.61  5663.1  208.46
#Mann=3,-1,0
  4128.2    0.05       0  4992.3    0.03       0  4998.3    0.05       0
Bank Sta=4992.3,4998.3
Exp/Cntr=0.3,0.1

Type RM Length L Ch R = 1,33649,611,611,611
BEGIN DESCRIPTION:
UNT051 IN SPCR 40.0
END DESCRIPTION:
XS GIS Cut Line= 2
      2279248.67     13321009.25      2278368.49     13321988.39
#Sta/Elev= 30
  4291.8  199.06  4354.8  199.10  4361.5  198.46  4375.7  197.97  4389.9  198.14
  4510.3  197.08  4630.6  197.37  4644.8  197.11  4687.4  197.68  4779.4  197.44
  4822.0  196.96  4893.0  195.01  4970.7  195.18  4996.1  194.30  4998.9  193.80
  5002.1  194.30  5041.6  194.70  5062.7  196.04  5112.0  196.96  5119.5  197.50
  5162.1  198.64  5189.7  199.82  5317.5  202.95  5352.7  203.43  5409.5  204.97
  5466.3  207.00  5487.2  206.94  5579.4  209.78  5600.8  210.21  5608.4  210.00
#Mann=3,-1,0
  4291.8    0.05       0  4996.1    0.03       0  5002.1    0.05       0
Bank Sta=4996.1,5002.1
Exp/Cntr=0.3,0.1

Type RM Length L Ch R = 1,33038,798,798,798
BEGIN DESCRIPTION:
UNT051 IN SPCR 39.0
END DESCRIPTION:
XS GIS Cut Line= 2
      2278707.02     13320566.54      2278009.11     13321727.98
#Sta/Elev= 30
  4394.5  199.57  4423.1  199.95  4460.1  199.71  4481.4  199.94  4576.6  199.07
  4598.0  199.14  4613.6  198.71  4619.4  199.00  4634.9  198.63  4730.1  198.08
  4889.5  194.92  4932.2  193.51  4969.1  193.54  4997.2  193.02  5000.0  192.52
  5003.2  193.02  5138.2  194.18  5159.5  194.79  5304.9  196.15  5377.1  197.30
  5509.3  200.23  5530.6  200.22  5567.6  201.57  5573.4  201.41  5619.9  202.58
  5625.8  203.10  5641.4  202.95  5647.2  203.47  5668.6  203.68  5749.5  205.76
#Mann=3,-1,0
  4394.5    0.05       0  4997.2   0.035       0  5003.2    0.05       0
Bank Sta=4997.2,5003.2
Exp/Cntr=0.3,0.1

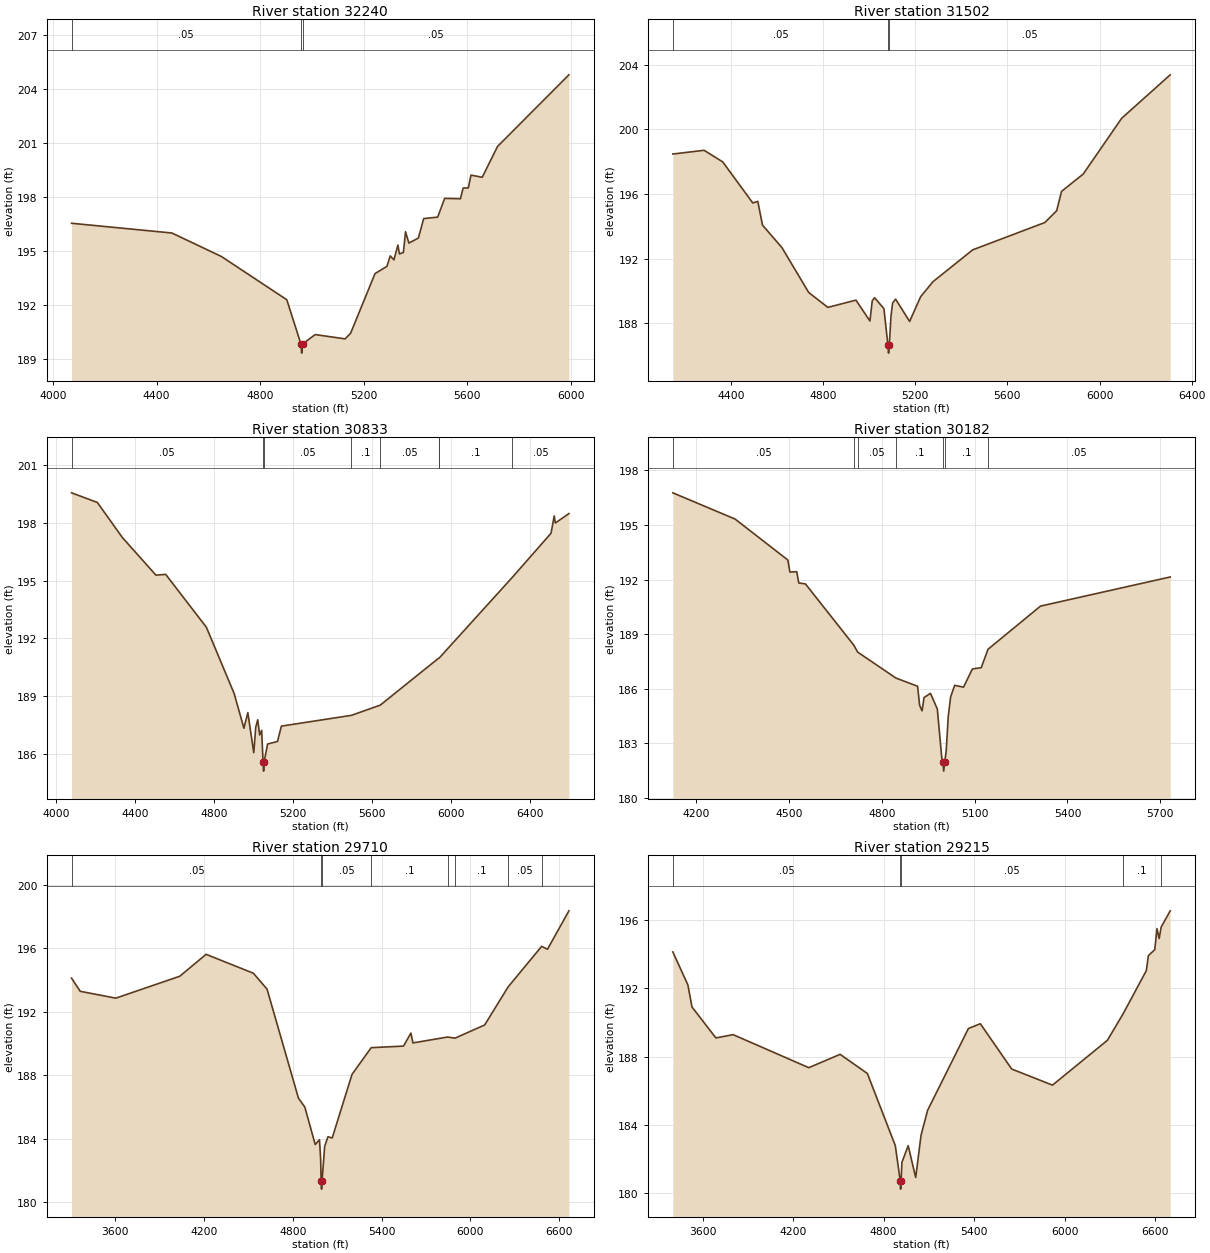
Type RM Length L Ch R = 1,32240,738,738,738
BEGIN DESCRIPTION:
UNT051 IN SPCR 38.0
END DESCRIPTION:
XS GIS Cut Line= 4
      2278160.15     13320035.26      2277873.70     13320561.30
      2277472.66     13321201.93      2277571.62     13321759.23
#Sta/Elev= 30
  4071.6  196.54  4459.2  196.00  4650.1  194.70  4902.9  192.30  4957.6  189.84
  4960.4  189.34  4963.6  189.84  5012.5  190.37  5128.0  190.13  5149.3  190.44
  5243.6  193.75  5289.5  194.15  5302.4  194.73  5316.6  194.51  5332.0  195.33
  5337.9  194.84  5353.2  194.92  5361.4  196.07  5374.4  195.44  5411.0  195.72
  5431.6  196.80  5485.6  196.88  5512.6  197.92  5573.6  197.90  5583.7  198.49
  5604.0  198.50  5614.2  199.21  5657.7  199.09  5716.8  200.80  5992.4  204.77
#Mann=3,-1,0
  4071.6    0.05       0  4957.6   0.035       0  4963.6    0.05       0
Bank Sta=4957.6,4963.6
Exp/Cntr=0.3,0.1

Type RM Length L Ch R = 1,31502,669,669,669
BEGIN DESCRIPTION:
UNT051 IN SPCR 37.0
END DESCRIPTION:
XS GIS Cut Line= 3
      2277170.57     13319852.98      2276946.61     13321191.51
      2277376.40     13321868.70
#Sta/Elev= 30
  4147.7  198.47  4283.4  198.70  4364.5  197.98  4494.8  195.44  4516.6  195.54
  4536.9  194.07  4621.3  192.68  4737.6  189.90  4820.8  188.98  4942.5  189.43
  5003.3  188.14  5013.4  189.39  5023.6  189.58  5064.1  188.90  5081.4  186.65
  5084.2  186.15  5087.4  186.65  5094.6  188.42  5101.9  189.26  5114.8  189.49
  5175.7  188.11  5223.4  189.64  5277.1  190.57  5449.4  192.54  5762.3  194.23
  5814.0  194.96  5835.2  196.16  5929.2  197.23  6096.1  200.68  6306.9  203.37
#Mann=3,-1,0
  4147.7    0.05       0  5081.4    0.03       0  5087.4    0.05       0
Bank Sta=5081.4,5087.4
Exp/Cntr=0.3,0.1

Type RM Length L Ch R = 1,30833,651,651,651
BEGIN DESCRIPTION:
UNT051 IN SPCR 36.0
END DESCRIPTION:
XS GIS Cut Line= 4
      2276904.96     13320009.21      2276436.20     13320472.76
      2276410.16     13321675.89      2276087.25     13322248.79
#Sta/Elev= 30
  4078.9  199.57  4209.6  199.07  4336.9  197.24  4506.6  195.29  4556.1  195.33
  4762.3  192.58  4903.1  189.13  4952.3  187.33  4972.3  188.14  5002.3  186.06
  5012.3  187.39  5022.3  187.77  5032.3  186.98  5042.3  187.22  5049.3  185.60
  5052.1  185.10  5055.3  185.60  5072.3  186.51  5122.3  186.64  5142.3  187.44
  5497.0  188.00  5643.1  188.53  5938.8  190.97  5939.1  190.97  5942.0  190.98
  6312.8  195.18  6508.7  197.47  6524.7  198.37  6530.4  198.00  6599.2  198.49
#Mann=9,-1,0
  4078.9    0.05       0  5049.3    0.03       0  5055.3    0.05       0
  5497.0     0.1       0  5643.1    0.05       0  5938.8     0.1       0
  5939.1    0.05       0  5942.0     0.1       0  6312.8    0.05       0
Bank Sta=5049.3,5055.3
Exp/Cntr=0.3,0.1

Type RM Length L Ch R = 1,30182,472,472,472
BEGIN DESCRIPTION:
UNT051 IN SPCR 35.0
END DESCRIPTION:
XS GIS Cut Line= 2
      2276566.41     13320212.34      2275333.39     13321242.46
#Sta/Elev= 30
  4125.3  196.76  4326.4  195.32  4496.9  193.07  4503.4  192.41  4525.6  192.43
  4532.1  191.81  4553.6  191.76  4710.2  188.39  4722.0  188.02  4846.0  186.59
  4916.0  186.14  4922.5  185.10  4930.3  184.79  4936.8  185.52  4957.6  185.75
  4979.7  184.89  4994.1  182.20  4997.6  181.98  5000.3  181.48  5003.6  181.98
  5008.4  182.58  5014.9  184.47  5022.7  185.56  5035.7  186.19  5064.3  186.09
  5093.0  187.09  5121.6  187.16  5143.4  188.17  5312.9  190.54  5732.0  192.14
#Mann=7,-1,0
  4125.3    0.05       0  4710.2     0.1       0  4722.0    0.05       0
  4846.0     0.1       0  4997.6    0.07       0  5003.6     0.1       0
  5143.4    0.05       0
Bank Sta=4997.6,5003.6
Exp/Cntr=0.3,0.1

Type RM Length L Ch R = 1,29710,495,495,495
BEGIN DESCRIPTION:
UNT051 IN SPCR 34.0
END DESCRIPTION:
XS GIS Cut Line= 4
      2276793.63     13319110.19      2275968.96     13320075.93
      2275209.41     13320998.24      2274807.92     13321801.22
#Sta/Elev= 30
  3303.8  194.11  3362.7  193.28  3603.1  192.85  4035.8  194.23  4213.5  195.61
  4533.0  194.42  4625.5  193.42  4837.9  186.55  4880.9  185.99  4951.2  183.63
  4979.9  183.93  4987.8  182.75  4991.2  181.32  4994.0  180.82  4997.2  181.32
  5015.4  183.53  5037.3  184.12  5066.0  184.04  5200.1  188.05  5329.5  189.73
  5548.1  189.83  5598.3  190.65  5611.9  190.03  5846.1  190.40  5896.4  190.33
  6096.7  191.16  6255.5  193.56  6481.8  196.11  6521.5  195.93  6666.3  198.35
#Mann=8,-1,0
  3303.8    0.05       0  4991.2   0.035       0  4997.2    0.05       0
  5329.5     0.1       0  5846.1    0.05       0  5896.4     0.1       0
  6255.5    0.05       0  6481.8     0.1       0
Bank Sta=4991.2,4997.2
Exp/Cntr=0.3,0.1

Type RM Length L Ch R = 1,29215,425,425,425
BEGIN DESCRIPTION:
UNT051 IN SPCR 33.0
END DESCRIPTION:
XS GIS Cut Line= 3
      2276283.64     13318784.69      2275524.08     13319848.06
      2274319.80     13321432.07
#Sta/Elev= 30
  3403.3  194.12  3503.1  192.19  3530.2  190.90  3688.6  189.09  3803.0  189.28
  4304.4  187.35  4512.0  188.13  4692.7  187.01  4877.9  182.79  4910.2  180.75
  4913.0  180.25  4916.2  180.75  4921.5  181.81  4963.1  182.79  5013.0  180.93
  5048.4  183.40  5092.0  184.86  5362.4  189.64  5441.4  189.92  5649.3  187.27
  5919.6  186.33  6283.5  188.95  6387.8  190.50  6541.3  193.02  6555.2  193.90
  6597.5  194.25  6612.1  195.48  6626.6  194.90  6639.9  195.57  6699.9  196.52
#Mann=5,-1,0
  3403.3    0.05       0  4910.2   0.035       0  4916.2    0.05       0
  6387.8     0.1       0  6639.9    0.05       0
Bank Sta=4910.2,4916.2
Exp/Cntr=0.3,0.1