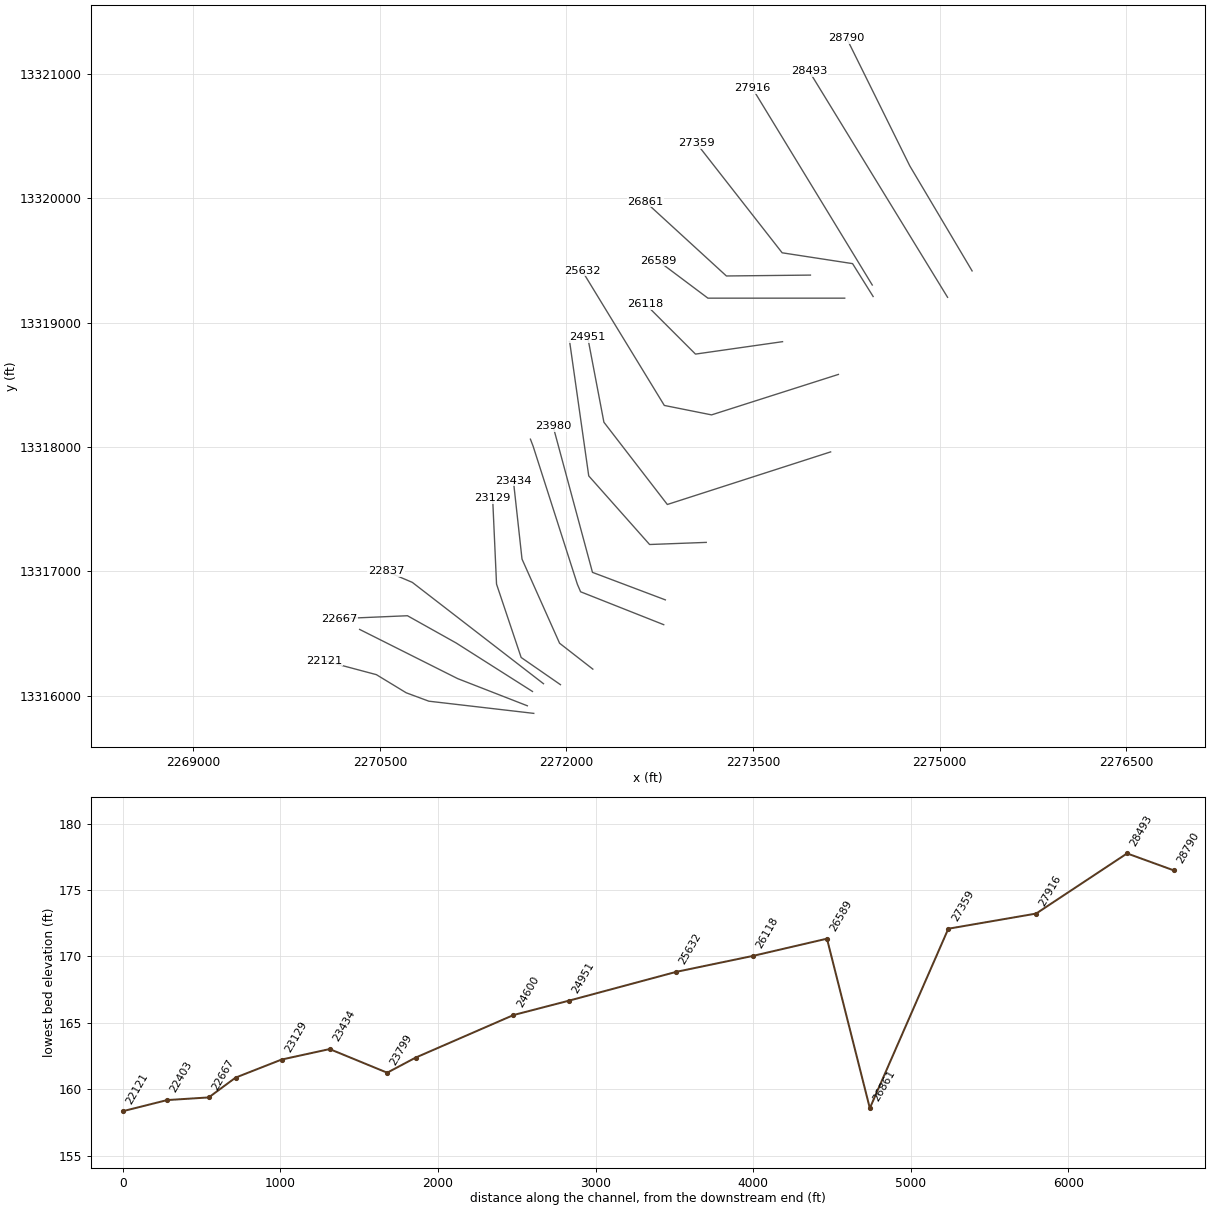
HEC-RAS study UNT051 IN SPCR.prj: UNT051 IN SPCR Base Level Engineering

--- UNT051 IN SPCR.g01 (geometry) --- (continued)

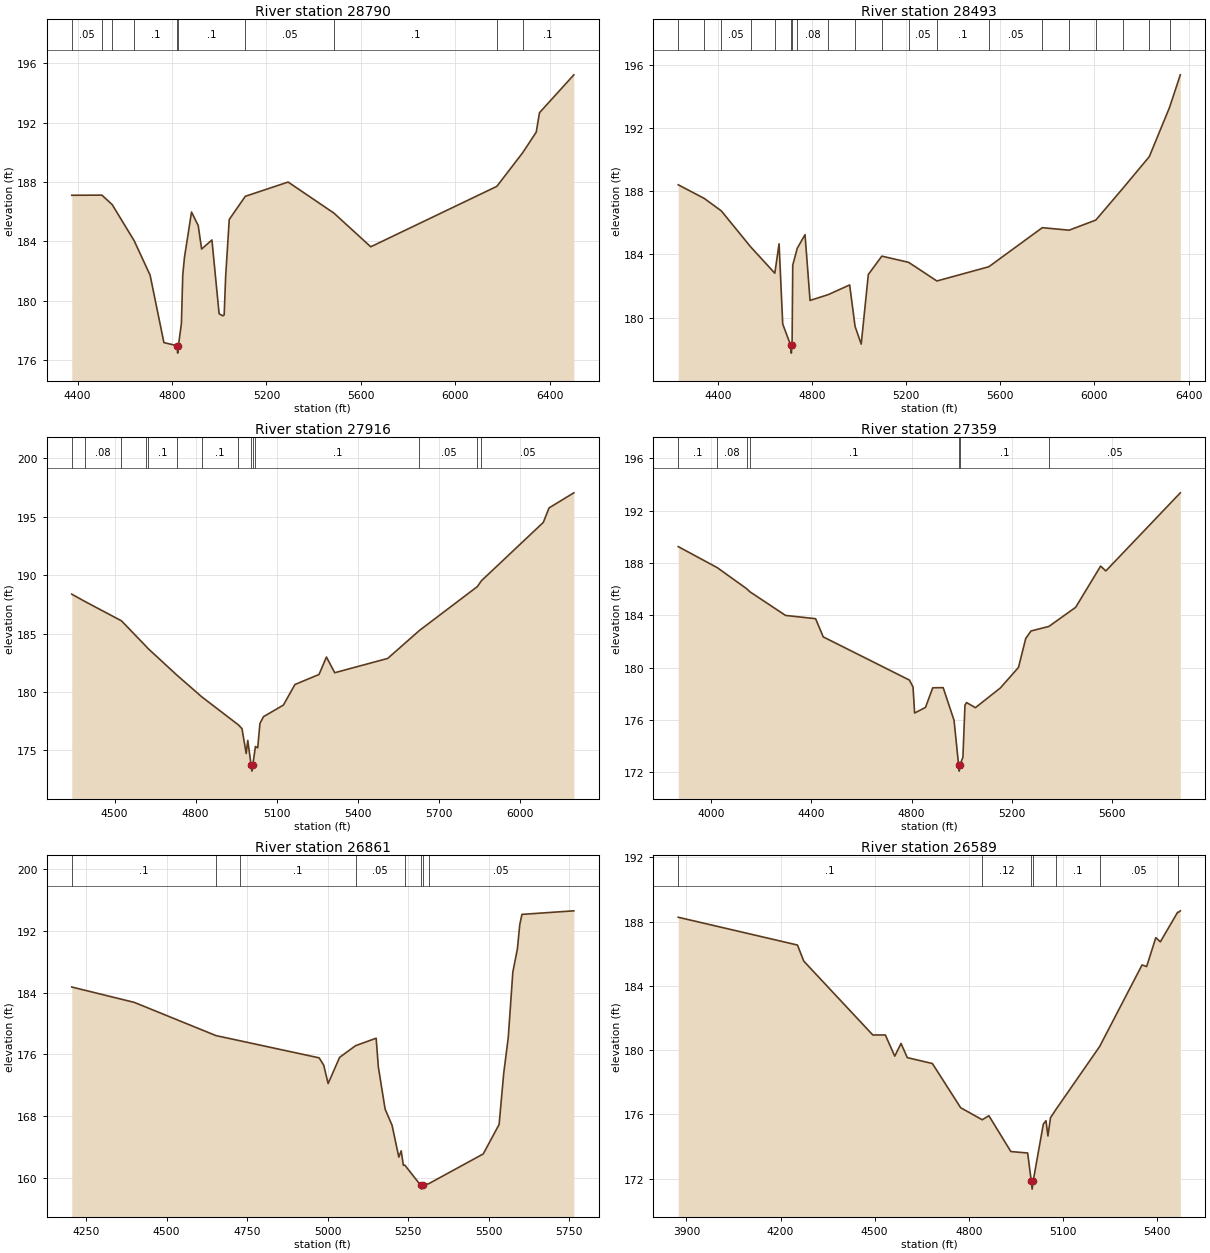
Type RM Length L Ch R = 1,28790,297,297,297
BEGIN DESCRIPTION:
UNT051 IN SPCR 32.0
END DESCRIPTION:
XS GIS Cut Line= 3
      2275261.91     13319416.10      2274760.60     13320261.34
      2274253.44     13321287.31
#Sta/Elev= 30
  4375.2  187.11  4502.8  187.12  4546.5  186.48  4639.9  184.04  4707.1  181.73
  4765.6  177.19  4821.1  176.98  4823.8  176.48  4827.1  176.98  4839.7  178.48
  4845.5  181.75  4852.8  182.94  4882.6  185.98  4910.9  185.07  4925.4  183.49
  4969.0  184.10  4999.5  179.13  5015.1  178.99  5020.9  179.05  5027.2  181.65
  5042.4  185.48  5110.4  187.04  5291.9  188.00  5485.8  185.91  5641.9  183.64
  6176.2  187.71  6285.4  189.97  6343.1  191.36  6356.9  192.67  6502.4  195.22
#Mann=10,-1,0
  4375.2    0.05       0  4502.8     0.1       0  4546.5    0.05       0
  4639.9     0.1       0  4821.1    0.07       0  4827.1     0.1       0
  5110.4    0.05       0  5485.8     0.1       0  6176.2    0.05       0
  6285.4     0.1       0
Bank Sta=4821.1,4827.1
Exp/Cntr=0.3,0.1

Type RM Length L Ch R = 1,28493,577,577,577
BEGIN DESCRIPTION:
UNT051 IN SPCR 31.0
END DESCRIPTION:
XS GIS Cut Line= 2
      2275064.69     13319203.61      2273951.36     13321023.47
#Sta/Elev= 30
  4231.4  188.40  4341.7  187.54  4414.5  186.75  4539.5  184.47  4641.8  182.81
  4659.9  184.67  4675.4  179.60  4709.1  178.26  4711.9  177.76  4715.1  178.26
  4718.0  183.32  4737.2  184.39  4770.2  185.25  4791.5  181.09  4869.2  181.46
  4959.8  182.07  4982.8  179.45  5008.9  178.33  5039.1  182.73  5096.5  183.89
  5210.2  183.50  5330.5  182.32  5551.2  183.22  5778.5  185.69  5892.2  185.53
  6005.8  186.17  6121.5  188.19  6233.1  190.18  6319.3  193.30  6364.8  195.35
#Mann=20,-1,0
  4231.4    0.05       0  4341.7    0.08       0  4414.5    0.05       0
  4539.5    0.08       0  4641.8     0.1       0  4709.1    0.04       0
  4715.1     0.1       0  4737.2    0.08       0  4869.2     0.1       0
  4982.8    0.05       0  5096.5     0.1       0  5210.2    0.05       0
  5330.5     0.1       0  5551.2    0.05       0  5778.5    0.05       0
  5892.2     0.1       0  6005.8    0.05       0  6121.5    0.08       0
  6233.1     0.1       0  6319.3    0.08       0
Bank Sta=4709.1,4715.1
Exp/Cntr=0.3,0.1

Type RM Length L Ch R = 1,27916,557,557,557
BEGIN DESCRIPTION:
Mapping XS b8983fee
END DESCRIPTION:
XS GIS Cut Line= 2
      2274459.03     13319302.72      2273493.76     13320887.96
#Sta/Elev= 30
  4342.0  188.37  4390.2  187.75  4525.7  186.09  4615.3  183.94  4624.0  183.72
  4730.8  181.44  4822.4  179.59  4957.8  177.19  4971.3  176.86  4986.8  174.74
  4992.6  175.86  5005.1  173.73  5007.9  173.23  5011.1  173.73  5020.9  175.34
  5029.4  175.22  5037.6  177.31  5050.8  177.89  5124.3  178.88  5167.0  180.64
  5256.0  181.50  5283.5  182.99  5314.1  181.65  5509.8  182.87  5627.0  185.26
  5841.4  189.02  5856.0  189.51  6085.1  194.51  6106.4  195.75  6198.0  197.04
#Mann=14,-1,0
  4342.0     0.1       0  4390.2    0.08       0  4525.7    0.05       0
  4615.3    0.08       0  4624.0     0.1       0  4730.8    0.08       0
  4822.4     0.1       0  4957.8    0.08       0  5005.1    0.07       0
  5011.1    0.08       0  5020.9     0.1       0  5627.0    0.05       0
  5841.4    0.08       0  5856.0    0.05       0
Bank Sta=5005.1,5011.1
Exp/Cntr=0.3,0.1

Type RM Length L Ch R = 1,27359,498,498,498
BEGIN DESCRIPTION:
Mapping XS aa9f5a0f
END DESCRIPTION:
XS GIS Cut Line= 4
      2274466.15     13319210.23      2274300.69     13319474.76
      2273734.64     13319561.82      2273046.87     13320441.94
#Sta/Elev= 30
  3869.3  189.25  4025.1  187.64  4142.2  186.03  4154.1  185.81  4297.2  183.99
  4417.0  183.74  4447.4  182.35  4790.9  179.05  4805.3  178.53  4811.7  176.53
  4855.1  176.96  4884.0  178.46  4925.6  178.47  4969.0  175.97  4986.9  172.59
  4989.6  172.09  4992.9  172.59  5004.3  173.15  5012.4  177.13  5018.8  177.33
  5054.1  176.94  5153.8  178.45  5225.9  180.02  5254.8  182.23  5275.6  182.80
  5347.2  183.15  5453.8  184.61  5553.3  187.76  5574.1  187.39  5871.0  193.36
#Mann=7,-1,0
  3869.3     0.1       0  4025.1    0.08       0  4142.2    0.05       0
  4154.1     0.1       0  4986.9    0.07       0  4992.9     0.1       0
  5347.2    0.05       0
Bank Sta=4986.9,4992.9
Exp/Cntr=0.3,0.1

Type RM Length L Ch R = 1,26861,272,272,272
BEGIN DESCRIPTION:
UNT051 IN SPCR 30.0
END DESCRIPTION:
XS GIS Cut Line= 3
      2273962.02     13319382.44      2273286.28     13319375.40
      2272635.43     13319972.01
#Sta/Elev= 30
  4205.6  184.71  4399.9  182.72  4653.2  178.43  4726.9  177.77  4973.7  175.55
  4987.8  174.60  5001.5  172.23  5037.2  175.62  5086.9  177.13  5150.6  178.09
  5157.4  174.38  5178.4  168.92  5200.0  166.83  5220.9  162.72  5228.3  163.53
  5235.1  161.66  5239.4  161.69  5288.8  159.08  5291.6  158.58  5294.8  159.08
  5313.8  159.28  5483.0  163.13  5532.3  166.94  5546.5  173.52  5560.7  178.18
  5574.9  186.64  5589.1  189.65  5596.4  192.77  5603.2  194.10  5764.3  194.56
#Mann=8,-1,0
  4205.6     0.1       0  4653.2    0.05       0  4726.9     0.1       0
  5086.9    0.05       0  5239.4     0.1       0  5288.8    0.07       0
  5294.8     0.1       0  5313.8    0.05       0
Bank Sta=5288.8,5294.8
Exp/Cntr=0.3,0.1

Type RM Length L Ch R = 1,26589,471,471,471
BEGIN DESCRIPTION:
UNT051 IN SPCR 29.0
END DESCRIPTION:
XS GIS Cut Line= 3
      2274237.70     13319196.85      2273137.72     13319196.85
      2272737.70     13319496.87
#Sta/Elev= 30
  3874.1  188.27  4254.1  186.54  4274.1  185.54  4494.1  180.94  4534.1  180.94
  4564.1  179.62  4584.1  180.41  4604.1  179.53  4684.1  179.16  4774.1  176.41
  4842.8  175.66  4864.1  175.91  4934.1  173.68  4987.6  173.59  4999.2  171.84
  5002.0  171.34  5005.2  171.84  5037.6  175.39  5046.0  175.60  5052.2  174.65
  5060.5  175.79  5077.4  176.29  5217.0  180.22  5352.2  185.30  5366.8  185.20
  5396.0  187.00  5410.5  186.74  5465.5  188.58  5468.1  188.58  5474.1  188.67
#Mann=8,-1,0
  3874.1     0.1       0  4842.8    0.12       0  4999.2    0.07       0
  5005.2    0.12       0  5077.4     0.1       0  5217.0    0.05       0
  5465.5     0.1       0  5468.1    0.05       0
Bank Sta=4999.2,5005.2
Exp/Cntr=0.3,0.1

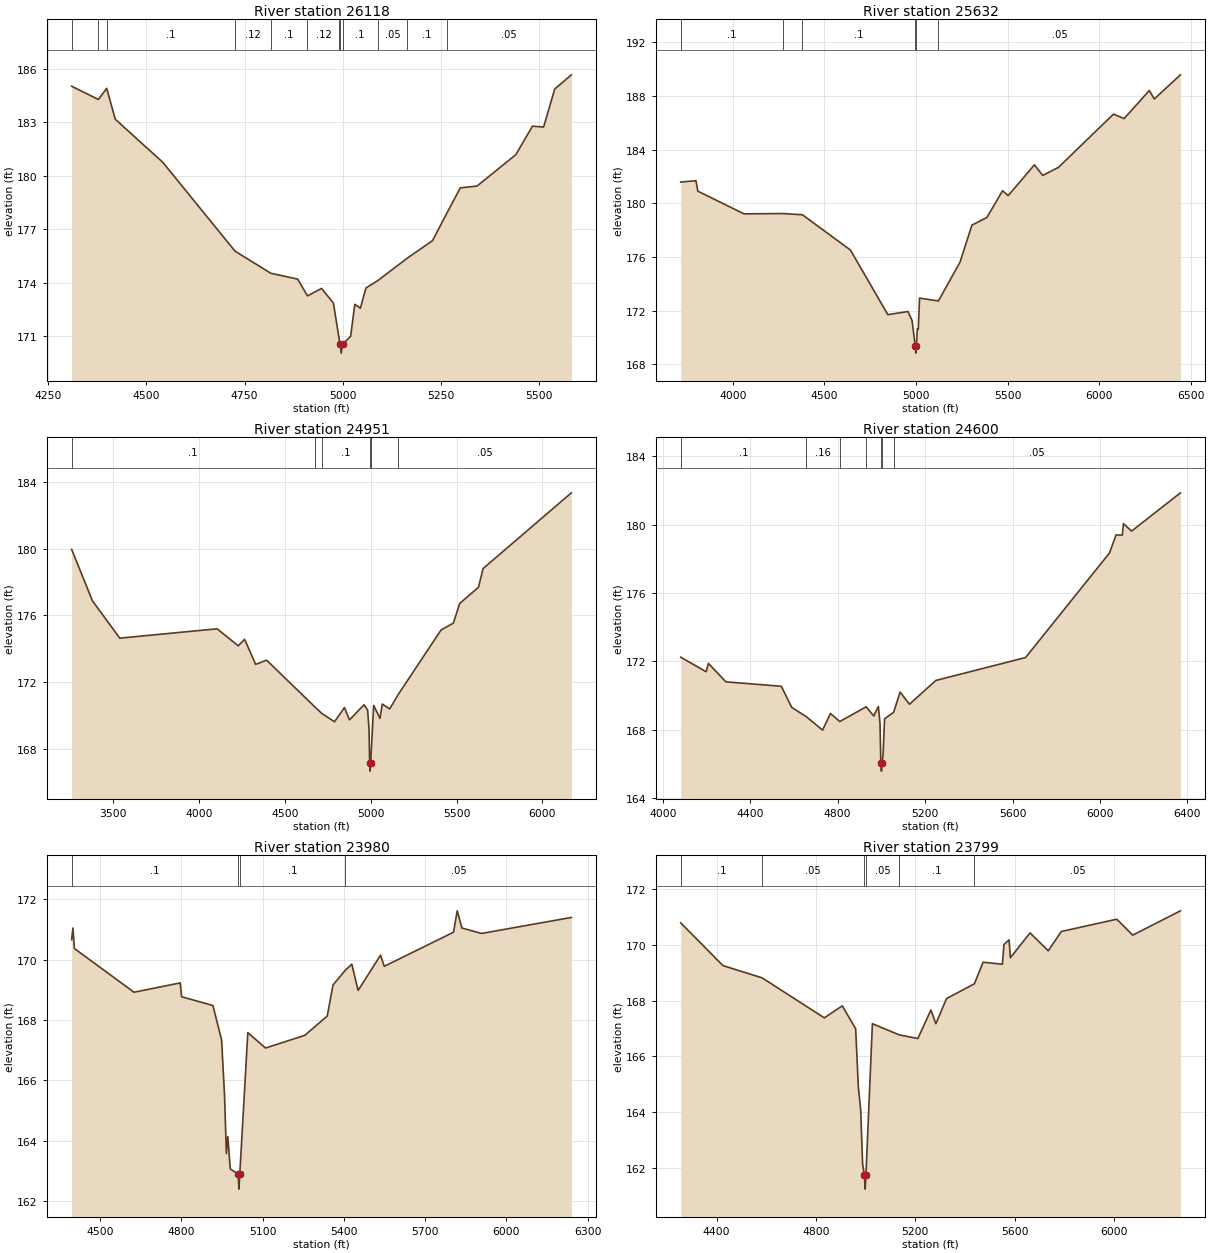
Type RM Length L Ch R = 1,26118,486,486,486
BEGIN DESCRIPTION:
UNT051 IN SPCR 28.0
END DESCRIPTION:
XS GIS Cut Line= 3
      2273737.70     13318846.85      2273037.72     13318746.85
      2272637.70     13319146.88
#Sta/Elev= 30
  4309.6  185.01  4377.7  184.27  4398.9  184.89  4420.7  183.16  4541.9  180.74
  4725.7  175.76  4817.0  174.52  4885.4  174.19  4910.2  173.25  4946.0  173.67
  4976.3  172.85  4991.6  170.75  4993.5  170.54  4996.2  170.04  4999.5  170.54
  5020.2  170.98  5030.8  172.78  5045.0  172.56  5059.1  173.69  5089.5  174.11
  5164.0  175.36  5228.8  176.35  5265.5  177.90  5299.5  179.31  5342.0  179.41
  5440.9  181.17  5483.4  182.77  5511.7  182.72  5539.9  184.85  5582.4  185.65
#Mann=12,-1,0
  4309.6     0.1       0  4377.7    0.16       0  4398.9     0.1       0
  4725.7    0.12       0  4817.0     0.1       0  4910.2    0.12       0
  4991.6     0.1       0  4993.5    0.07       0  4999.5     0.1       0
  5089.5    0.05       0  5164.0     0.1       0  5265.5    0.05       0
Bank Sta=4993.5,4999.5
Exp/Cntr=0.3,0.1

Type RM Length L Ch R = 1,25632,681,681,681
BEGIN DESCRIPTION:
UNT051 IN SPCR 27.0
END DESCRIPTION:
XS GIS Cut Line= 4
      2274186.87     13318583.29      2273166.92     13318257.78
      2272787.15     13318333.73      2272125.28     13319418.77
#Sta/Elev= 30
  3715.3  181.59  3798.4  181.69  3808.9  180.91  4060.8  179.22  4275.6  179.24
  4380.1  179.15  4642.2  176.52  4846.3  171.71  4956.5  171.94  4978.9  171.26
  4996.3  169.34  4999.0  168.84  5002.3  169.34  5007.5  170.65  5012.6  170.63
  5019.7  172.94  5122.6  172.73  5240.3  175.61  5305.7  178.38  5387.4  178.95
  5472.7  180.94  5503.6  180.58  5646.9  182.87  5692.3  182.08  5778.6  182.69
  6078.6  186.65  6136.7  186.32  6274.2  188.41  6301.4  187.78  6444.2  189.58
#Mann=6,-1,0
  3715.3     0.1       0  4275.6    0.16       0  4380.1     0.1       0
  4996.3    0.07       0  5002.3     0.1       0  5122.6    0.05       0
Bank Sta=4996.3,5002.3
Exp/Cntr=0.3,0.1

Type RM Length L Ch R = 1,24951,351,351,351
BEGIN DESCRIPTION:
Mapping XS 7c5a5ea7
END DESCRIPTION:
XS GIS Cut Line= 4
      2274124.38     13317960.05      2272811.41     13317536.86
      2272301.43     13318198.76      2272171.26     13318882.11
#Sta/Elev= 30
  3258.2  179.96  3379.1  176.88  3538.4  174.64  4105.7  175.20  4228.4  174.18
  4265.7  174.57  4329.8  173.07  4393.9  173.32  4673.8  170.53  4715.2  170.13
  4789.2  169.63  4847.3  170.48  4876.3  169.74  4961.4  170.65  4982.2  170.33
  4990.4  169.19  4993.7  167.17  4996.5  166.67  4999.7  167.17  5017.5  170.61
  5054.3  169.83  5067.4  170.69  5110.9  170.40  5158.4  171.23  5409.8  175.13
  5481.5  175.54  5518.5  176.72  5627.9  177.69  5654.6  178.81  6168.9  183.35
#Mann=6,-1,0
  3258.2     0.1       0  4673.8    0.16       0  4715.2     0.1       0
  4993.7    0.07       0  4999.7     0.1       0  5158.4    0.05       0
Bank Sta=4993.7,4999.7
Exp/Cntr=0.3,0.1

Type RM Length L Ch R = 1,24600,620,620,620
BEGIN DESCRIPTION:
Mapping XS 8b4a7899
END DESCRIPTION:
XS GIS Cut Line= 4
      2273124.16     13317231.93      2272668.88     13317214.86
      2272179.46     13317766.88      2272025.80     13318848.18
#Sta/Elev= 30
  4082.4  172.25  4198.9  171.40  4208.9  171.89  4289.0  170.81  4542.6  170.55
  4590.0  169.32  4656.9  168.77  4731.3  167.99  4767.3  168.96  4809.8  168.49
  4930.6  169.35  4965.5  168.81  4986.4  169.37  4993.9  168.37  4997.6  166.09
  5000.4  165.59  5003.6  166.09  5008.1  166.58  5014.8  168.65  5056.1  169.03
  5085.9  170.21  5128.6  169.50  5249.0  170.89  5659.5  172.23  6043.3  178.34
  6073.6  179.40  6102.2  179.39  6107.3  180.06  6144.3  179.62  6367.9  181.86
#Mann=7,-1,0
  4082.4     0.1       0  4656.9    0.16       0  4809.8     0.1       0
  4930.6    0.16       0  4997.6    0.07       0  5003.6    0.16       0
  5056.1    0.05       0
Bank Sta=4997.6,5003.6
Exp/Cntr=0.3,0.1

Type RM Length L Ch R = 1,23980,181,181,181
BEGIN DESCRIPTION:
Mapping XS 77705507
END DESCRIPTION:
XS GIS Cut Line= 3
      2272795.44     13316769.46      2272209.46     13316990.83
      2271892.66     13318166.91
#Sta/Elev= 30
  4395.1  170.66  4399.9  171.05  4405.3  170.37  4625.4  168.92  4795.8  169.23
  4801.1  168.77  4916.5  168.48  4948.5  167.34  4959.2  165.53  4966.2  163.57
  4971.5  164.13  4980.6  163.06  5009.7  162.89  5012.4  162.39  5015.7  162.89
  5045.3  167.58  5110.6  167.07  5255.6  167.49  5338.4  168.13  5359.7  169.16
  5405.2  169.65  5429.2  169.85  5452.4  168.98  5535.2  170.15  5549.0  169.78
  5804.5  170.91  5818.2  171.62  5835.5  171.05  5908.0  170.87  6239.5  171.40
#Mann=4,-1,0
  4395.1     0.1       0  5009.7    0.07       0  5015.7     0.1       0
  5405.2    0.05       0
Bank Sta=5009.7,5015.7
Exp/Cntr=0.3,0.1

Type RM Length L Ch R = 1,23799,365,365,365
BEGIN DESCRIPTION:
Mapping XS 3db65801
END DESCRIPTION:
XS GIS Cut Line= 5
      2272782.42     13316569.81      2272113.97     13316834.58
      2272087.93     13316895.35      2271732.03     13318006.46
      2271710.53     13318062.36
#Sta/Elev= 30
  4255.4  170.78  4425.5  169.25  4583.3  168.81  4833.6  167.38  4905.8  167.81
  4959.6  166.99  4970.7  164.88  4979.9  164.09  4987.7  162.14  4995.1  161.75
  4997.8  161.25  5001.1  161.75  5027.1  167.17  5135.1  166.77  5210.1  166.64
  5262.6  167.66  5282.7  167.17  5325.6  168.07  5437.8  168.60  5472.6  169.37
  5550.3  169.30  5556.6  170.00  5577.2  170.17  5582.5  169.53  5661.6  170.42
  5735.1  169.78  5787.6  170.47  6010.8  170.91  6075.1  170.34  6267.1  171.21
#Mann=6,-1,0
  4255.4     0.1       0  4583.3    0.05       0  4995.1   0.035       0
  5001.1    0.05       0  5135.1     0.1       0  5437.8    0.05       0
Bank Sta=4995.1,5001.1
Exp/Cntr=0.3,0.1

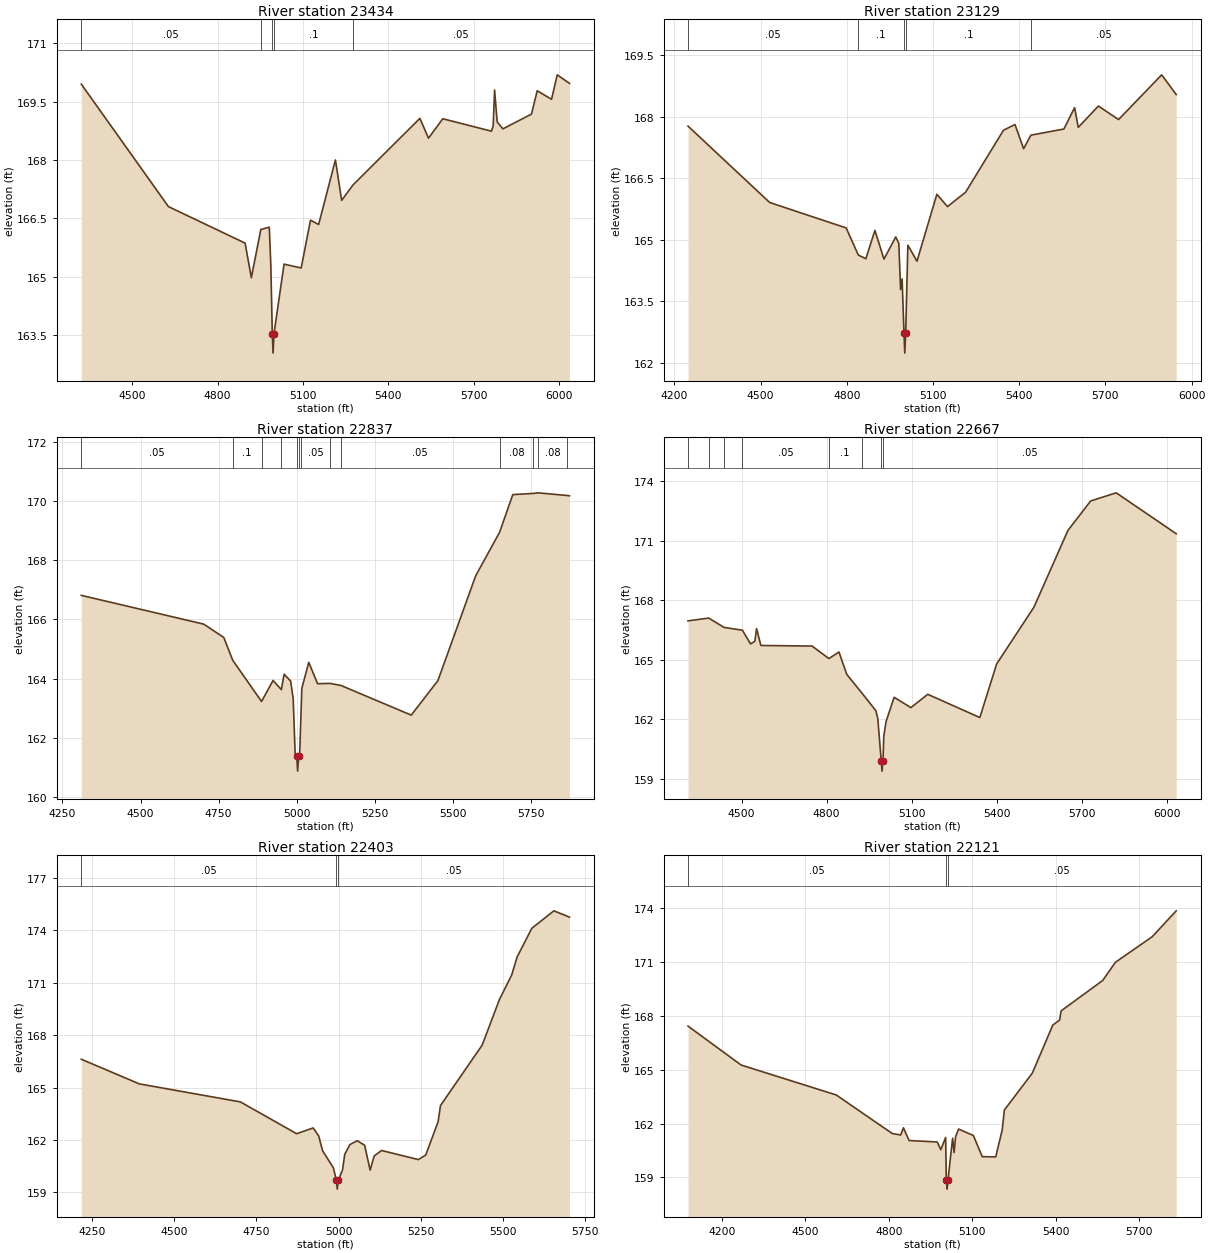
Type RM Length L Ch R = 1,23434,305,305,305
BEGIN DESCRIPTION:
Mapping XS 2b3e9bc1
END DESCRIPTION:
XS GIS Cut Line= 4
      2272212.42     13316212.24      2271945.05     13316420.58
      2271642.97     13317097.66      2271573.52     13317729.59
#Sta/Elev= 30
  4321.0  169.95  4627.2  166.80  4896.8  165.86  4918.7  164.97  4952.0  166.21
  4981.8  166.27  4987.3  165.27  4992.3  163.53  4995.1  163.03  4998.3  163.53
  5033.7  165.32  5093.9  165.22  5126.6  166.45  5155.3  166.34  5214.3  168.00
  5236.2  166.96  5276.5  167.36  5511.2  169.07  5541.4  168.56  5591.7  169.06
  5762.7  168.74  5768.8  168.87  5773.8  169.80  5782.8  168.98  5803.0  168.80
  5903.6  169.18  5923.7  169.78  5974.0  169.56  5994.1  170.19  6037.1  169.97
#Mann=5,-1,0
  4321.0    0.05       0  4952.0     0.1       0  4992.3    0.07       0
  4998.3     0.1       0  5276.5    0.05       0
Bank Sta=4992.3,4998.3
Exp/Cntr=0.3,0.1

Type RM Length L Ch R = 1,23129,292,292,292
BEGIN DESCRIPTION:
Mapping XS 5afc44d4
END DESCRIPTION:
XS GIS Cut Line= 4
      2271952.01     13316087.24      2271636.02     13316306.00
      2271438.11     13316896.27      2271406.85     13317587.27
#Sta/Elev= 30
  4247.7  167.77  4531.7  165.91  4798.0  165.29  4840.1  164.63  4866.4  164.54
  4898.0  165.23  4929.5  164.53  4970.4  165.07  4981.0  164.92  4987.3  163.79
  4992.6  164.05  4999.1  162.74  5001.8  162.24  5005.1  162.74  5012.6  164.87
  5044.3  164.48  5113.5  166.11  5150.4  165.81  5213.5  166.16  5345.3  167.67
  5385.3  167.81  5415.3  167.22  5440.7  167.55  5555.5  167.70  5592.8  168.22
  5605.5  167.74  5675.6  168.26  5745.7  167.93  5895.8  169.02  5946.3  168.54
#Mann=5,-1,0
  4247.7    0.05       0  4840.1     0.1       0  4999.1    0.07       0
  5005.1     0.1       0  5440.7    0.05       0
Bank Sta=4999.1,5005.1
Exp/Cntr=0.3,0.1

Type RM Length L Ch R = 1,22837,170,170,170
BEGIN DESCRIPTION:
Mapping XS f89822a6
END DESCRIPTION:
XS GIS Cut Line= 3
      2271815.63     13316094.99      2270761.02     13316910.16
      2270550.94     13316999.70
#Sta/Elev= 30
  4310.7  166.81  4702.1  165.84  4766.4  165.39  4795.0  164.62  4887.1  163.23
  4924.0  163.94  4950.4  163.63  4959.3  164.15  4980.1  163.92  4988.3  163.32
  4994.6  161.46  4999.8  161.38  5002.5  160.88  5005.8  161.38  5009.1  161.47
  5014.2  163.12  5015.9  163.67  5038.1  164.55  5066.4  163.83  5105.9  163.84
  5141.2  163.77  5365.9  162.77  5451.0  163.93  5572.0  167.47  5648.5  168.94
  5690.7  170.21  5756.6  170.25  5770.8  170.27  5864.7  170.18  5872.0  170.17
#Mann=13,-1,0
  4310.7    0.05       0  4795.0     0.1       0  4887.1    0.05       0
  4950.4     0.1       0  4999.8    0.07       0  5005.8     0.1       0
  5014.2    0.05       0  5105.9     0.1       0  5141.2    0.05       0
  5648.5    0.08       0  5756.6    0.05       0  5770.8    0.08       0
  5864.7    0.05       0
Bank Sta=4999.8,5005.8
Exp/Cntr=0.3,0.1

Type RM Length L Ch R = 1,22667,264,264,264
BEGIN DESCRIPTION:
Mapping XS beab28c2
END DESCRIPTION:
XS GIS Cut Line= 4
      2271727.12     13316032.47      2271112.55     13316423.08
      2270721.92     13316641.83      2270176.33     13316618.45
#Sta/Elev= 30
  4311.2  166.96  4384.4  167.10  4438.2  166.63  4503.0  166.49  4531.7  165.80
  4547.0  165.93  4552.9  166.57  4568.1  165.72  4748.9  165.69  4808.1  165.06
  4843.7  165.39  4871.3  164.26  4923.1  163.35  4974.0  162.43  4980.6  162.04
  4992.8  159.89  4995.6  159.39  4998.8  159.89  5001.7  161.14  5009.6  161.88
  5038.2  163.11  5097.4  162.59  5156.8  163.26  5340.5  162.09  5399.9  164.79
  5531.4  167.65  5651.5  171.52  5731.5  173.00  5821.6  173.41  6033.2  171.35
#Mann=8,-1,0
  4311.2    0.08       0  4384.4    0.05       0  4438.2    0.08       0
  4503.0    0.05       0  4808.1     0.1       0  4923.1    0.05       0
  4992.8   0.035       0  4998.8    0.05       0
Bank Sta=4992.8,4998.8
Exp/Cntr=0.3,0.1

Type RM Length L Ch R = 1,22403,282,282,282
BEGIN DESCRIPTION:
Mapping XS b79fd5c9
END DESCRIPTION:
XS GIS Cut Line= 3
      2271685.80     13315917.35      2271125.61     13316135.86
      2270337.42     13316531.69
#Sta/Elev= 30
  4218.3  166.62  4394.6  165.21  4701.6  164.18  4872.6  162.36  4922.8  162.69
  4939.6  162.23  4951.5  161.38  4984.2  160.41  4993.3  159.69  4996.0  159.19
  4999.3  159.69  5012.1  160.30  5018.7  161.18  5034.5  161.74  5056.8  161.96
  5079.1  161.70  5095.9  160.28  5108.2  161.09  5130.6  161.40  5242.5  160.88
  5264.8  161.14  5302.5  163.05  5309.6  163.97  5436.4  167.43  5488.6  170.03
  5525.8  171.43  5542.5  172.47  5587.2  174.11  5654.2  175.11  5701.6  174.75
#Mann=3,-1,0
  4218.3    0.05       0  4993.3   0.035       0  4999.3    0.05       0
Bank Sta=4993.3,4999.3
Exp/Cntr=0.3,0.1

Type RM Length L Ch R = 1,22121,57,57,57
BEGIN DESCRIPTION:
Mapping XS bdf662e4
END DESCRIPTION:
XS GIS Cut Line= 5
      2271737.50     13315856.26      2270893.80     13315954.33
      2270711.50     13316022.04      2270471.92     13316167.88
      2270054.69     13316279.00
#Sta/Elev= 30
  4077.7  167.44  4268.8  165.27  4611.0  163.60  4812.4  161.45  4842.6  161.37
  4852.7  161.77  4872.8  161.06  4974.2  160.98  4986.9  160.55  5004.5  161.23
  5006.8  158.85  5009.6  158.35  5012.8  158.85  5029.5  161.19  5034.9  160.39
  5040.2  161.27  5050.9  161.70  5104.2  161.34  5136.1  160.16  5184.6  160.15
  5207.9  161.65  5215.6  162.76  5316.3  164.82  5389.9  167.50  5414.5  167.78
  5419.7  168.29  5569.8  169.99  5615.1  171.00  5747.9  172.43  5833.8  173.87
#Mann=3,-1,0
  4077.7    0.05       0  5006.8   0.035       0  5012.8    0.05       0
Bank Sta=5006.8,5012.8
Exp/Cntr=0.3,0.1