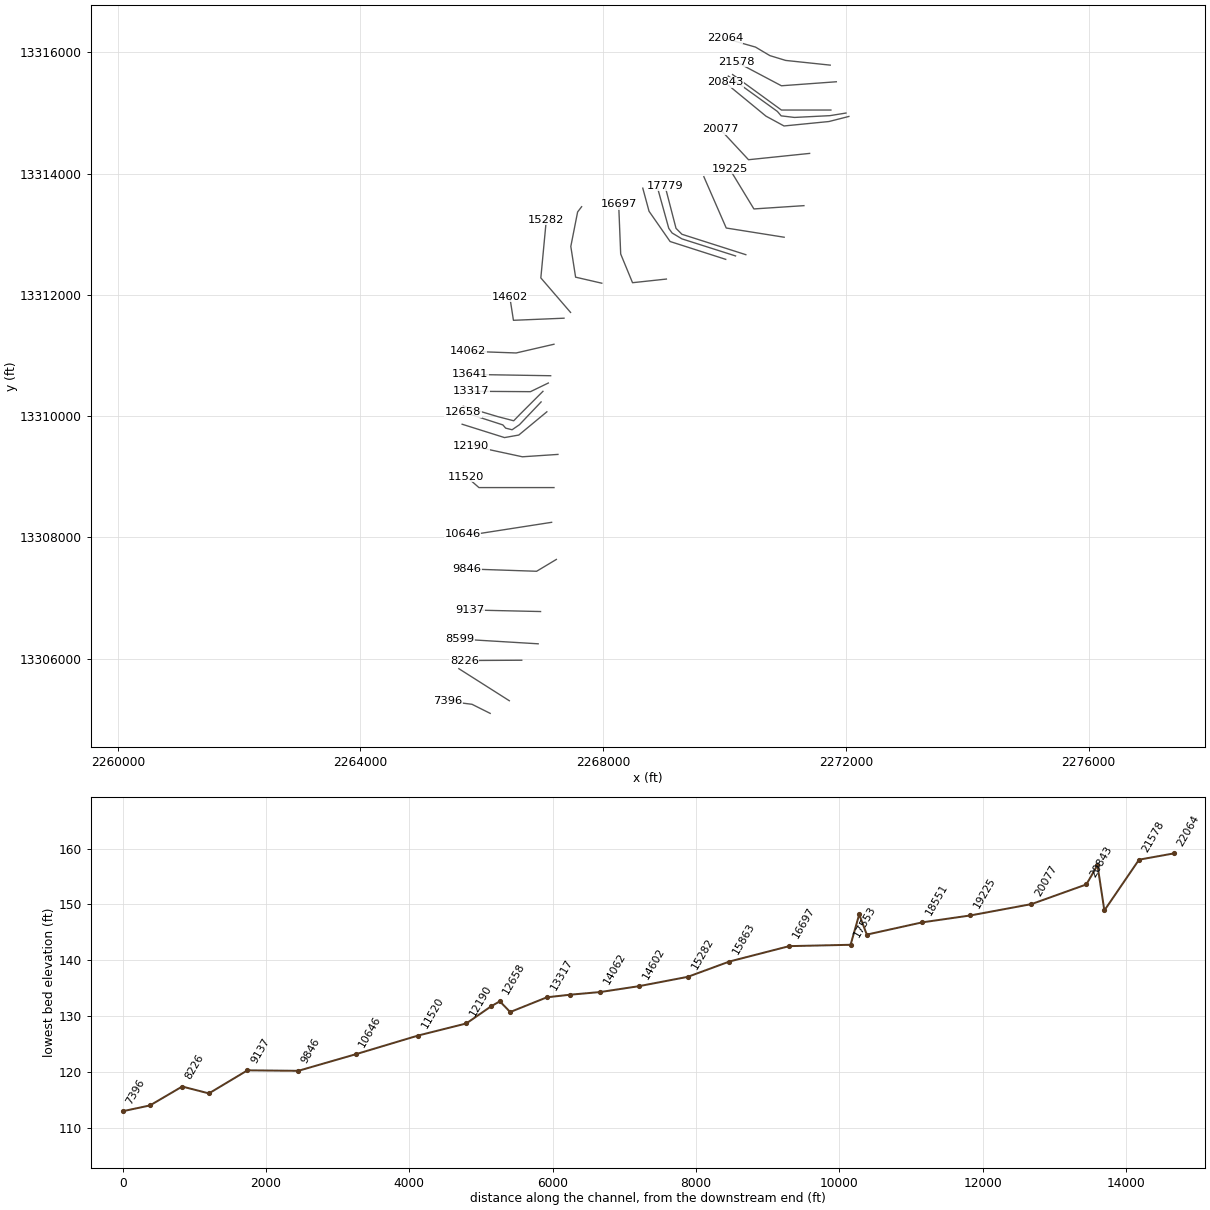
HEC-RAS study UNT051 IN SPCR.prj: UNT051 IN SPCR Base Level Engineering

--- UNT051 IN SPCR.g01 (geometry) --- (continued)

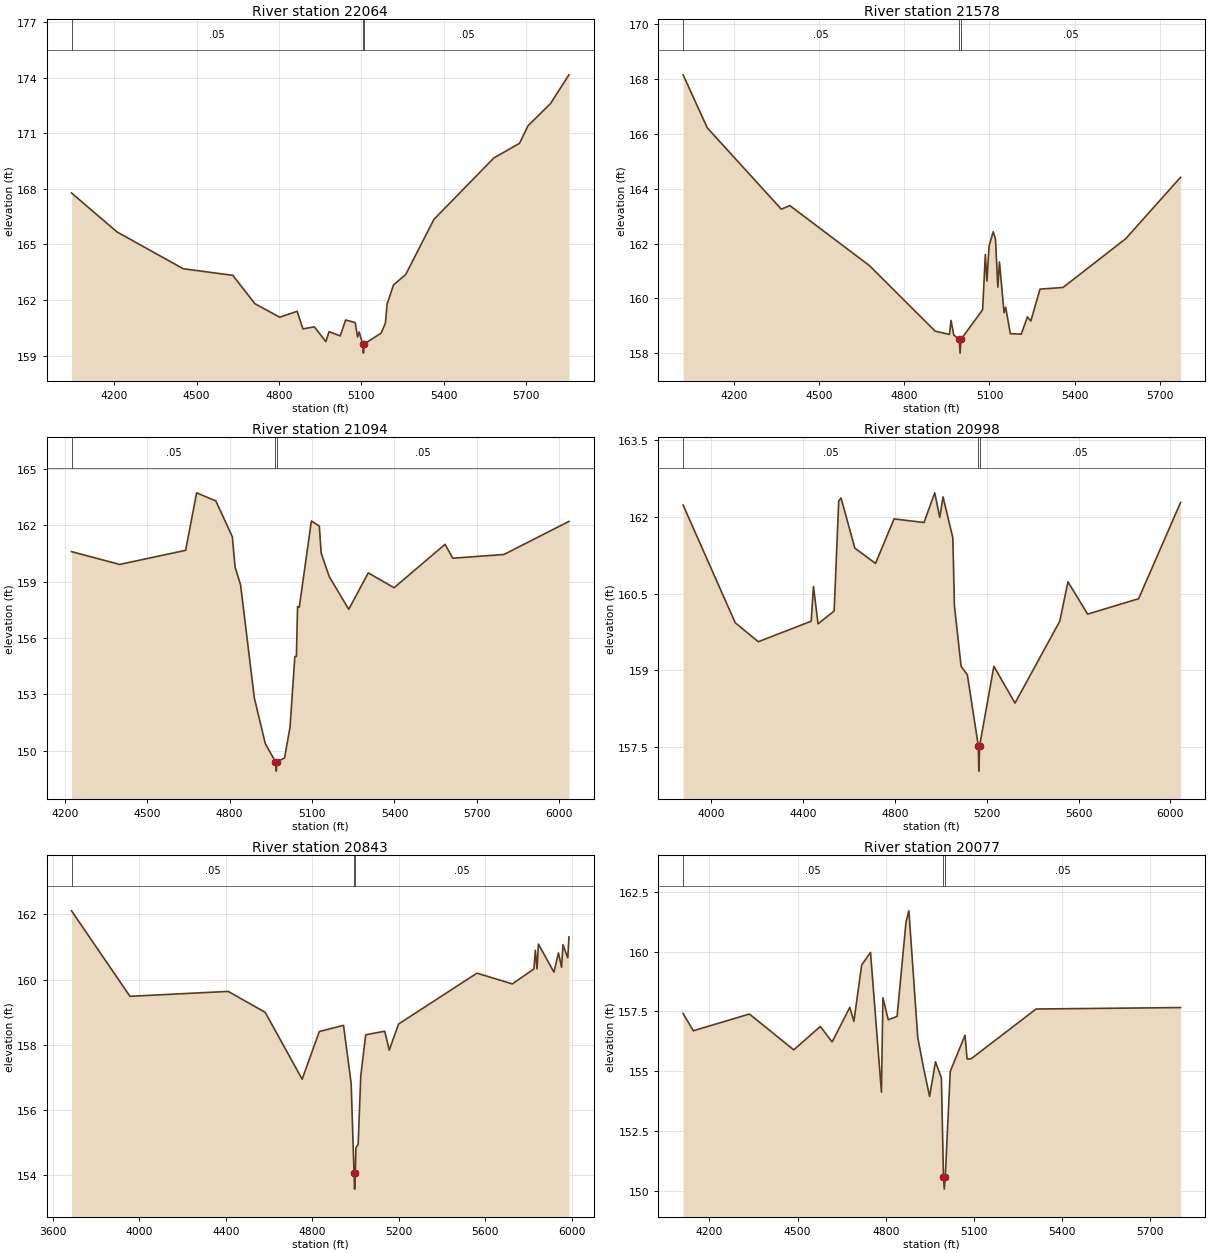
Type RM Length L Ch R = 1,22064,486,486,486
BEGIN DESCRIPTION:
Mapping XS 5b216182
END DESCRIPTION:
XS GIS Cut Line= 5
      2271742.09     13315787.20      2271007.53     13315864.84
      2270747.65     13315944.12      2270509.79     13316085.08
      2270004.48     13316229.18
#Sta/Elev= 30
  4044.7  167.78  4210.0  165.68  4451.3  163.69  4632.3  163.33  4712.8  161.80
  4803.1  161.07  4866.8  161.39  4887.7  160.44  4929.5  160.55  4971.3  159.75
  4982.9  160.29  5023.6  160.06  5043.3  160.92  5078.2  160.78  5086.9  160.00
  5092.7  160.27  5105.4  159.63  5108.1  159.13  5111.4  159.63  5172.7  160.21
  5188.3  160.75  5194.5  161.78  5217.7  162.81  5262.4  163.38  5364.9  166.35
  5583.3  169.67  5676.8  170.46  5708.0  171.41  5789.9  172.61  5857.0  174.16
#Mann=3,-1,0
  4044.7    0.05       0  5105.4   0.035       0  5111.4    0.05       0
Bank Sta=5105.4,5111.4
Exp/Cntr=0.3,0.1

Type RM Length L Ch R = 1,21578,484,484,484
BEGIN DESCRIPTION:
UNT051 IN SPCR 26.0
END DESCRIPTION:
XS GIS Cut Line= 3
      2271842.45     13315512.93      2270937.72     13315446.85
      2270192.05     13315841.48
#Sta/Elev= 30
  4021.7  168.14  4106.7  166.21  4367.3  163.25  4397.4  163.38  4678.2  161.19
  4908.8  158.81  4959.0  158.69  4964.7  159.20  4974.1  158.67  4993.7  158.51
  4996.5  158.01  4999.7  158.51  5075.9  159.59  5085.4  161.60  5091.0  160.63
  5098.6  161.91  5113.0  162.43  5121.2  162.15  5129.4  160.41  5135.0  161.33
  5151.4  159.48  5157.0  159.68  5173.4  158.72  5211.7  158.70  5233.7  159.33
  5245.6  159.18  5277.8  160.34  5358.8  160.40  5580.1  162.18  5772.5  164.41
#Mann=3,-1,0
  4021.7    0.05       0  4993.7   0.035       0  4999.7    0.05       0
Bank Sta=4993.7,4999.7
Exp/Cntr=0.3,0.1

Type RM Length L Ch R = 1,21094,96,96,96
BEGIN DESCRIPTION:
UNT051 IN SPCR 25.0
END DESCRIPTION:
XS GIS Cut Line= 3
      2271752.96     13315046.85      2270937.72     13315046.85
      2270133.06     13315632.06
#Sta/Elev= 30
  4224.7  160.60  4399.9  159.92  4639.9  160.67  4679.9  163.73  4749.9  163.30
  4809.9  161.39  4819.9  159.78  4839.9  158.83  4889.9  152.82  4929.9  150.38
  4966.9  149.42  4969.7  148.92  4972.9  149.42  4999.9  149.62  5019.9  151.26
  5037.4  155.02  5043.0  155.02  5047.3  157.68  5053.5  157.64  5097.5  162.23
  5126.5  161.96  5133.1  160.53  5162.4  159.28  5233.5  157.53  5304.6  159.47
  5398.5  158.68  5584.0  160.99  5612.2  160.25  5798.5  160.45  6034.9  162.21
#Mann=3,-1,0
  4224.7    0.05       0  4966.9   0.035       0  4972.9    0.05       0
Bank Sta=4966.9,4972.9
Exp/Cntr=0.3,0.1

Type RM Length L Ch R = 1,20998,155,155,155
BEGIN DESCRIPTION:
Mapping XS b1218c10
END DESCRIPTION:
XS GIS Cut Line= 6
      2272001.71     13314997.28      2271736.43     13314954.01
      2271152.38     13314924.67      2270933.63     13314950.72
      2270871.13     13315023.63      2270062.15     13315606.85
#Sta/Elev= 30
  3877.4  162.23  4104.4  159.93  4205.0  159.56  4435.3  159.96  4445.3  160.64
  4465.3  159.91  4535.4  160.16  4555.4  162.31  4565.4  162.37  4625.5  161.39
  4715.6  161.09  4796.4  161.96  4927.0  161.89  4973.6  162.47  4995.5  161.99
  5009.8  162.39  5052.5  161.59  5059.5  160.26  5088.5  159.08  5116.0  158.91
  5163.3  157.53  5166.0  157.03  5169.3  157.53  5231.3  159.08  5323.4  158.36
  5518.4  159.96  5554.0  160.73  5639.9  160.10  5862.0  160.40  6044.6  162.28
#Mann=3,-1,0
  3877.4    0.05       0  5163.3   0.035       0  5169.3    0.05       0
Bank Sta=5163.3,5169.3
Exp/Cntr=0.3,0.1

Type RM Length L Ch R = 1,20843,766,766,766
BEGIN DESCRIPTION:
Mapping XS b8fa97e0
END DESCRIPTION:
XS GIS Cut Line= 5
      2272049.40     13314940.84      2271721.23     13314857.33
      2270980.51     13314784.05      2270683.63     13314945.51
      2270005.77     13315503.03
#Sta/Elev= 30
  3687.5  162.11  3957.5  159.49  4411.5  159.64  4582.3  159.00  4753.2  156.95
  4832.5  158.41  4944.4  158.60  4979.7  156.82  4992.9  154.08  4995.6  153.58
  4998.9  154.08  5001.6  154.84  5012.0  154.96  5024.1  157.05  5046.8  158.31
  5134.8  158.42  5155.6  157.84  5198.7  158.64  5561.0  160.20  5724.6  159.87
  5824.3  160.33  5830.7  160.90  5838.6  160.33  5845.1  161.09  5916.8  160.23
  5937.6  160.82  5952.0  160.38  5958.5  161.07  5980.7  160.67  5986.1  161.31
#Mann=3,-1,0
  3687.5    0.05       0  4992.9   0.035       0  4998.9    0.05       0
Bank Sta=4992.9,4998.9
Exp/Cntr=0.3,0.1

Type RM Length L Ch R = 1,20077,852,852,852
BEGIN DESCRIPTION:
UNT051 IN SPCR 23.0
END DESCRIPTION:
XS GIS Cut Line= 3
      2271402.25     13314331.52      2270395.33     13314227.36
      2269931.41     13314725.90
#Sta/Elev= 30
  4110.4  157.41  4145.1  156.69  4336.1  157.39  4486.9  155.89  4577.4  156.87
  4617.6  156.22  4677.9  157.67  4691.7  157.08  4718.2  159.44  4748.3  159.97
  4785.5  154.12  4790.5  158.07  4808.6  157.15  4838.8  157.29  4869.0  161.23
  4879.0  161.71  4909.2  156.40  4929.3  155.11  4949.4  153.94  4969.5  155.39
  4989.6  154.72  4996.7  150.56  4999.4  150.06  5002.7  150.56  5019.8  154.99
  5070.0  156.50  5077.0  155.51  5090.1  155.51  5311.9  157.60  5803.7  157.66
#Mann=3,-1,0
  4110.4    0.05       0  4996.7   0.035       0  5002.7    0.05       0
Bank Sta=4996.7,5002.7
Exp/Cntr=0.3,0.1

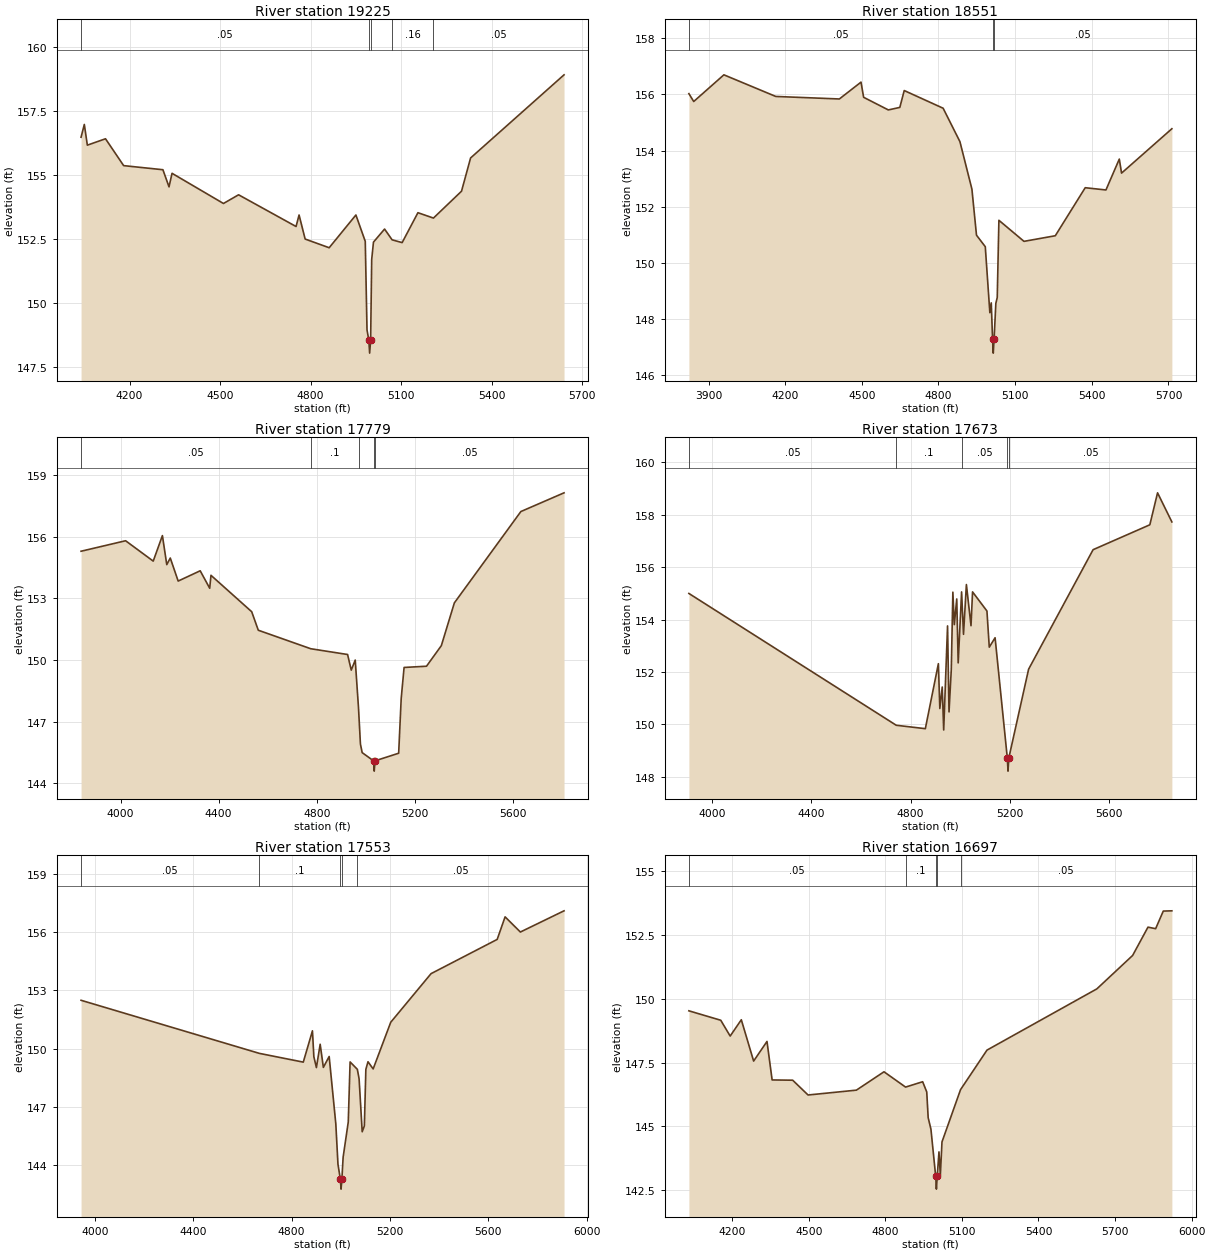
Type RM Length L Ch R = 1,19225,674,674,674
BEGIN DESCRIPTION:
UNT051 IN SPCR 22.0
END DESCRIPTION:
XS GIS Cut Line= 3
      2271308.51     13313469.98      2270483.87     13313415.73
      2270082.58     13314077.32
#Sta/Elev= 30
  4039.3  156.47  4050.1  156.97  4060.1  156.16  4120.3  156.41  4180.4  155.36
  4310.5  155.20  4330.7  154.53  4340.7  155.06  4511.1  153.88  4561.2  154.22
  4751.6  152.98  4761.6  153.43  4781.7  152.49  4861.3  152.15  4949.9  153.43
  4980.9  152.40  4986.7  148.94  4992.7  148.53  4995.4  148.03  4998.7  148.53
  5002.2  151.69  5008.1  152.37  5044.9  152.88  5069.8  152.46  5103.1  152.35
  5155.4  153.52  5206.8  153.31  5299.8  154.36  5329.9  155.66  5639.5  158.91
#Mann=5,-1,0
  4039.3    0.05       0  4992.7   0.035       0  4998.7    0.05       0
  5069.8    0.16       0  5206.8    0.05       0
Bank Sta=4992.7,4998.7
Exp/Cntr=0.3,0.1

Type RM Length L Ch R = 1,18551,772,772,772
BEGIN DESCRIPTION:
UNT051 IN SPCR 21.0
END DESCRIPTION:
XS GIS Cut Line= 3
      2270983.00     13312949.15      2270028.14     13313101.06
      2269659.23     13313947.38
#Sta/Elev= 30
  3823.2  156.03  3842.1  155.75  3960.2  156.70  4163.2  155.93  4412.0  155.84
  4496.8  156.44  4507.0  155.90  4603.7  155.45  4648.7  155.54  4665.9  156.14
  4818.2  155.51  4883.9  154.32  4930.8  152.63  4948.7  150.99  4983.1  150.58
  5001.0  148.23  5006.5  148.58  5011.6  147.29  5014.3  146.79  5017.6  147.29
  5024.4  148.56  5029.9  148.77  5036.4  151.52  5134.6  150.77  5257.1  150.97
  5374.2  152.68  5455.3  152.60  5507.6  153.70  5516.4  153.20  5713.3  154.78
#Mann=3,-1,0
  3823.2    0.05       0  5011.6   0.035       0  5017.6    0.05       0
Bank Sta=5011.6,5017.6
Exp/Cntr=0.3,0.1

Type RM Length L Ch R = 1,17779,106,106,106
BEGIN DESCRIPTION:
Mapping XS 95aa380e
END DESCRIPTION:
XS GIS Cut Line= 4
      2270350.88     13312661.43      2269298.33     13312997.81
      2269200.67     13313095.46      2269017.87     13313800.13
#Sta/Elev= 30
  3838.4  155.29  4020.2  155.80  4132.9  154.81  4170.4  156.05  4188.2  154.64
  4202.5  154.96  4234.7  153.84  4324.6  154.34  4363.4  153.49  4368.6  154.12
  4534.8  152.35  4561.7  151.45  4775.8  150.55  4926.1  150.27  4941.1  149.51
  4957.3  150.00  4970.7  147.67  4978.5  145.92  4985.6  145.50  5032.1  145.10
  5034.8  144.60  5038.1  145.10  5134.6  145.47  5144.9  148.13  5156.7  149.64
  5248.2  149.70  5308.7  150.70  5361.9  152.78  5633.3  157.22  5809.5  158.13
#Mann=5,-1,0
  3838.4    0.05       0  4775.8     0.1       0  4970.7    0.05       0
  5032.1   0.035       0  5038.1    0.05       0
Bank Sta=5032.1,5038.1
Exp/Cntr=0.3,0.1

Type RM Length L Ch R = 1,17673,120,120,120
BEGIN DESCRIPTION:
Mapping XS 3c297da4
END DESCRIPTION:
XS GIS Cut Line= 5
      2270181.50     13312640.64      2269298.33     13312921.85
      2269135.57     13313019.51      2269081.31     13313095.46
      2268885.28     13313802.37
#Sta/Elev= 30
  3908.0  155.00  4742.5  149.97  4859.5  149.84  4912.0  152.32  4917.8  150.61
  4927.5  151.43  4933.4  149.79  4948.9  153.76  4954.8  150.48  4963.9  152.09
  4970.3  155.05  4976.1  153.81  4985.9  154.79  4991.7  152.35  5005.4  155.06
  5013.1  153.44  5024.7  155.34  5043.3  153.77  5049.5  155.06  5107.4  154.33
  5116.8  152.95  5140.2  153.31  5189.4  148.72  5192.2  148.22  5195.4  148.72
  5275.1  152.11  5534.6  156.67  5762.9  157.62  5794.0  158.84  5851.6  157.73
#Mann=5,-1,0
  3908.0    0.05       0  4742.5     0.1       0  5005.4    0.05       0
  5189.4    0.07       0  5195.4    0.05       0
Bank Sta=5189.4,5195.4
Exp/Cntr=0.3,0.1

Type RM Length L Ch R = 1,17553,856,856,856
BEGIN DESCRIPTION:
Mapping XS bb06e312
END DESCRIPTION:
XS GIS Cut Line= 4
      2270019.65     13312584.28      2269103.01     13312878.45
      2268755.79     13313377.58      2268652.73     13313758.38
#Sta/Elev= 30
  3943.2  152.49  4668.8  149.76  4847.4  149.31  4884.7  150.92  4890.4  149.59
  4900.8  149.03  4916.1  150.23  4929.1  149.04  4952.7  149.60  4979.8  146.13
  4988.5  144.06  4998.4  143.28  5001.1  142.78  5004.4  143.28  5009.5  144.42
  5030.4  146.23  5037.9  149.32  5067.4  148.94  5074.5  148.45  5087.1  145.73
  5095.9  146.03  5102.0  148.94  5110.7  149.33  5131.7  148.96  5203.2  151.36
  5367.3  153.86  5636.4  155.62  5668.5  156.78  5730.7  156.00  5908.4  157.09
#Mann=5,-1,0
  3943.2    0.05       0  4668.8     0.1       0  4998.4    0.07       0
  5004.4     0.1       0  5067.4    0.05       0
Bank Sta=4998.4,5004.4
Exp/Cntr=0.3,0.1

Type RM Length L Ch R = 1,16697,834,834,834
BEGIN DESCRIPTION:
Mapping XS 1373133d
END DESCRIPTION:
XS GIS Cut Line= 4
      2269041.83     13312259.36      2268483.85     13312199.23
      2268288.71     13312672.53      2268255.50     13313490.39
#Sta/Elev= 30
  4030.8  149.53  4155.6  149.16  4192.5  148.54  4236.1  149.18  4284.4  147.56
  4336.7  148.33  4356.8  146.82  4437.3  146.81  4497.6  146.23  4686.8  146.42
  4795.0  147.14  4879.5  146.54  4946.4  146.75  4962.4  146.35  4968.0  145.34
  4978.8  144.89  4997.5  143.04  5000.2  142.54  5003.5  143.04  5010.3  144.00
  5015.7  143.08  5022.1  144.39  5094.8  146.44  5198.4  147.99  5628.7  150.39
  5768.8  151.70  5828.9  152.81  5858.9  152.75  5888.9  153.44  5922.5  153.45
#Mann=5,-1,0
  4030.8    0.05       0  4879.5     0.1       0  4997.5    0.07       0
  5003.5     0.1       0  5094.8    0.05       0
Bank Sta=4997.5,5003.5
Exp/Cntr=0.3,0.1

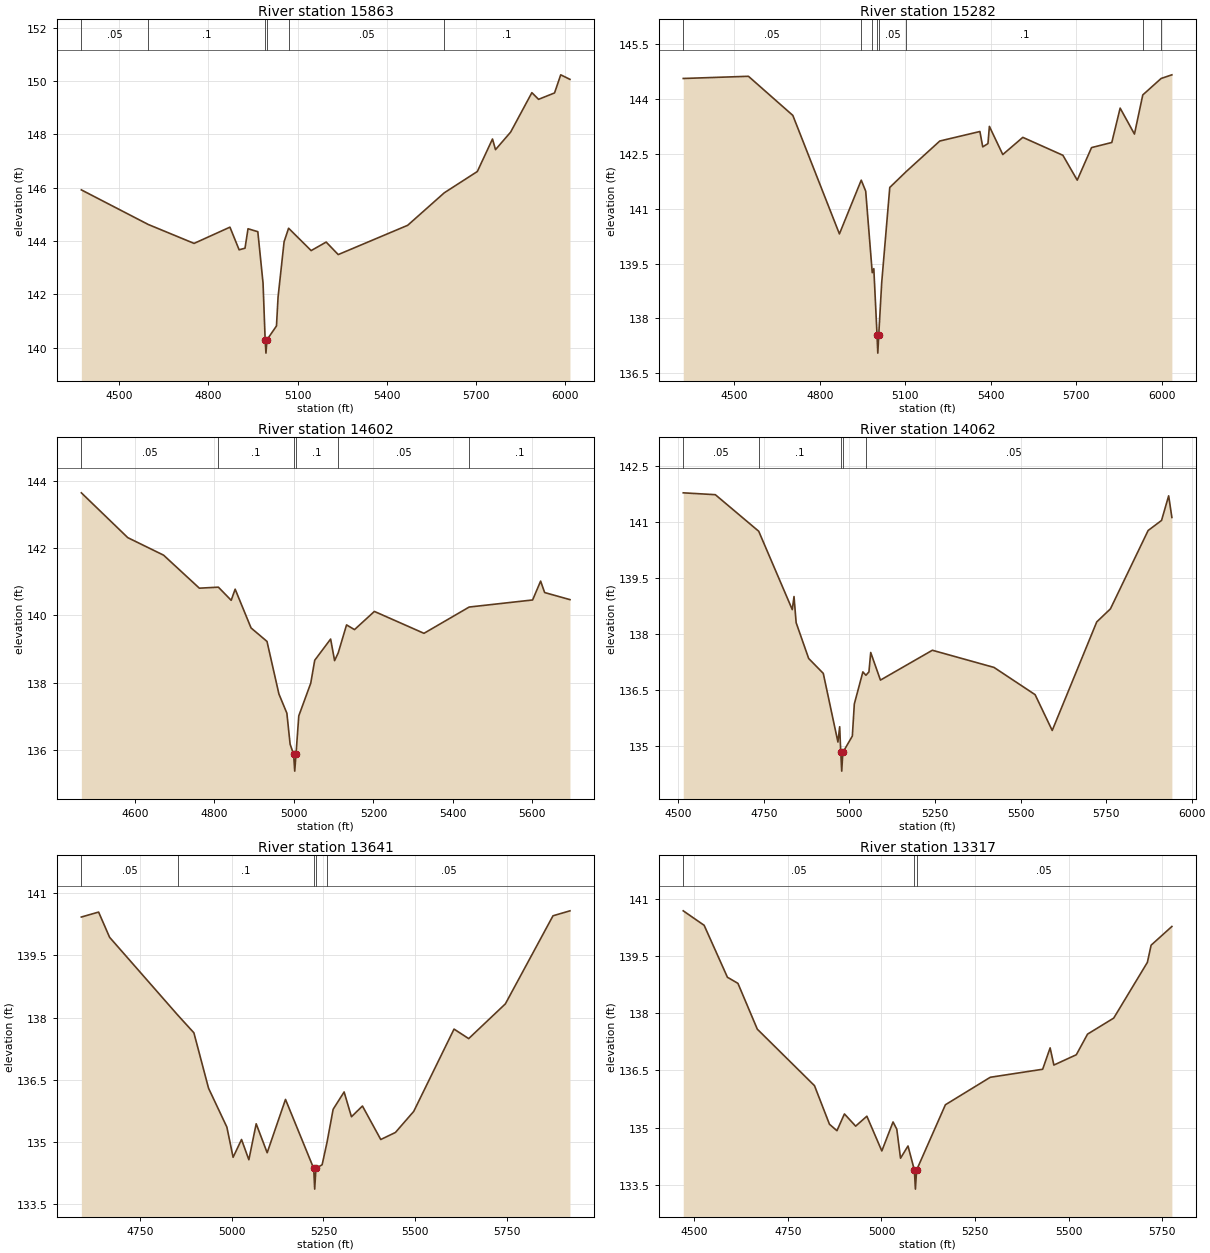
Type RM Length L Ch R = 1,15863,581,581,581
BEGIN DESCRIPTION:
Mapping XS 6faf0082
END DESCRIPTION:
XS GIS Cut Line= 5
      2267977.38     13312190.91      2267545.54     13312290.57
      2267466.66     13312797.09      2267578.76     13313365.88
      2267644.73     13313452.47
#Sta/Elev= 30
  4372.3  145.92  4597.6  144.62  4751.7  143.91  4872.4  144.52  4903.3  143.67
  4923.1  143.73  4933.2  144.46  4966.2  144.35  4983.8  142.42  4990.9  140.29
  4993.6  139.79  4996.9  140.29  5029.0  140.81  5034.4  141.90  5054.6  143.97
  5069.8  144.48  5145.7  143.64  5196.3  143.96  5236.8  143.49  5470.6  144.59
  5593.7  145.81  5705.0  146.61  5756.0  147.83  5766.1  147.43  5817.1  148.09
  5888.5  149.57  5911.1  149.32  5964.8  149.56  5985.6  150.24  6016.7  150.07
#Mann=6,-1,0
  4372.3    0.05       0  4597.6     0.1       0  4990.9    0.07       0
  4996.9     0.1       0  5069.8    0.05       0  5593.7     0.1       0
Bank Sta=4990.9,4996.9
Exp/Cntr=0.3,0.1

Type RM Length L Ch R = 1,15282,680,680,680
BEGIN DESCRIPTION:
Mapping XS e594abf0
END DESCRIPTION:
XS GIS Cut Line= 3
      2267462.53     13311709.29      2266972.60     13312278.11
      2267062.86     13313237.54
#Sta/Elev= 30
  4320.9  144.56  4549.6  144.62  4705.4  143.55  4868.8  140.31  4945.4  141.78
  4961.0  141.48  4984.0  139.25  4989.5  139.36  5000.8  137.55  5003.5  137.05
  5006.8  137.55  5017.2  138.98  5045.5  141.58  5102.5  142.01  5221.0  142.85
  5361.7  143.11  5371.7  142.69  5390.0  142.78  5395.0  143.25  5442.0  142.48
  5512.3  142.95  5652.9  142.46  5703.2  141.78  5753.4  142.67  5824.5  142.81
  5853.8  143.75  5904.0  143.04  5933.2  144.11  5997.5  144.56  6035.3  144.66
#Mann=8,-1,0
  4320.9    0.05       0  4945.4     0.1       0  4984.0    0.05       0
  5000.8   0.035       0  5006.8    0.05       0  5102.5     0.1       0
  5933.2    0.16       0  5997.5     0.1       0
Bank Sta=5000.8,5006.8
Exp/Cntr=0.3,0.1

Type RM Length L Ch R = 1,14602,540,540,540
BEGIN DESCRIPTION:
UNT051 IN SPCR 20.0
END DESCRIPTION:
XS GIS Cut Line= 3
      2267354.39     13311613.85      2266521.05     13311579.13
      2266460.29     13311969.77
#Sta/Elev= 30
  4465.1  143.64  4581.9  142.31  4672.0  141.79  4762.0  140.81  4809.9  140.84
  4842.1  140.45  4852.1  140.78  4892.1  139.63  4932.2  139.23  4962.2  137.67
  4982.2  137.10  4990.4  136.18  4999.2  135.88  5002.0  135.38  5005.2  135.88
  5012.2  137.02  5042.3  137.99  5052.3  138.67  5092.3  139.30  5102.3  138.66
  5111.4  138.89  5132.4  139.72  5152.4  139.58  5202.4  140.12  5327.2  139.47
  5440.9  140.25  5600.5  140.46  5620.7  141.02  5630.8  140.68  5694.5  140.47
#Mann=6,-1,0
  4465.1    0.05       0  4809.9     0.1       0  4999.2    0.07       0
  5005.2     0.1       0  5111.4    0.05       0  5440.9     0.1       0
Bank Sta=4999.2,5005.2
Exp/Cntr=0.3,0.1

Type RM Length L Ch R = 1,14062,421,421,421
BEGIN DESCRIPTION:
UNT051 IN SPCR 19.0
END DESCRIPTION:
XS GIS Cut Line= 3
      2267189.07     13311184.38      2266565.65     13311040.51
      2265778.35     13311068.49
#Sta/Elev= 30
  4514.6  141.79  4608.3  141.74  4735.1  140.76  4833.1  138.66  4838.2  139.01
  4844.4  138.31  4881.0  137.35  4923.7  136.95  4966.5  135.11  4971.6  135.52
  4974.8  134.83  4977.6  134.33  4980.8  134.83  5008.6  135.27  5014.4  136.13
  5039.4  136.99  5048.3  136.90  5057.1  136.99  5062.3  137.51  5090.7  136.77
  5242.4  137.57  5422.5  137.11  5542.6  136.38  5592.6  135.42  5722.7  138.33
  5762.7  138.68  5872.8  140.78  5912.0  141.05  5932.8  141.71  5942.2  141.13
#Mann=6,-1,0
  4514.6    0.05       0  4735.1     0.1       0  4974.8    0.07       0
  4980.8     0.1       0  5048.3    0.05       0  5912.0     0.1       0
Bank Sta=4974.8,4980.8
Exp/Cntr=0.3,0.1

Type RM Length L Ch R = 1,13641,324,324,324
BEGIN DESCRIPTION:
UNT051 IN SPCR 18.0
END DESCRIPTION:
XS GIS Cut Line= 2
      2267134.83     13310665.09      2265801.41     13310686.77
#Sta/Elev= 30
  4589.1  140.43  4636.2  140.55  4666.2  139.94  4852.1  138.06  4896.3  137.63
  4936.3  136.29  4986.3  135.35  5003.3  134.62  5026.3  135.05  5046.3  134.56
  5066.3  135.43  5096.3  134.73  5146.3  136.02  5223.3  134.35  5226.0  133.85
  5229.3  134.35  5246.3  134.44  5259.6  134.98  5276.3  135.78  5306.3  136.20
  5326.3  135.60  5356.3  135.86  5406.3  135.05  5446.3  135.22  5496.3  135.73
  5606.3  137.72  5646.3  137.49  5746.4  138.33  5876.4  140.46  5922.7  140.58
#Mann=5,-1,0
  4589.1    0.05       0  4852.1     0.1       0  5223.3    0.07       0
  5229.3     0.1       0  5259.6    0.05       0
Bank Sta=5223.3,5229.3
Exp/Cntr=0.3,0.1

Type RM Length L Ch R = 1,13317,514,514,514
BEGIN DESCRIPTION:
Mapping XS 4ca686ab
END DESCRIPTION:
XS GIS Cut Line= 3
      2267095.91     13310544.82      2266801.40     13310402.22
      2265822.24     13310408.42
#Sta/Elev= 30
  4470.0  140.68  4525.9  140.30  4588.1  138.94  4616.2  138.78  4668.0  137.58
  4820.9  136.10  4860.9  135.09  4880.9  134.92  4900.9  135.36  4930.9  135.04
  4960.9  135.30  5000.9  134.39  5030.9  135.15  5040.9  134.96  5050.9  134.20
  5070.9  134.52  5087.9  133.89  5090.7  133.39  5093.9  133.89  5170.9  135.60
  5290.9  136.32  5430.9  136.53  5450.9  137.09  5460.9  136.64  5520.9  136.91
  5550.9  137.45  5620.9  137.87  5710.9  139.33  5720.9  139.78  5776.4  140.27
#Mann=3,-1,0
  4470.0    0.05       0  5087.9    0.03       0  5093.9    0.05       0
Bank Sta=5087.9,5093.9
Exp/Cntr=0.3,0.1

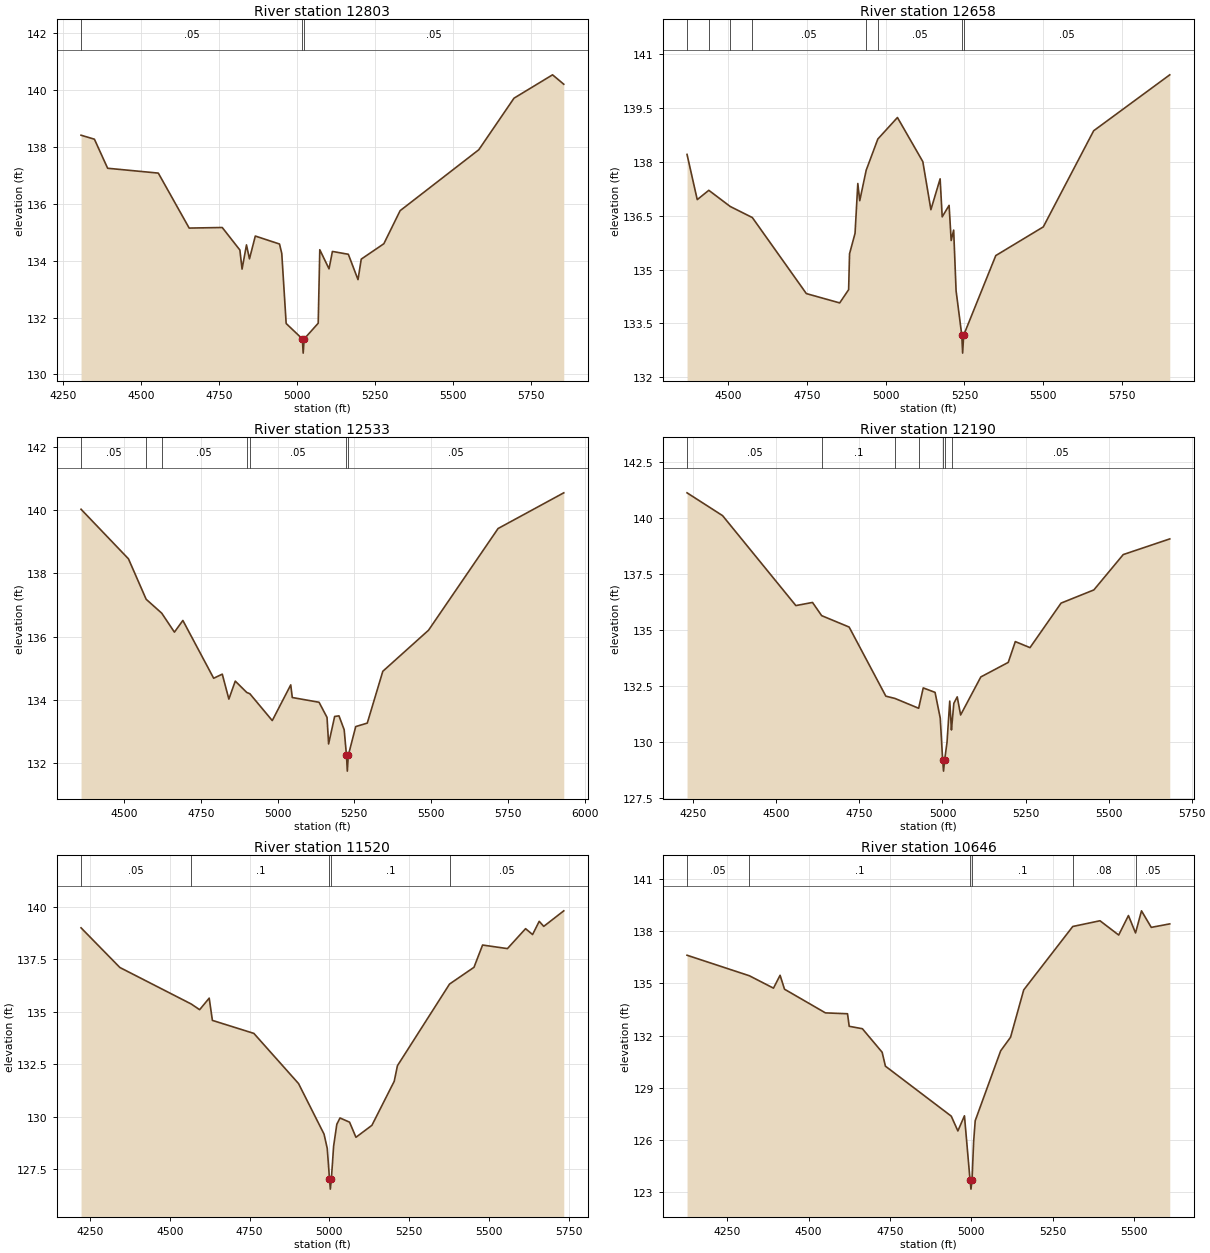
Type RM Length L Ch R = 1,12803,145,145,145
BEGIN DESCRIPTION:
Mapping XS e0735056
END DESCRIPTION:
XS GIS Cut Line= 5
      2267007.45     13310407.77      2266628.04     13310028.36
      2266525.60     13309922.13      2266263.82     13309990.42
      2265694.76     13310161.14
#Sta/Elev= 30
  4307.6  138.40  4350.5  138.26  4392.9  137.24  4555.5  137.07  4654.5  135.14
  4760.6  135.16  4817.2  134.37  4824.2  133.70  4838.4  134.55  4848.0  134.06
  4866.7  134.86  4944.4  134.58  4951.6  134.25  4965.7  131.79  5017.6  131.25
  5020.3  130.75  5023.6  131.25  5068.5  131.80  5073.6  134.38  5103.2  133.71
  5114.1  134.32  5165.2  134.22  5196.2  133.33  5206.6  134.05  5279.1  134.59
  5331.3  135.75  5583.8  137.89  5696.7  139.70  5820.4  140.52  5856.4  140.19
#Mann=3,-1,0
  4307.6    0.05       0  5017.6    0.03       0  5023.6    0.05       0
Bank Sta=5017.6,5023.6
Exp/Cntr=0.3,0.1

Type RM Length L Ch R = 1,12658,125,125,125
BEGIN DESCRIPTION:
Mapping XS 4b7932db
END DESCRIPTION:
XS GIS Cut Line= 6
      2266977.07     13310233.22      2266620.45     13309857.63
      2266499.04     13309774.16      2266392.81     13309800.72
      2266347.28     13309853.84      2265691.78     13310066.02
#Sta/Elev= 30
  4368.8  138.21  4401.2  136.95  4438.0  137.21  4505.8  136.76  4576.3  136.45
  4747.9  134.33  4853.8  134.07  4882.2  134.44  4885.1  135.44  4902.6  136.01
  4911.4  137.40  4917.5  136.92  4938.0  137.77  4975.0  138.64  5037.3  139.24
  5117.9  138.01  5143.6  136.67  5172.9  137.53  5179.5  136.47  5201.4  136.79
  5208.0  135.81  5215.9  136.10  5223.6  134.41  5241.7  133.17  5244.4  132.67
  5247.7  133.17  5349.7  135.39  5500.7  136.19  5660.7  138.87  5902.5  140.43
#Mann=8,-1,0
  4368.8     0.1       0  4438.0    0.05       0  4505.8     0.1       0
  4576.3    0.05       0  4938.0     0.1       0  4975.0    0.05       0
  5241.7   0.035       0  5247.7    0.05       0
Bank Sta=5241.7,5247.7
Exp/Cntr=0.3,0.1

Type RM Length L Ch R = 1,12533,343,343,343
BEGIN DESCRIPTION:
Mapping XS db27a635
END DESCRIPTION:
XS GIS Cut Line= 4
      2267071.92     13310070.08      2266609.07     13309686.90
      2266373.84     13309645.17      2265675.78     13309865.21
#Sta/Elev= 30
  4360.1  140.03  4514.5  138.46  4572.1  137.18  4622.8  136.74  4664.1  136.14
  4691.6  136.51  4791.9  134.68  4819.9  134.81  4841.4  134.02  4862.2  134.59
  4899.7  134.23  4909.7  134.19  4982.7  133.34  5042.8  134.47  5047.9  134.07
  5135.0  133.92  5161.0  133.44  5166.1  132.60  5185.8  133.47  5199.9  133.49
  5216.8  133.05  5224.3  132.24  5227.1  131.74  5230.3  132.24  5254.4  133.15
  5292.0  133.26  5342.6  134.90  5491.4  136.20  5717.9  139.42  5931.8  140.55
#Mann=7,-1,0
  4360.1    0.05       0  4572.1     0.1       0  4622.8    0.05       0
  4899.7     0.1       0  4909.7    0.05       0  5224.3   0.035       0
  5230.3    0.05       0
Bank Sta=5224.3,5230.3
Exp/Cntr=0.3,0.1

Type RM Length L Ch R = 1,12190,670,670,670
BEGIN DESCRIPTION:
UNT051 IN SPCR 17.0
END DESCRIPTION:
XS GIS Cut Line= 3
      2267254.47     13309367.45      2266668.52     13309328.39
      2265822.47     13309510.62
#Sta/Elev= 30
  4231.4  141.14  4338.4  140.12  4558.9  136.10  4609.0  136.24  4636.5  135.65
  4719.2  135.14  4829.7  132.05  4857.0  131.95  4928.4  131.51  4942.2  132.42
  4977.8  132.22  4993.4  131.07  5000.6  129.20  5003.3  128.70  5006.6  129.20
  5013.8  129.99  5022.0  131.83  5027.1  130.54  5029.5  130.94  5034.3  131.73
  5044.5  132.02  5054.7  131.21  5115.5  132.91  5198.0  133.56  5219.3  134.49
  5263.5  134.22  5357.0  136.21  5455.7  136.80  5544.1  138.38  5684.1  139.08
#Mann=7,-1,0
  4231.4    0.05       0  4636.5     0.1       0  4857.0    0.05       0
  4928.4     0.1       0  5000.6    0.07       0  5006.6     0.1       0
  5029.5    0.05       0
Bank Sta=5000.6,5006.6
Exp/Cntr=0.3,0.1

Type RM Length L Ch R = 1,11520,874,874,874
BEGIN DESCRIPTION:
UNT051 IN SPCR 16.0
END DESCRIPTION:
XS GIS Cut Line= 3
      2267189.40     13308820.58      2265952.38     13308820.58
      2265744.61     13309002.37
#Sta/Elev= 30
  4221.7  139.00  4343.4  137.11  4567.1  135.37  4593.4  135.10  4623.4  135.65
  4633.4  134.59  4763.4  133.97  4903.4  131.58  4983.4  129.17  4993.4  128.49
  5000.4  127.05  5003.1  126.55  5006.4  127.05  5013.4  128.60  5023.4  129.64
  5033.4  129.94  5063.4  129.74  5083.4  129.02  5133.4  129.59  5203.4  131.69
  5213.4  132.43  5376.7  136.32  5453.4  137.12  5480.3  138.18  5558.2  138.01
  5615.1  138.96  5637.0  138.68  5657.8  139.31  5672.1  139.07  5734.8  139.81
#Mann=5,-1,0
  4221.7    0.05       0  4567.1     0.1       0  5000.4    0.07       0
  5006.4     0.1       0  5376.7    0.05       0
Bank Sta=5000.4,5006.4
Exp/Cntr=0.3,0.1

Type RM Length L Ch R = 1,10646,800,800,800
BEGIN DESCRIPTION:
UNT051 IN SPCR 15.0
END DESCRIPTION:
XS GIS Cut Line= 3
      2267150.30     13308247.66      2265978.42     13308065.37
      2265680.88     13308052.43
#Sta/Elev= 30
  4126.1  136.62  4317.9  135.44  4391.8  134.73  4412.1  135.47  4425.7  134.67
  4551.5  133.31  4619.4  133.26  4624.6  132.54  4665.1  132.40  4725.8  131.05
  4735.9  130.25  4938.3  127.38  4958.6  126.53  4978.8  127.40  4996.1  123.69
  4998.8  123.19  5002.1  123.69  5006.9  125.88  5011.9  127.12  5090.1  131.13
  5120.5  131.91  5161.0  134.63  5311.7  138.27  5395.4  138.60  5452.9  137.78
  5482.9  138.90  5504.7  137.90  5523.0  139.17  5553.0  138.22  5609.9  138.42
#Mann=6,-1,0
  4126.1    0.05       0  4317.9     0.1       0  4996.1    0.07       0
  5002.1     0.1       0  5311.7    0.08       0  5504.7    0.05       0
Bank Sta=4996.1,5002.1
Exp/Cntr=0.3,0.1

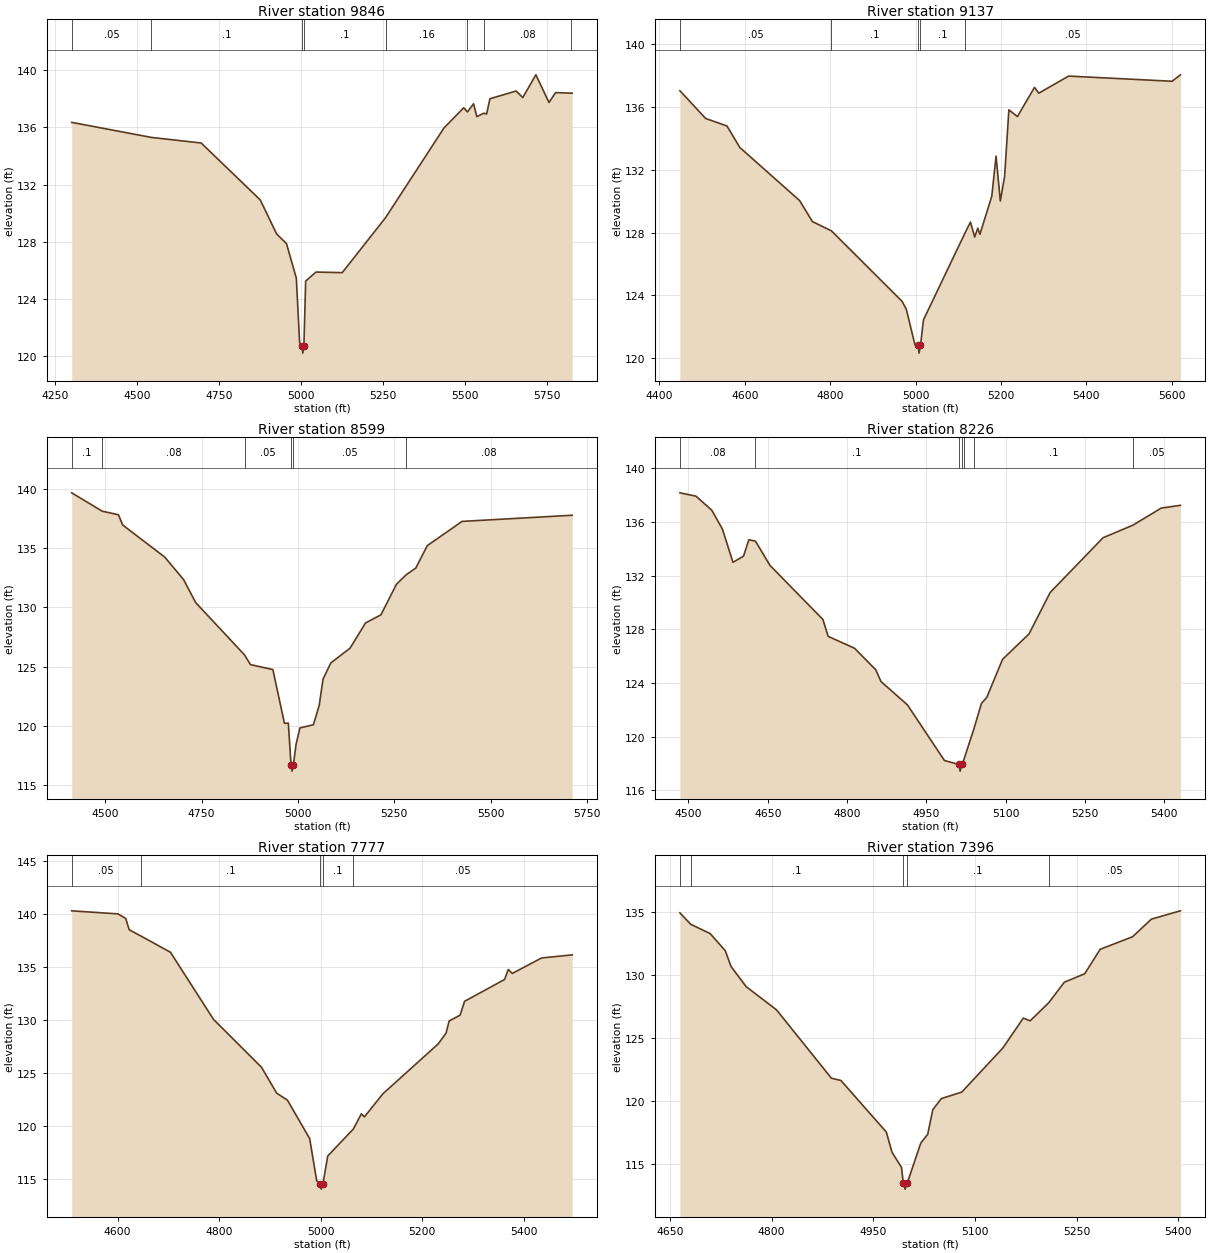
Type RM Length L Ch R = 1,9846,709,709,709
BEGIN DESCRIPTION:
UNT051 IN SPCR 14.0
END DESCRIPTION:
XS GIS Cut Line= 3
      2267228.41     13307635.67      2266902.90     13307440.37
      2265757.07     13307479.43
#Sta/Elev= 30
  4300.1  136.34  4543.2  135.29  4694.9  134.90  4875.0  130.93  4925.0  128.55
  4955.0  127.88  4985.1  125.46  4995.1  120.96  5002.1  120.73  5004.8  120.23
  5008.1  120.73  5013.5  125.26  5045.1  125.89  5125.1  125.85  5257.2  129.69
  5435.3  135.95  5495.4  137.36  5506.8  137.07  5525.4  137.64  5535.4  136.74
  5556.7  136.98  5565.4  136.93  5575.4  137.99  5655.4  138.53  5675.5  138.07
  5715.5  139.66  5755.5  137.73  5775.5  138.42  5822.6  138.38  5826.2  138.38
#Mann=8,-1,0
  4300.1    0.05       0  4543.2     0.1       0  5002.1    0.07       0
  5008.1     0.1       0  5257.2    0.16       0  5506.8     0.1       0
  5556.7    0.08       0  5822.6    0.05       0
Bank Sta=5002.1,5008.1
Exp/Cntr=0.3,0.1

Type RM Length L Ch R = 1,9137,538,538,538
BEGIN DESCRIPTION:
UNT051 IN SPCR 13.0
END DESCRIPTION:
XS GIS Cut Line= 2
      2266968.04     13306776.31      2265796.13     13306802.35
#Sta/Elev= 30
  4448.1  137.04  4508.4  135.27  4558.4  134.79  4588.5  133.42  4728.5  130.04
  4758.5  128.70  4803.1  128.11  4968.5  123.62  4978.6  123.10  4998.6  120.85
  5005.6  120.82  5008.3  120.32  5011.6  120.82  5018.6  122.44  5116.7  128.02
  5128.6  128.67  5138.6  127.72  5145.8  128.28  5150.8  127.89  5178.6  130.32
  5188.6  132.87  5198.6  130.01  5208.6  131.57  5218.6  135.82  5238.6  135.39
  5278.6  137.25  5288.6  136.88  5358.6  137.97  5600.9  137.64  5620.3  138.05
#Mann=5,-1,0
  4448.1    0.05       0  4803.1     0.1       0  5005.6    0.07       0
  5011.6     0.1       0  5116.7    0.05       0
Bank Sta=5005.6,5011.6
Exp/Cntr=0.3,0.1

Type RM Length L Ch R = 1,8599,373,373,373
BEGIN DESCRIPTION:
UNT051 IN SPCR 12.0
END DESCRIPTION:
XS GIS Cut Line= 2
      2266928.86     13306244.15      2265632.41     13306322.25
#Sta/Elev= 30
  4413.0  139.65  4492.4  138.10  4534.4  137.80  4545.3  136.94  4654.6  134.23
  4703.5  132.33  4734.7  130.40  4861.5  125.99  4876.9  125.17  4935.1  124.75
  4965.1  120.22  4975.2  120.24  4982.2  116.69  4984.9  116.19  4988.2  116.69
  4995.2  118.44  5005.2  119.83  5040.2  120.10  5055.3  121.73  5065.3  123.95
  5085.4  125.31  5135.5  126.56  5175.5  128.68  5215.6  129.37  5255.7  131.94
  5280.9  132.74  5305.8  133.30  5335.8  135.20  5426.0  137.24  5711.8  137.76
#Mann=6,-1,0
  4413.0     0.1       0  4492.4    0.08       0  4861.5    0.05       0
  4982.2    0.04       0  4988.2    0.05       0  5280.9    0.08       0
Bank Sta=4982.2,4988.2
Exp/Cntr=0.3,0.1

Type RM Length L Ch R = 1,8226,449,449,449
BEGIN DESCRIPTION:
UNT051 IN SPCR 11.0
END DESCRIPTION:
XS GIS Cut Line= 2
      2266658.09     13305973.31      2265711.40     13305968.11
#Sta/Elev= 30
  4483.8  138.17  4514.2  137.92  4544.2  136.87  4564.2  135.47  4584.2  132.99
  4604.2  133.45  4614.2  134.67  4626.7  134.57  4654.2  132.76  4754.3  128.73
  4764.2  127.47  4814.2  126.58  4854.2  124.98  4864.2  124.10  4914.2  122.36
  4984.2  118.21  5011.2  117.92  5013.9  117.42  5017.2  117.92  5020.7  118.24
  5040.2  120.61  5054.2  122.47  5064.2  122.91  5094.2  125.76  5144.2  127.65
  5184.2  130.74  5284.2  134.82  5340.8  135.76  5394.2  137.03  5430.5  137.24
#Mann=7,-1,0
  4483.8    0.08       0  4626.7     0.1       0  5011.2    0.07       0
  5017.2     0.1       0  5020.7    0.05       0  5040.2     0.1       0
  5340.8    0.05       0
Bank Sta=5011.2,5017.2
Exp/Cntr=0.3,0.1

Type RM Length L Ch R = 1,7777,381,381,381
BEGIN DESCRIPTION:
UNT051 IN SPCR 10.0
END DESCRIPTION:
XS GIS Cut Line= 2
      2266453.32     13305305.27      2265621.37     13305833.90
#Sta/Elev= 30
  4509.7  140.31  4600.9  140.02  4616.1  139.59  4623.0  138.52  4645.7  137.94
  4704.2  136.40  4788.9  130.07  4883.6  125.54  4913.4  123.10  4934.6  122.44
  4978.4  118.81  4992.2  114.84  4998.5  114.54  5001.2  114.04  5004.5  114.54
  5014.0  117.17  5064.5  119.72  5080.2  121.15  5086.2  120.86  5122.6  123.04
  5231.8  127.76  5247.1  128.78  5253.0  129.91  5274.6  130.46  5283.5  131.77
  5362.3  133.83  5369.4  134.77  5377.5  134.40  5435.1  135.86  5495.4  136.15
#Mann=5,-1,0
  4509.7    0.05       0  4645.7     0.1       0  4998.5    0.07       0
  5004.5     0.1       0  5064.5    0.05       0
Bank Sta=4998.5,5004.5
Exp/Cntr=0.3,0.1

Type RM Length L Ch R = 1,7396,440,440,440
BEGIN DESCRIPTION:
UNT051 IN SPCR 9.0
END DESCRIPTION:
XS GIS Cut Line= 3
      2266137.70     13305096.86      2265837.72     13305246.85
      2265437.72     13305296.85
#Sta/Elev= 30
  4664.7  134.97  4680.7  134.06  4709.4  133.32  4731.8  131.95  4740.1  130.71
  4762.5  129.10  4807.2  127.26  4888.3  121.82  4902.3  121.64  4969.3  117.54
  4977.7  115.93  4991.7  114.73  4994.3  113.50  4997.0  113.00  5000.3  113.50
  5020.2  116.67  5030.3  117.35  5037.9  119.32  5050.5  120.20  5080.7  120.72
  5141.2  124.22  5171.4  126.60  5181.5  126.38  5209.1  127.83  5231.9  129.45
  5262.1  130.13  5284.8  132.07  5332.7  133.07  5360.4  134.47  5403.2  135.13
#Mann=5,-1,0
  4664.7    0.05       0  4680.7     0.1       0  4994.3    0.07       0
  5000.3     0.1       0  5209.1    0.05       0
Bank Sta=4994.3,5000.3
Exp/Cntr=0.3,0.1