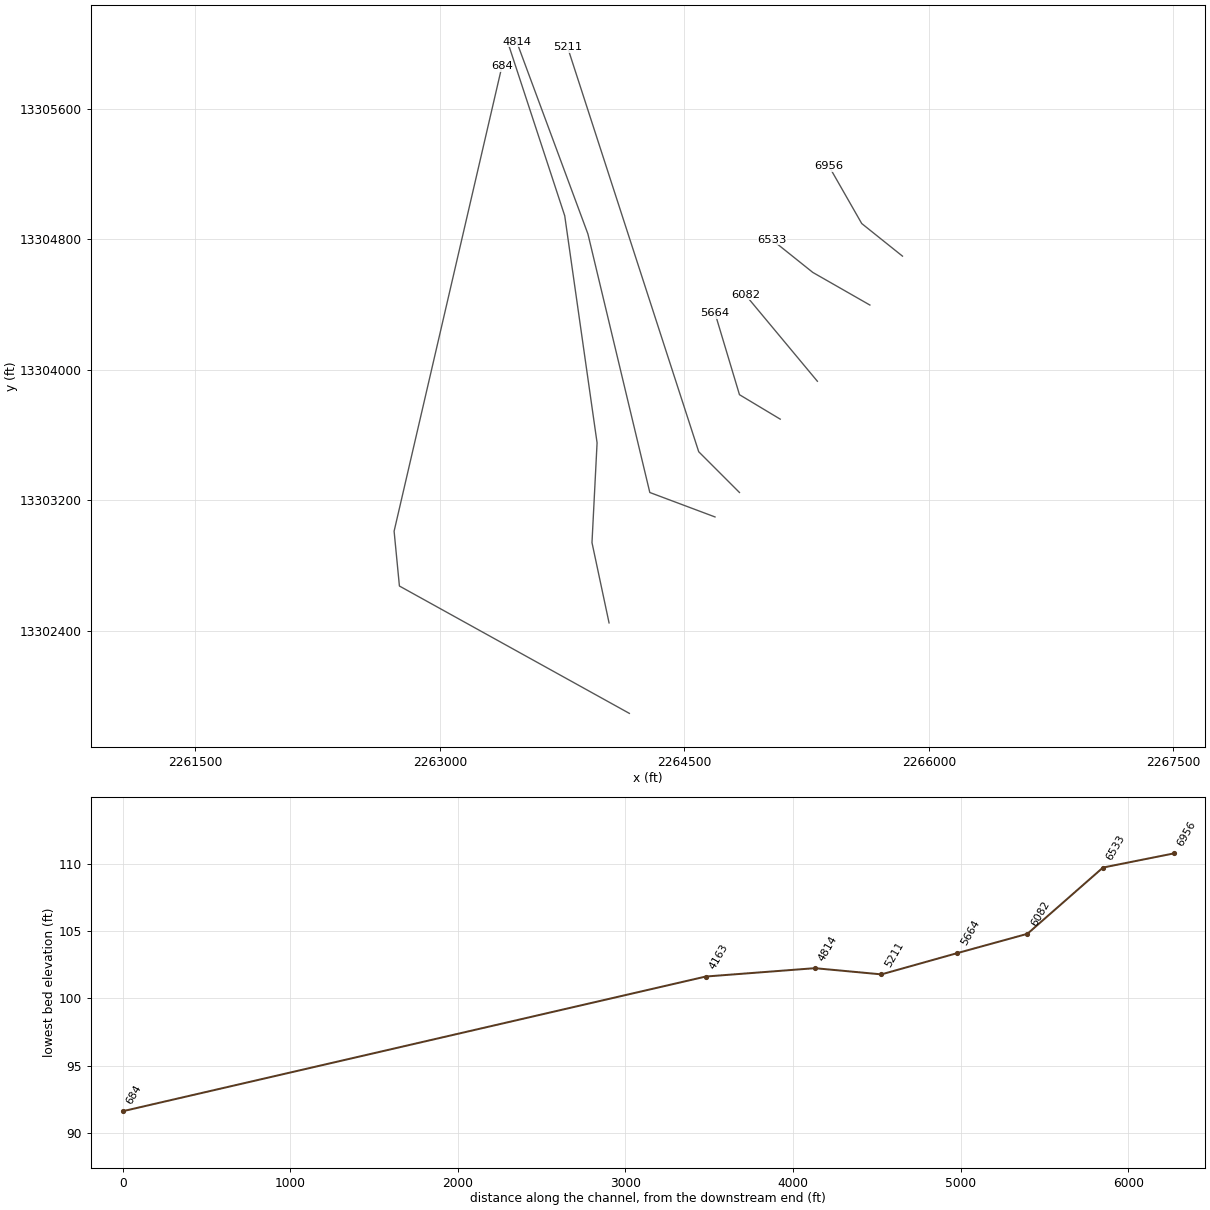
HEC-RAS study UNT051 IN SPCR.prj: UNT051 IN SPCR Base Level Engineering

--- UNT051 IN SPCR.g01 (geometry) --- (continued)

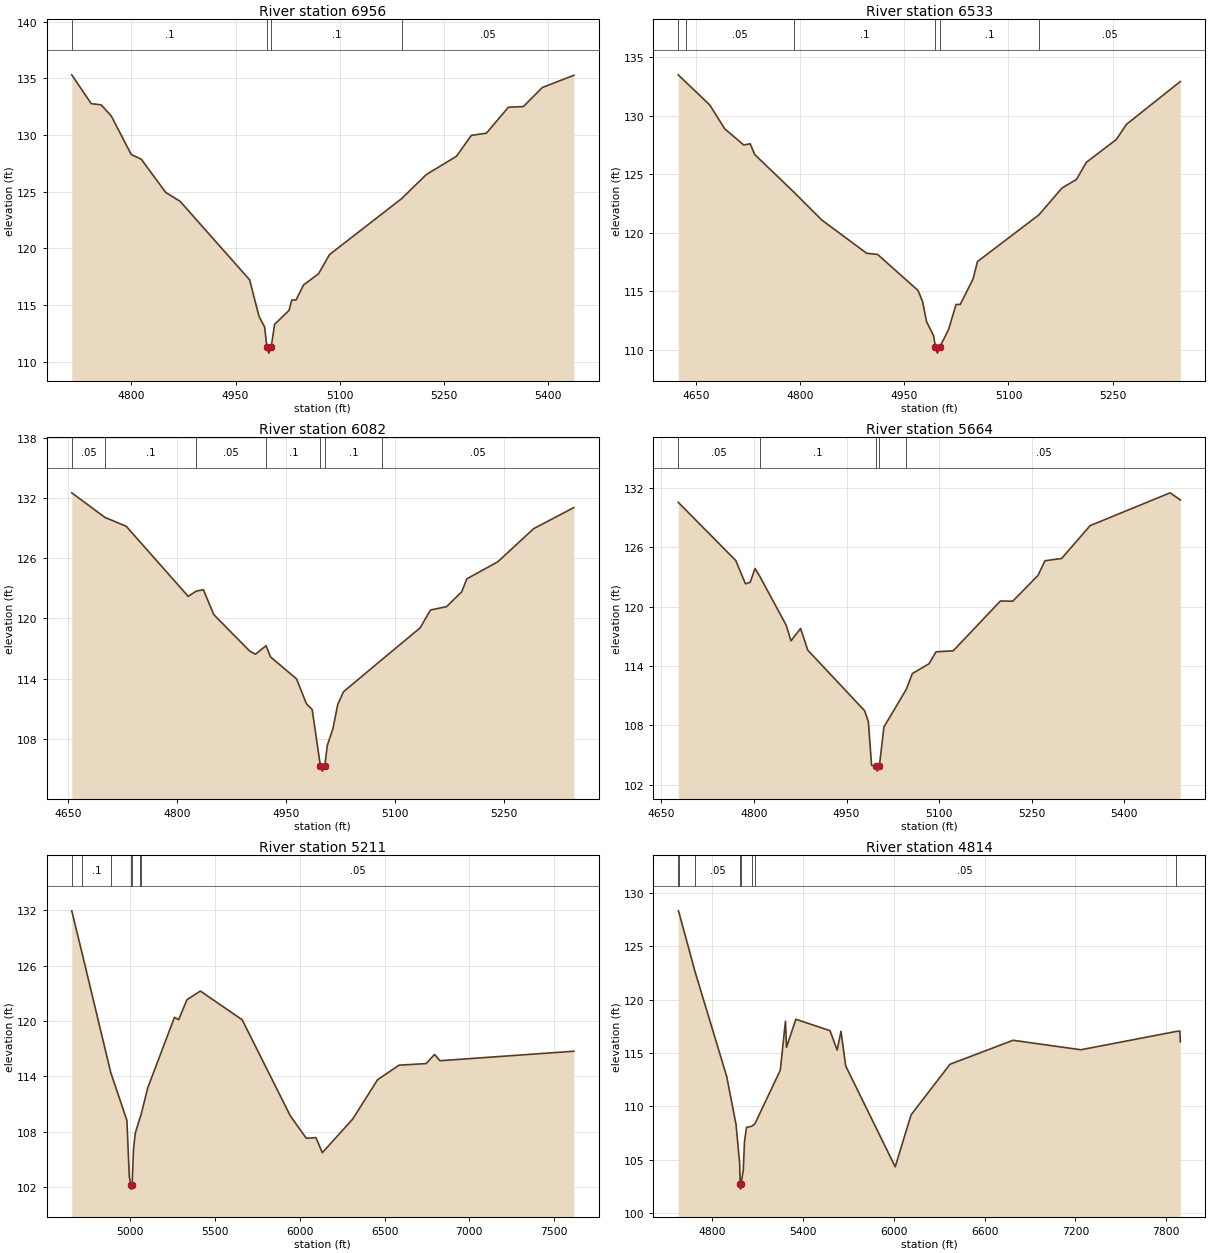
Type RM Length L Ch R = 1,6956,423,423,423
BEGIN DESCRIPTION:
UNT051 IN SPCR 8.0
END DESCRIPTION:
XS GIS Cut Line= 3
      2265837.74     13304696.84      2265587.72     13304896.85
      2265387.72     13305246.86
#Sta/Elev= 30
  4714.1  135.31  4742.1  132.77  4756.5  132.66  4771.0  131.68  4799.8  128.28
  4814.2  127.87  4849.4  124.94  4870.2  124.15  4970.3  117.23  4983.9  113.99
  4991.9  113.07  4995.3  111.26  4998.0  110.76  5001.3  111.26  5006.3  113.30
  5027.1  114.53  5031.1  115.45  5037.2  115.45  5048.0  116.77  5069.6  117.76
  5085.4  119.45  5189.3  124.39  5225.0  126.52  5268.2  128.12  5289.8  129.97
  5311.4  130.16  5343.1  132.45  5364.7  132.51  5392.0  134.19  5437.4  135.27
#Mann=4,-1,0
  4714.1     0.1       0  4995.3    0.07       0  5001.3     0.1       0
  5189.3    0.05       0
Bank Sta=4995.3,5001.3
Exp/Cntr=0.3,0.1

Type RM Length L Ch R = 1,6533,451,451,451
BEGIN DESCRIPTION:
UNT051 IN SPCR 7.0
END DESCRIPTION:
XS GIS Cut Line= 3
      2265637.74     13304396.84      2265287.72     13304596.85
      2265037.71     13304796.86
#Sta/Elev= 30
  4624.3  133.48  4635.9  132.82  4669.7  130.91  4691.3  128.87  4718.6  127.49
  4728.0  127.59  4734.5  126.67  4791.5  123.43  4830.9  121.09  4895.7  118.24
  4911.5  118.14  4969.8  115.06  4976.3  114.11  4982.1  112.39  4992.2  111.19
  4994.9  110.21  4997.7  109.71  5000.9  110.21  5013.8  111.74  5024.6  113.87
  5030.6  113.87  5049.0  116.04  5055.4  117.53  5143.9  121.52  5177.1  123.81
  5197.9  124.54  5212.3  126.01  5255.5  127.96  5270.0  129.25  5347.6  132.91
#Mann=6,-1,0
  4624.3     0.1       0  4635.9    0.05       0  4791.5     0.1       0
  4994.9    0.07       0  5000.9     0.1       0  5143.9    0.05       0
Bank Sta=4994.9,5000.9
Exp/Cntr=0.3,0.1

Type RM Length L Ch R = 1,6082,418,418,418
BEGIN DESCRIPTION:
UNT051 IN SPCR 6.0
END DESCRIPTION:
XS GIS Cut Line= 2
      2265315.62     13303929.29      2264873.77     13304460.03
#Sta/Elev= 30
  4655.2  132.50  4700.9  130.05  4730.1  129.17  4815.4  122.19  4826.3  122.71
  4836.2  122.86  4850.5  120.38  4900.0  116.74  4907.8  116.43  4922.5  117.28
  4928.6  116.16  4964.3  113.98  4978.1  111.48  4985.9  110.92  4997.2  105.29
  5000.0  104.79  5003.2  105.29  5006.7  107.36  5014.5  109.03  5021.0  111.41
  5028.9  112.69  5081.6  115.88  5134.3  119.05  5148.6  120.83  5170.8  121.17
  5191.6  122.65  5198.5  123.93  5241.1  125.63  5290.5  128.93  5345.8  131.03
#Mann=7,-1,0
  4655.2    0.05       0  4700.9     0.1       0  4826.3    0.05       0
  4922.5     0.1       0  4997.2    0.07       0  5003.2     0.1       0
  5081.6    0.05       0
Bank Sta=4997.2,5003.2
Exp/Cntr=0.3,0.1

Type RM Length L Ch R = 1,5664,453,453,453
BEGIN DESCRIPTION:
UNT051 IN SPCR 5.0
END DESCRIPTION:
XS GIS Cut Line= 3
      2265087.74     13303696.84      2264837.72     13303846.85
      2264687.72     13304346.87
#Sta/Elev= 30
  4677.2  130.55  4770.5  124.66  4786.1  122.31  4793.8  122.46  4801.6  123.86
  4809.5  123.05  4852.2  118.11  4859.9  116.54  4875.5  117.79  4887.1  115.60
  4979.2  109.47  4985.3  108.37  4990.5  103.95  4997.1  103.86  4999.8  103.36
  5003.1  103.86  5010.5  107.82  5047.0  111.66  5056.6  113.23  5083.6  114.22
  5094.9  115.43  5122.8  115.53  5199.3  120.57  5219.3  120.55  5260.2  123.16
  5271.5  124.64  5298.5  124.87  5344.6  128.19  5474.3  131.51  5490.8  130.79
#Mann=5,-1,0
  4677.2    0.05       0  4809.5     0.1       0  4997.1    0.07       0
  5003.1     0.1       0  5047.0    0.05       0
Bank Sta=4997.1,5003.1
Exp/Cntr=0.3,0.1

Type RM Length L Ch R = 1,5211,397,397,397
BEGIN DESCRIPTION:
UNT051 IN SPCR 4.0
END DESCRIPTION:
XS GIS Cut Line= 3
      2264837.74     13303246.84      2264587.72     13303496.85
      2263783.08     13305978.49
#Sta/Elev= 30
  4653.9  131.93  4717.2  127.16  4883.9  114.41  4979.2  109.23  4993.3  103.19
  5000.9  102.28  5003.7  101.78  5006.9  102.28  5010.1  102.28  5018.0  106.08
  5028.7  107.84  5055.4  109.45  5061.3  109.74  5102.1  112.75  5259.8  120.39
  5284.6  120.13  5333.4  122.30  5412.5  123.24  5659.3  120.13  5943.1  109.73
  6037.7  107.29  6094.6  107.36  6132.3  105.73  6311.0  109.36  6458.2  113.63
  6584.8  115.21  6744.7  115.38  6794.6  116.37  6826.1  115.69  7616.3  116.72
#Mann=7,-1,0
  4653.9    0.05       0  4717.2     0.1       0  4883.9    0.05       0
  5000.9   0.035       0  5006.9    0.05       0  5055.4     0.1       0
  5061.3    0.05       0
Bank Sta=5000.9,5006.9
Exp/Cntr=0.3,0.1

Type RM Length L Ch R = 1,4814,651,651,651
BEGIN DESCRIPTION:
UNT051 IN SPCR 3.0
END DESCRIPTION:
XS GIS Cut Line= 4
      2264687.72     13303096.85      2264287.72     13303246.85
      2263908.07     13304832.69      2263470.84     13306012.53
#Sta/Elev= 30
  4576.4  128.34  4580.0  128.25  4686.1  122.70  4896.8  112.79  4958.2  108.30
  4982.2  104.63  4985.5  102.74  4988.2  102.24  4991.5  102.74  5006.2  104.06
  5013.9  106.68  5027.2  108.03  5061.6  108.13  5082.5  108.36  5250.4  113.39
  5284.6  117.99  5291.5  115.54  5353.2  118.17  5578.9  117.10  5626.0  115.28
  5651.4  117.04  5682.3  113.80  6009.6  104.33  6114.1  109.20  6371.2  113.95
  6788.0  116.20  7235.9  115.31  7862.1  117.02  7889.4  117.07  7892.5  116.06
#Mann=8,-1,0
  4576.4    0.05       0  4580.0     0.1       0  4686.1    0.05       0
  4985.5   0.035       0  4991.5    0.05       0  5061.6     0.1       0
  5082.5    0.05       0  7862.1     0.1       0
Bank Sta=4985.5,4991.5
Exp/Cntr=0.3,0.1

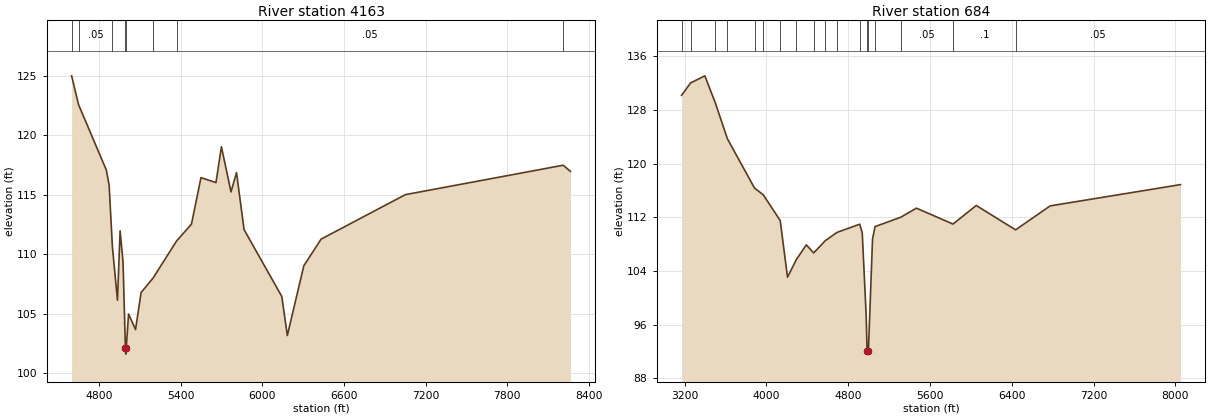
Type RM Length L Ch R = 1,4163,3479,3479,3479
BEGIN DESCRIPTION:
UNT051 IN SPCR 2.0
END DESCRIPTION:
XS GIS Cut Line= 5
      2264037.71     13302446.90      2263932.94     13302939.44
      2263964.19     13303551.42      2263765.79     13304944.20
      2263408.43     13306032.98
#Sta/Elev= 30
  4596.9  125.00  4648.0  122.58  4852.4  117.08  4872.9  115.81  4896.9  110.64
  4934.2  106.15  4953.5  111.98  4975.1  109.36  4992.6  102.12  4995.3  101.62
  4998.6  102.12  5016.0  104.99  5067.1  103.68  5107.9  106.79  5196.6  108.02
  5368.6  111.12  5478.4  112.54  5548.5  116.45  5658.6  116.03  5698.7  119.04
  5769.2  115.25  5809.6  116.87  5865.3  112.08  6143.0  106.46  6183.4  103.18
  6304.6  109.04  6431.8  111.28  7052.1  115.02  8212.7  117.49  8266.0  116.97
#Mann=8,-1,0
  4596.9     0.1       0  4648.0    0.05       0  4896.9     0.1       0
  4992.6    0.07       0  4998.6     0.1       0  5196.6    0.16       0
  5368.6    0.05       0  8212.7     0.1       0
Bank Sta=4992.6,4998.6
Exp/Cntr=0.3,0.1

Type RM Length L Ch R = 1,684,0,0,0
BEGIN DESCRIPTION:
UNT051 IN SPCR 1.0
END DESCRIPTION:
XS GIS Cut Line= 4
      2264162.19     13301891.80      2262751.57     13302673.06
      2262719.02     13303009.43      2263380.77     13305862.54
#Sta/Elev= 30
  3169.7  130.19  3257.7  132.03  3397.3  133.09  3499.7  129.05  3618.1  123.70
  3883.7  116.35  3968.1  115.37  4134.4  111.52  4205.6  103.08  4292.1  105.71
  4389.9  107.90  4461.5  106.70  4575.6  108.53  4689.8  109.76  4911.9  110.98
  4936.7  109.67  4974.9   97.43  4984.0   92.12  4986.7   91.62  4990.0   92.12
  4997.0   92.15  5037.2  108.76  5061.4  110.62  5313.5  112.02  5466.5  113.37
  5823.9  111.00  6051.7  113.77  6436.3  110.14  6774.8  113.71  8049.0  116.88
#Mann=18,-1,0
  3169.7     0.1       0  3257.7    0.16       0  3499.7     0.1       0
  3618.1    0.05       0  3883.7     0.1       0  3968.1    0.05       0
  4134.4     0.1       0  4292.1    0.16       0  4461.5     0.1       0
  4575.6    0.16       0  4689.8    0.12       0  4911.9     0.1       0
  4984.0    0.07       0  4990.0     0.1       0  5061.4    0.12       0
  5313.5    0.05       0  5823.9     0.1       0  6436.3    0.05       0
Bank Sta=4984,4990
Exp/Cntr=0.3,0.1

Chan Stop Cuts=-1

--- UNT051 IN SPCR.g02 (geometry) ---

Geom Title=Dummy
Program Version=4.10

River Reach=UNT051 IN SPCR  ,Reach-1
Reach XY= 30
       2279414.3     13329661.25      2279736.83      13328836.5
      2279724.32     13326598.69       2280836.2      13324845.5
      2280818.03     13324301.52       2280113.6     13323473.61
      2279797.18      13322185.8      2278146.06     13320930.72
       2276812.8     13320597.21      2276003.31     13320892.44
      2275386.94     13320091.33      2273225.44     13319503.07
      2272935.19     13318197.86      2272380.24     13317595.81
      2272194.73      13316922.4      2271435.06     13316631.97
      2270844.92     13316028.62      2271015.65     13315105.19
      2270611.83      13314655.4        2270440.     13313549.98
      2266961.52     13312115.28      2266234.81     13308336.78
      2266591.58     13307664.91      2266449.22     13306480.88
      2265762.69     13305054.23      2264004.78     13302854.21
       2263322.7     13303946.88      2263344.04     13303164.49
      2262817.89     13302897.86      2262154.24     13303023.63

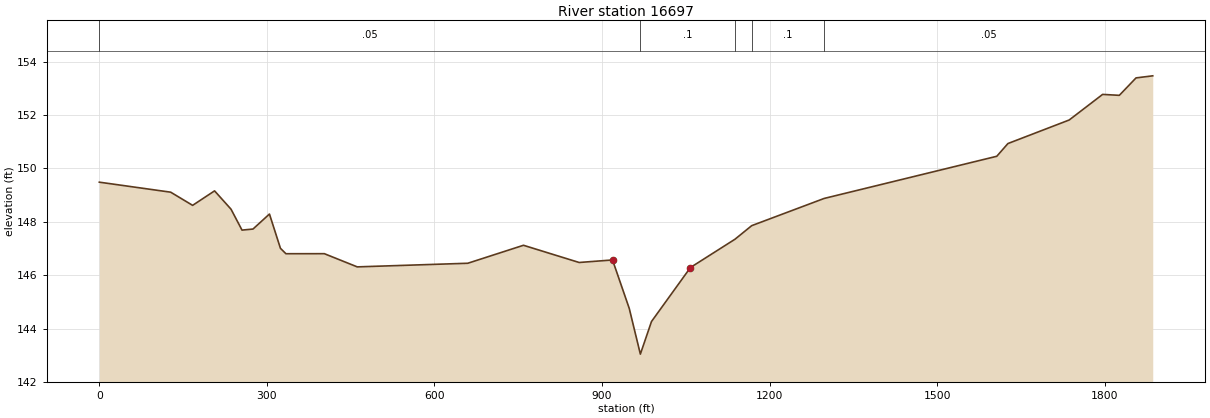
Type RM Length L Ch R = 1 ,16697   ,,,
XS GIS Cut Line= 4
     2269041.818    13312259.363     2268483.846    13312199.228
     2268288.712    13312672.531     2268255.497    13313490.433
#Sta/Elev= 30
       0149.4836127.7309149.1084167.0327148.6149206.3346149.1575235.8109148.4701
255.4619147.6871275.1128 147.727304.5891148.2894  324.24147.0061334.0655146.8023
402.8437146.8038461.7964146.3093659.7159146.4452759.3809147.1187859.0458146.4742
918.8448146.5683948.7443144.7553968.6772143.0401988.6102144.26171058.376 146.286
1138.142147.34621168.059147.85431297.698148.87351606.838 150.4541626.783150.9308
1736.478151.81331796.311152.77231826.228152.73741856.145153.39051886.062153.4685
#Mann= 5 ,-1 , 0
       0     .05       0968.6772      .1       01138.142     .07       0
1168.059      .1       01297.698     .05       0
Bank Sta=918.8448,1058.376
XS Rating Curve= 0 ,0
Exp/Cntr=0.3,0.1

Chan Stop Cuts=-1
Use User Specified Reach Order=0
Composite Channel Slope=5