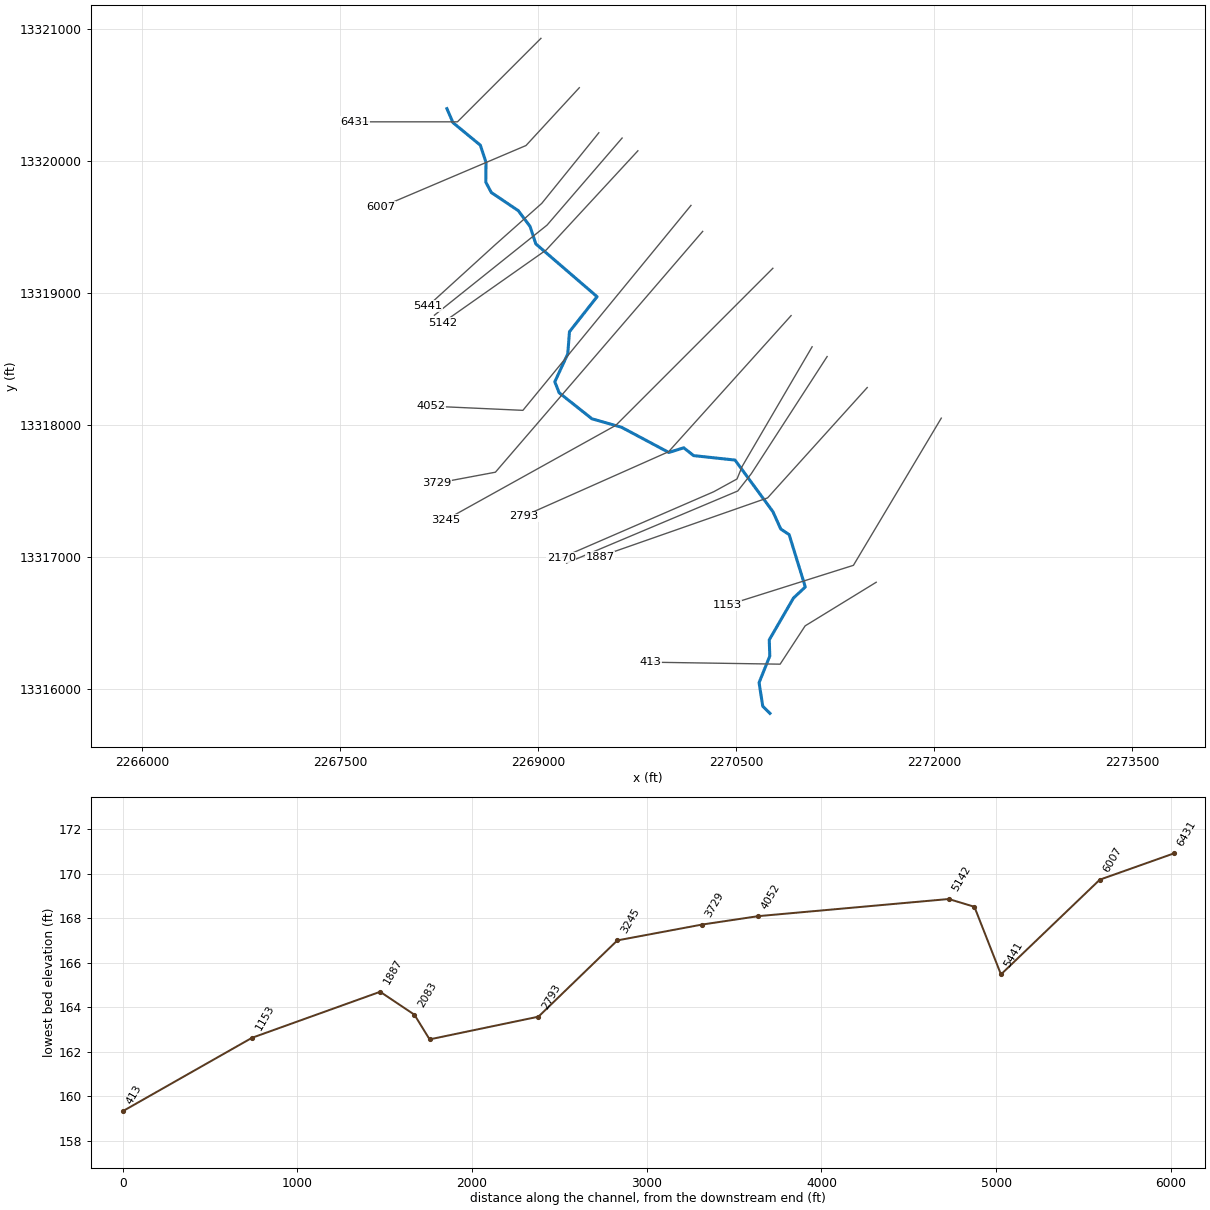
--- UNT052 IN SPCR.prj (project) ---

Proj Title=UNT052 IN SPCR Base Level Engineering
Current Plan=p01
Default Exp/Contr=0.3,0.1
English Units
Geom File=g01
Flow File=f01
Plan File=p01
BEGIN DESCRIPTION:
UNT052 IN SPCR
END DESCRIPTION:

--- UNT052 IN SPCR.p01 (plan) ---

Plan Title=Multiple Run
Short Identifier=Multiple
Geom File=g01
Flow File=f01
Subcritical Flow
K Sum by GR= 0
Std Step Tol= 0.01
Critical Tol= 0.01
Num of Std Step Trials= 20
Max Error Tol= 0.3
Flow Tol Ratio= 0.001
Split Flow NTrial= 30
Split Flow Tol= 0.02
Split Flow Ratio= 0.02
Log Output Level= 0
Friction Slope Method= 1
Unsteady Friction Slope Method= 2
Unsteady Bridges Friction Slope Method= 1
Parabolic Critical Depth
Global Vel Dist=  1 , 1 , 1
Global Log Level= 0
CheckData=True
Encroach Param= -1, 0, 0, 0
BEGIN DESCRIPTION:
Multiple Run
END DESCRIPTION:

--- UNT052 IN SPCR.f01 (steady flow) ---

Flow Title=Multiple
Number of Profiles=7
Profile Names=10-year,25-year,50-year,1pct_min,100-year,1pct_plu,500-year
River Rch & RM= UNT052 IN SPCR,Reach-1,6431
     176     239     290     259     350     474     520
River Rch & RM= UNT052 IN SPCR,Reach-1,5289
     218     298     363     325     440     595     656
Boundary for River Rch & Prof#=UNT052 IN SPCR,Reach-1,1
Up Type=0
Dn Type=3
Dn Slope=0.005
Boundary for River Rch & Prof#=UNT052 IN SPCR,Reach-1,2
Up Type=0
Dn Type=3
Dn Slope=0.005
Boundary for River Rch & Prof#=UNT052 IN SPCR,Reach-1,3
Up Type=0
Dn Type=3
Dn Slope=0.005
Boundary for River Rch & Prof#=UNT052 IN SPCR,Reach-1,4
Up Type=0
Dn Type=3
Dn Slope=0.005
Boundary for River Rch & Prof#=UNT052 IN SPCR,Reach-1,5
Up Type=0
Dn Type=3
Dn Slope=0.005
Boundary for River Rch & Prof#=UNT052 IN SPCR,Reach-1,6
Up Type=0
Dn Type=3
Dn Slope=0.005
Boundary for River Rch & Prof#=UNT052 IN SPCR,Reach-1,7
Up Type=0
Dn Type=3
Dn Slope=0.005

--- UNT052 IN SPCR.g01 (geometry) ---

Geom Title=Existing Conditions

River Reach=UNT052 IN SPCR,Reach-1
Reach XY= 30
      2268307.72     13320396.86      2268354.41     13320290.04
      2268561.34     13320119.59      2268603.87     13319991.52
      2268602.95     13319839.06      2268644.62     13319760.93
      2268848.61     13319623.78      2268938.02     13319503.99
      2268981.43     13319372.04      2269445.83     13318971.87
      2269236.63     13318706.25      2269223.61     13318537.84
      2269125.52     13318326.91      2269158.51     13318243.57
      2269406.77     13318046.52      2269630.62     13317982.48
      2269989.83     13317791.19      2270102.45     13317826.71
      2270177.39     13317767.40      2270491.24     13317733.67
      2270778.57     13317342.18      2270837.76     13317211.17
      2270901.26     13317168.77      2271023.79     13316772.11
      2270934.22     13316688.11      2270750.62     13316371.22
      2270754.66     13316248.20      2270673.43     13316047.01
      2270701.34     13315868.29      2270756.03     13315814.10

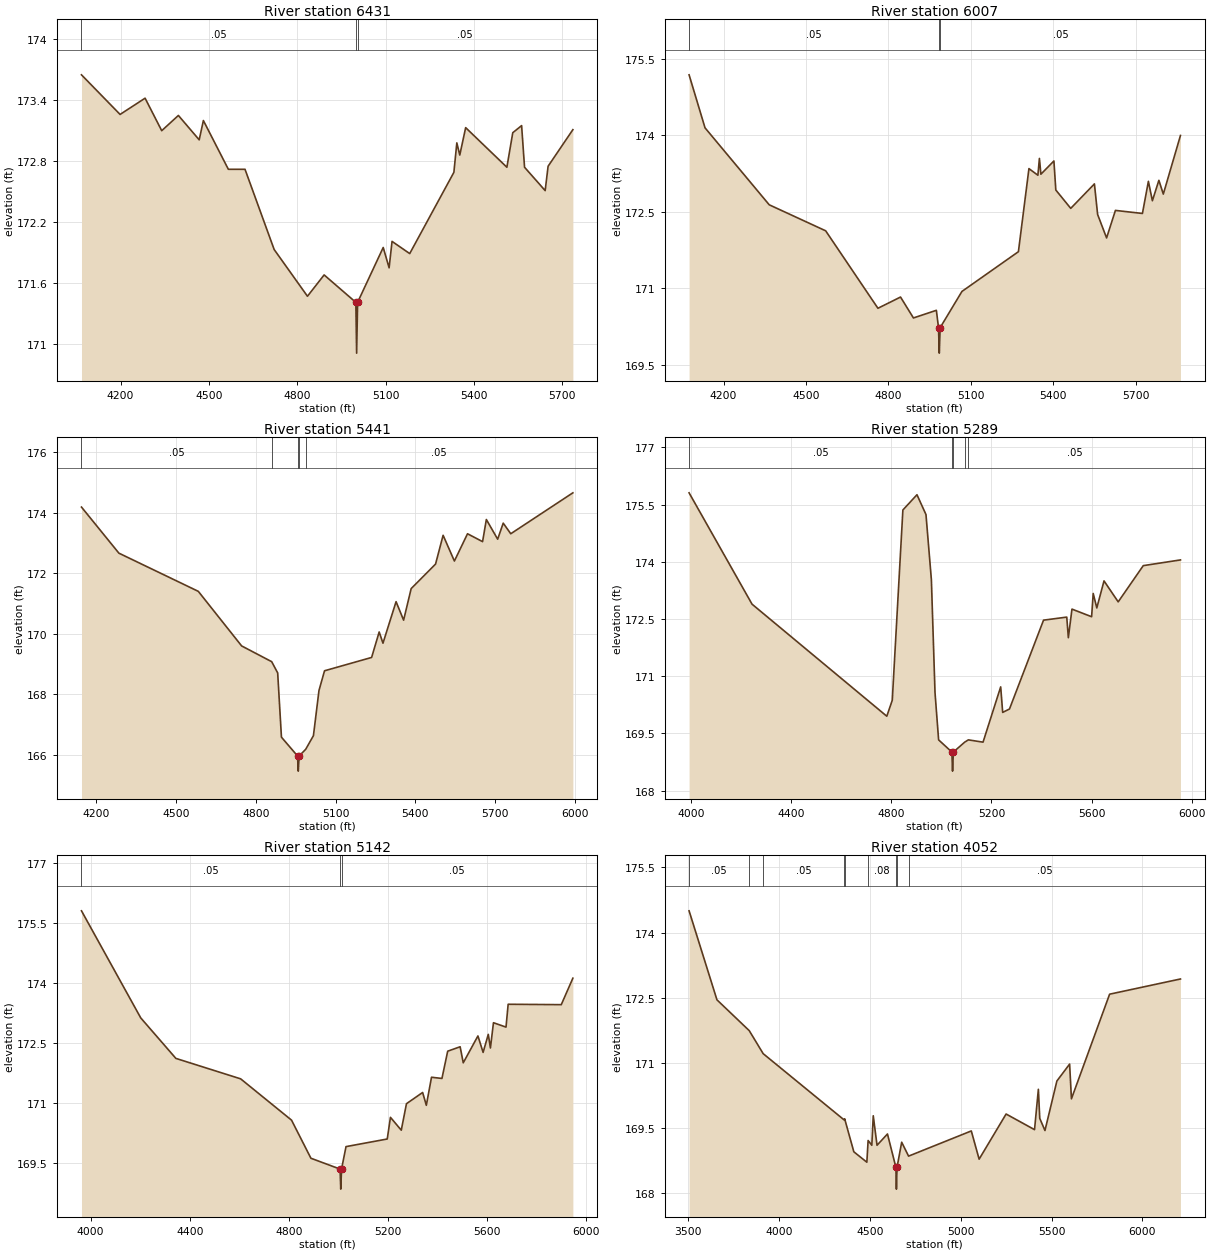
Type RM Length L Ch R = 1,6431,424,424,424
BEGIN DESCRIPTION:
UNT052 IN SPCR 9.0
END DESCRIPTION:
XS GIS Cut Line= 3
      2269020.44     13320929.57      2268387.72     13320296.85
      2267613.62     13320296.85
#Sta/Elev= 30
  4067.4  173.65  4198.5  173.26  4283.4  173.42  4339.9  173.10  4396.5  173.25
  4467.2  173.01  4481.4  173.20  4566.2  172.72  4622.8  172.72  4721.8  171.93
  4834.9  171.47  4891.5  171.68  4999.2  171.41  5001.9  170.91  5005.2  171.41
  5092.2  171.95  5112.2  171.75  5122.2  172.01  5182.2  171.89  5332.2  172.69
  5342.2  172.98  5352.2  172.86  5372.2  173.13  5512.2  172.74  5532.2  173.08
  5562.2  173.15  5572.2  172.74  5642.2  172.51  5652.2  172.75  5736.3  173.11
#Mann=3,-1,0
  4067.4    0.05       0  4999.2    0.03       0  5005.2    0.05       0
Bank Sta=4999.2,5005.2
Exp/Cntr=0.3,0.1

Type RM Length L Ch R = 1,6007,566,566,566
BEGIN DESCRIPTION:
UNT052 IN SPCR 8.0
END DESCRIPTION:
XS GIS Cut Line= 3
      2269311.21     13320555.41      2268907.18     13320117.23
      2267810.30     13319651.20
#Sta/Elev= 30
  4074.5  175.19  4132.5  174.15  4366.1  172.64  4571.4  172.13  4761.6  170.61
  4843.8  170.83  4890.8  170.42  4974.2  170.57  4982.0  170.23  4984.8  169.73
  4988.0  170.23  5067.2  170.94  5272.7  171.72  5311.0  173.35  5343.6  173.22
  5349.1  173.55  5354.5  173.24  5401.8  173.50  5408.8  172.93  5463.1  172.57
  5549.2  173.05  5560.9  172.45  5593.5  171.99  5625.6  172.53  5723.9  172.47
  5745.6  173.10  5760.1  172.72  5783.8  173.12  5799.9  172.85  5862.3  174.00
#Mann=3,-1,0
  4074.5    0.05       0  4982.0    0.03       0  4988.0    0.05       0
Bank Sta=4982,4988
Exp/Cntr=0.3,0.1

Type RM Length L Ch R = 1,5441,152,152,152
BEGIN DESCRIPTION:
UNT052 IN SPCR 7.0
END DESCRIPTION:
XS GIS Cut Line= 4
      2269459.18     13320213.96      2269026.69     13319679.03
      2268668.16     13319360.34      2268163.55     13318901.08
#Sta/Elev= 30
  4143.7  174.18  4284.5  172.66  4583.5  171.40  4746.6  169.60  4859.8  169.08
  4882.3  168.71  4896.5  166.59  4957.1  165.97  4959.8  165.47  4963.1  165.97
  4987.8  166.19  5016.9  166.64  5037.8  168.13  5058.7  168.78  5236.0  169.22
  5264.4  170.06  5278.7  169.69  5328.0  171.06  5356.4  170.45  5384.8  171.49
  5476.7  172.30  5505.1  173.25  5547.6  172.40  5597.0  173.30  5653.7  173.04
  5667.9  173.77  5710.5  173.12  5731.4  173.65  5759.8  173.30  5993.6  174.65
#Mann=5,-1,0
  4143.7    0.05       0  4859.8     0.1       0  4957.1    0.03       0
  4963.1     0.1       0  4987.8    0.05       0
Bank Sta=4957.1,4963.1
Exp/Cntr=0.3,0.1

Type RM Length L Ch R = 1,5289,147,147,147
BEGIN DESCRIPTION:
Mapping XS ce46451e
END DESCRIPTION:
XS GIS Cut Line= 3
      2269635.60     13320174.12      2269066.53     13319514.00
      2268213.39     13318831.49
#Sta/Elev= 30
  3991.4  175.81  4243.0  172.89  4781.7  169.95  4803.6  170.37  4846.0  175.36
  4902.3  175.76  4938.3  175.24  4959.9  173.53  4974.4  170.57  4988.8  169.33
  5041.8  169.01  5044.5  168.51  5047.8  169.01  5093.0  169.27  5107.7  169.33
  5166.4  169.27  5236.9  170.72  5244.9  170.05  5272.1  170.14  5408.2  172.47
  5501.0  172.55  5507.4  172.01  5521.8  172.76  5600.3  172.56  5606.7  173.17
  5621.1  172.79  5649.9  173.50  5706.6  172.95  5806.8  173.90  5955.5  174.05
#Mann=5,-1,0
  3991.4    0.05       0  5041.8    0.03       0  5047.8    0.05       0
  5093.0     0.1       0  5107.7    0.05       0
Bank Sta=5041.8,5047.8
Exp/Cntr=0.3,0.1

Type RM Length L Ch R = 1,5142,1090,1090,1090
BEGIN DESCRIPTION:
Mapping XS 4c216143
END DESCRIPTION:
XS GIS Cut Line= 3
      2269755.12     13320077.38      2269060.84     13319326.19
      2268275.52     13318774.20
#Sta/Elev= 30
  3963.1  175.80  4202.2  173.13  4344.0  172.12  4605.4  171.61  4810.7  170.58
  4888.9  169.63  5006.5  169.36  5009.3  168.86  5012.5  169.36  5030.5  169.92
  5196.9  170.11  5209.8  170.65  5253.5  170.33  5274.4  170.99  5339.7  171.27
  5354.6  170.95  5375.5  171.65  5417.6  171.62  5440.8  172.30  5491.0  172.41
  5503.6  172.01  5562.8  172.68  5583.7  172.27  5604.6  172.72  5613.2  172.38
  5625.5  173.01  5676.1  172.90  5684.8  173.47  5899.1  173.46  5945.9  174.12
#Mann=3,-1,0
  3963.1    0.05       0  5006.5    0.03       0  5012.5    0.05       0
Bank Sta=5006.5,5012.5
Exp/Cntr=0.3,0.1

Type RM Length L Ch R = 1,4052,323,323,323
BEGIN DESCRIPTION:
UNT052 IN SPCR 6.0
END DESCRIPTION:
XS GIS Cut Line= 3
      2270157.43     13319663.56      2268883.76     13318110.47
      2268188.14     13318142.09
#Sta/Elev= 30
  3505.0  174.50  3658.4  172.45  3836.2  171.74  3912.9  171.21  4359.7  169.68
  4361.4  169.71  4411.9  168.95  4483.6  168.71  4490.6  169.21  4510.9  169.10
  4518.8  169.78  4539.6  169.10  4597.0  169.36  4643.6  168.59  4646.3  168.09
  4649.6  168.59  4675.3  169.17  4713.3  168.85  5058.5  169.43  5101.6  168.78
  5250.1  169.82  5406.6  169.46  5427.7  170.39  5435.3  169.72  5464.0  169.44
  5529.6  170.58  5599.7  170.97  5609.7  170.17  5819.9  172.58  6209.9  172.93
#Mann=9,-1,0
  3505.0    0.05       0  3836.2    0.08       0  3912.9    0.05       0
  4359.7    0.08       0  4361.4    0.05       0  4490.6    0.08       0
  4643.6   0.035       0  4649.6    0.08       0  4713.3    0.05       0
Bank Sta=4643.6,4649.6
Exp/Cntr=0.3,0.1

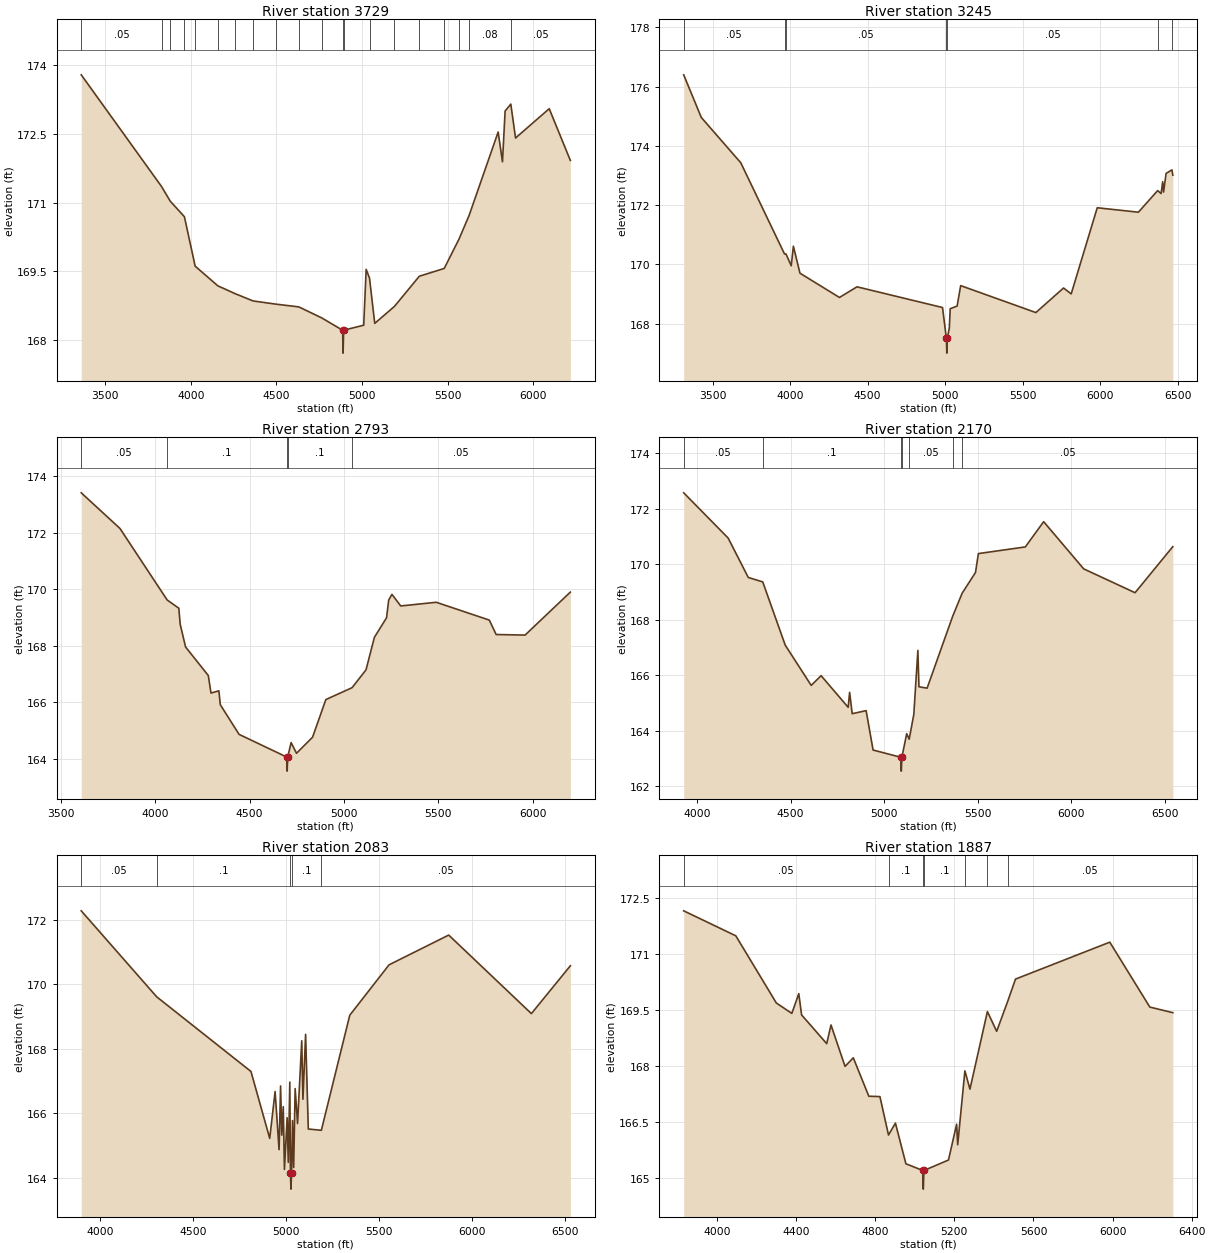
Type RM Length L Ch R = 1,3729,484,484,484
BEGIN DESCRIPTION:
UNT052 IN SPCR 5.0
END DESCRIPTION:
XS GIS Cut Line= 3
      2270246.14     13319466.61      2268675.43     13317641.72
      2268233.01     13317558.76
#Sta/Elev= 30
  3359.5  173.79  3828.6  171.35  3879.5  171.03  3962.3  170.69  4025.1  169.61
  4157.6  169.18  4258.2  169.01  4363.4  168.85  4497.1  168.78  4630.8  168.72
  4764.5  168.48  4886.7  168.21  4889.4  167.71  4892.7  168.21  5010.0  168.32
  5024.3  169.54  5043.8  169.35  5074.4  168.36  5189.4  168.73  5334.9  169.39
  5480.4  169.56  5566.7  170.20  5626.0  170.72  5795.5  172.54  5820.8  171.89
  5836.2  173.00  5869.5  173.15  5897.2  172.41  6093.9  173.05  6217.4  171.92
#Mann=20,-1,0
  3359.5    0.05       0  3828.6     0.1       0  3879.5    0.05       0
  3962.3     0.1       0  4025.1    0.08       0  4157.6    0.05       0
  4258.2    0.08       0  4363.4    0.05       0  4497.1    0.05       0
  4630.8    0.05       0  4764.5    0.05       0  4886.7    0.04       0
  4892.7    0.05       0  5043.8    0.08       0  5189.4    0.08       0
  5334.9    0.08       0  5480.4    0.08       0  5566.7    0.05       0
  5626.0    0.08       0  5869.5    0.05       0
Bank Sta=4886.7,4892.7
Exp/Cntr=0.3,0.1

Type RM Length L Ch R = 1,3245,452,452,452
BEGIN DESCRIPTION:
UNT052 IN SPCR 4.0
END DESCRIPTION:
XS GIS Cut Line= 3
      2270778.00     13319187.14      2269587.72     13317996.85
      2268301.76     13317282.43
#Sta/Elev= 30
  3314.1  176.40  3427.6  174.96  3682.2  173.43  3964.2  170.35  3973.8  170.35
  4007.5  169.95  4021.6  170.61  4064.0  169.70  4318.6  168.88  4431.7  169.24
  4983.3  168.54  5008.1  167.50  5010.9  167.00  5014.1  167.50  5027.2  167.85
  5032.9  168.50  5077.5  168.59  5100.4  169.28  5585.4  168.37  5763.9  169.20
  5813.1  169.00  5981.2  171.91  6246.6  171.76  6370.8  172.49  6393.0  172.39
  6403.3  172.79  6409.1  172.44  6425.1  173.07  6462.8  173.19  6468.5  173.01
#Mann=7,-1,0
  3314.1    0.05       0  3964.2     0.1       0  3973.8    0.05       0
  5008.1   0.035       0  5014.1    0.05       0  6370.8    0.08       0
  6462.8    0.05       0
Bank Sta=5008.1,5014.1
Exp/Cntr=0.3,0.1

Type RM Length L Ch R = 1,2793,623,623,623
BEGIN DESCRIPTION:
UNT052 IN SPCR 3.0
END DESCRIPTION:
XS GIS Cut Line= 3
      2270916.17     13318828.46      2269987.72     13317796.85
      2268888.58     13317308.35
#Sta/Elev= 30
  3608.7  173.41  3813.8  172.15  4064.0  169.62  4125.5  169.33  4132.9  168.76
  4161.3  167.96  4281.7  166.95  4295.9  166.33  4337.7  166.41  4345.2  165.92
  4444.6  164.87  4696.5  164.07  4699.2  163.57  4702.5  164.07  4720.4  164.58
  4748.8  164.20  4834.0  164.77  4904.3  166.10  5043.1  166.52  5117.0  167.15
  5161.4  168.30  5225.7  168.99  5237.3  169.62  5254.4  169.82  5300.9  169.41
  5489.0  169.54  5770.1  168.91  5806.4  168.40  5959.6  168.38  6199.4  169.90
#Mann=5,-1,0
  3608.7    0.05       0  4064.0     0.1       0  4696.5    0.07       0
  4702.5     0.1       0  5043.1    0.05       0
Bank Sta=4696.5,4702.5
Exp/Cntr=0.3,0.1

Type RM Length L Ch R = 1,2170,87,87,87
BEGIN DESCRIPTION:
Mapping XS b2bcfd30
END DESCRIPTION:
XS GIS Cut Line= 5
      2271075.45     13318592.11      2270546.17     13317687.21
      2270506.33     13317590.46      2270329.91     13317493.72
      2269174.64     13316992.91
#Sta/Elev= 30
  3928.6  172.58  4166.1  170.95  4273.6  169.53  4350.9  169.37  4471.1  167.09
  4609.9  165.64  4662.8  165.99  4807.4  164.85  4815.1  165.39  4828.9  164.62
  4903.3  164.73  4940.5  163.31  5088.4  163.05  5091.1  162.55  5094.4  163.05
  5120.1  163.90  5133.3  163.70  5158.0  164.59  5179.8  166.90  5185.5  165.59
  5229.1  165.54  5365.7  168.13  5416.2  168.96  5487.7  169.71  5503.1  170.39
  5753.8  170.63  5851.9  171.54  6065.6  169.84  6340.2  168.98  6541.9  170.64
#Mann=7,-1,0
  3928.6    0.05       0  4350.9     0.1       0  5088.4    0.07       0
  5094.4     0.1       0  5133.3    0.05       0  5365.7     0.1       0
  5416.2    0.05       0
Bank Sta=5088.4,5094.4
Exp/Cntr=0.3,0.1

Type RM Length L Ch R = 1,2083,196,196,196
BEGIN DESCRIPTION:
Mapping XS a9d41459
END DESCRIPTION:
XS GIS Cut Line= 4
      2271189.24     13318518.08      2270614.46     13317630.30
      2270512.02     13317499.41      2269214.47     13316953.07
#Sta/Elev= 30
  3896.5  172.27  4302.4  169.61  4809.7  167.30  4910.6  165.23  4939.6  166.68
  4960.9  164.88  4969.0  166.85  4975.3  165.33  4983.5  166.21  4989.8  164.27
  5004.3  165.87  5010.6  164.49  5018.7  166.97  5022.1  164.16  5024.8  163.66
  5028.1  164.16  5033.2  165.78  5039.5  164.33  5047.4  166.77  5060.4  165.69
  5082.9  168.25  5089.3  166.44  5103.7  168.45  5118.2  165.52  5188.4  165.48
  5341.3  169.04  5552.8  170.60  5873.7  171.52  6318.5  169.09  6528.2  170.57
#Mann=5,-1,0
  3896.5    0.05       0  4302.4     0.1       0  5022.1    0.07       0
  5028.1     0.1       0  5188.4    0.05       0
Bank Sta=5022.1,5028.1
Exp/Cntr=0.3,0.1

Type RM Length L Ch R = 1,1887,734,734,734
BEGIN DESCRIPTION:
UNT052 IN SPCR 2.0
END DESCRIPTION:
XS GIS Cut Line= 3
      2271493.21     13318283.29      2270737.72     13317446.85
      2269466.92     13317002.09
#Sta/Elev= 30
  3831.2  172.15  4094.8  171.48  4299.6  169.68  4378.0  169.40  4413.2  169.93
  4427.4  169.36  4554.4  168.59  4576.1  169.09  4647.1  167.98  4688.9  168.21
  4767.4  167.18  4823.6  167.17  4866.9  166.14  4901.9  166.46  4954.9  165.37
  5040.1  165.19  5042.8  164.69  5046.1  165.19  5170.2  165.47  5211.5  166.43
  5216.8  165.88  5253.2  167.86  5278.8  167.37  5367.1  169.45  5413.9  168.92
  5470.1  169.73  5509.2  170.32  5986.0  171.31  6188.5  169.57  6304.7  169.42
#Mann=7,-1,0
  3831.2    0.05       0  4866.9     0.1       0  5040.1    0.07       0
  5046.1     0.1       0  5253.2    0.05       0  5367.1    0.08       0
  5470.1    0.05       0
Bank Sta=5040.1,5046.1
Exp/Cntr=0.3,0.1

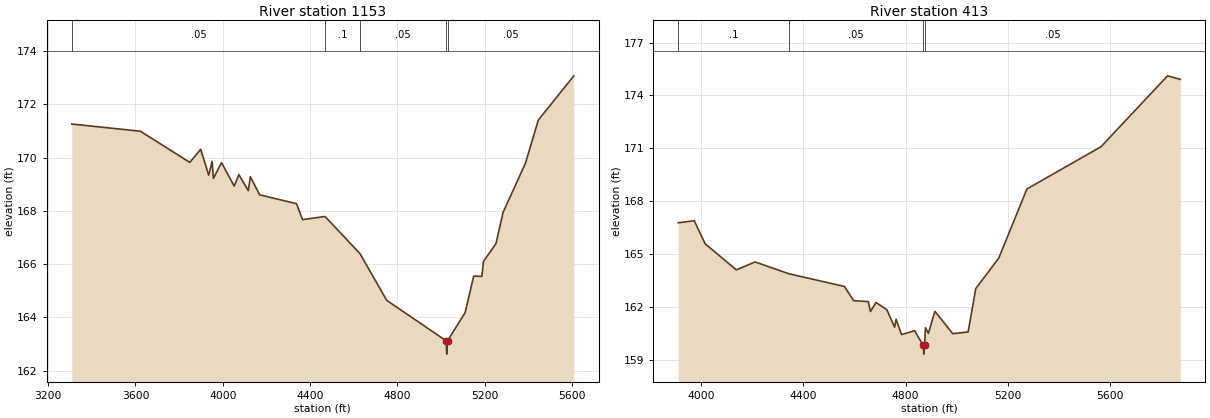
Type RM Length L Ch R = 1,1153,740,740,740
BEGIN DESCRIPTION:
Mapping XS 3b6eb8da
END DESCRIPTION:
XS GIS Cut Line= 3
      2272054.25     13318051.40      2271388.42     13316936.01
      2270432.57     13316634.46
#Sta/Elev= 30
  3308.0  171.26  3622.5  170.99  3849.0  169.82  3898.9  170.31  3935.8  169.34
  3951.4  169.86  3957.2  169.22  3994.2  169.81  4052.6  168.93  4074.0  169.36
  4116.9  168.76  4126.5  169.28  4169.4  168.60  4338.2  168.27  4365.9  167.67
  4468.8  167.79  4629.3  166.39  4751.5  164.64  5024.2  163.12  5026.9  162.62
  5030.2  163.12  5111.1  164.18  5150.2  165.55  5187.8  165.54  5195.0  166.10
  5252.5  166.77  5284.8  167.94  5387.1  169.78  5446.6  171.41  5609.3  173.07
#Mann=5,-1,0
  3308.0    0.05       0  4468.8     0.1       0  4629.3    0.05       0
  5024.2   0.035       0  5030.2    0.05       0
Bank Sta=5024.2,5030.2
Exp/Cntr=0.3,0.1

Type RM Length L Ch R = 1,413,0,0,0
BEGIN DESCRIPTION:
UNT052 IN SPCR 1.0
END DESCRIPTION:
XS GIS Cut Line= 4
      2271561.13     13316807.78      2271022.65     13316477.35
      2270833.03     13316186.97      2269847.83     13316201.99
#Sta/Elev= 30
  3910.8  166.77  3973.5  166.89  4016.1  165.58  4138.0  164.10  4211.5  164.55
  4343.5  163.88  4560.9  163.16  4597.1  162.35  4654.4  162.30  4662.6  161.74
  4684.6  162.25  4726.8  161.84  4757.1  160.85  4763.0  161.30  4784.1  160.43
  4835.4  160.65  4868.6  159.82  4871.4  159.32  4874.6  159.82  4877.6  160.82
  4889.4  160.50  4914.7  161.75  4984.7  160.48  5044.7  160.58  5074.7  163.04
  5164.7  164.77  5274.7  168.69  5564.8  171.09  5824.8  175.11  5874.7  174.91
#Mann=4,-1,0
  3910.8     0.1       0  4343.5    0.05       0  4868.6   0.035       0
  4874.6    0.05       0
Bank Sta=4868.6,4874.6
Exp/Cntr=0.3,0.1

Chan Stop Cuts=-1