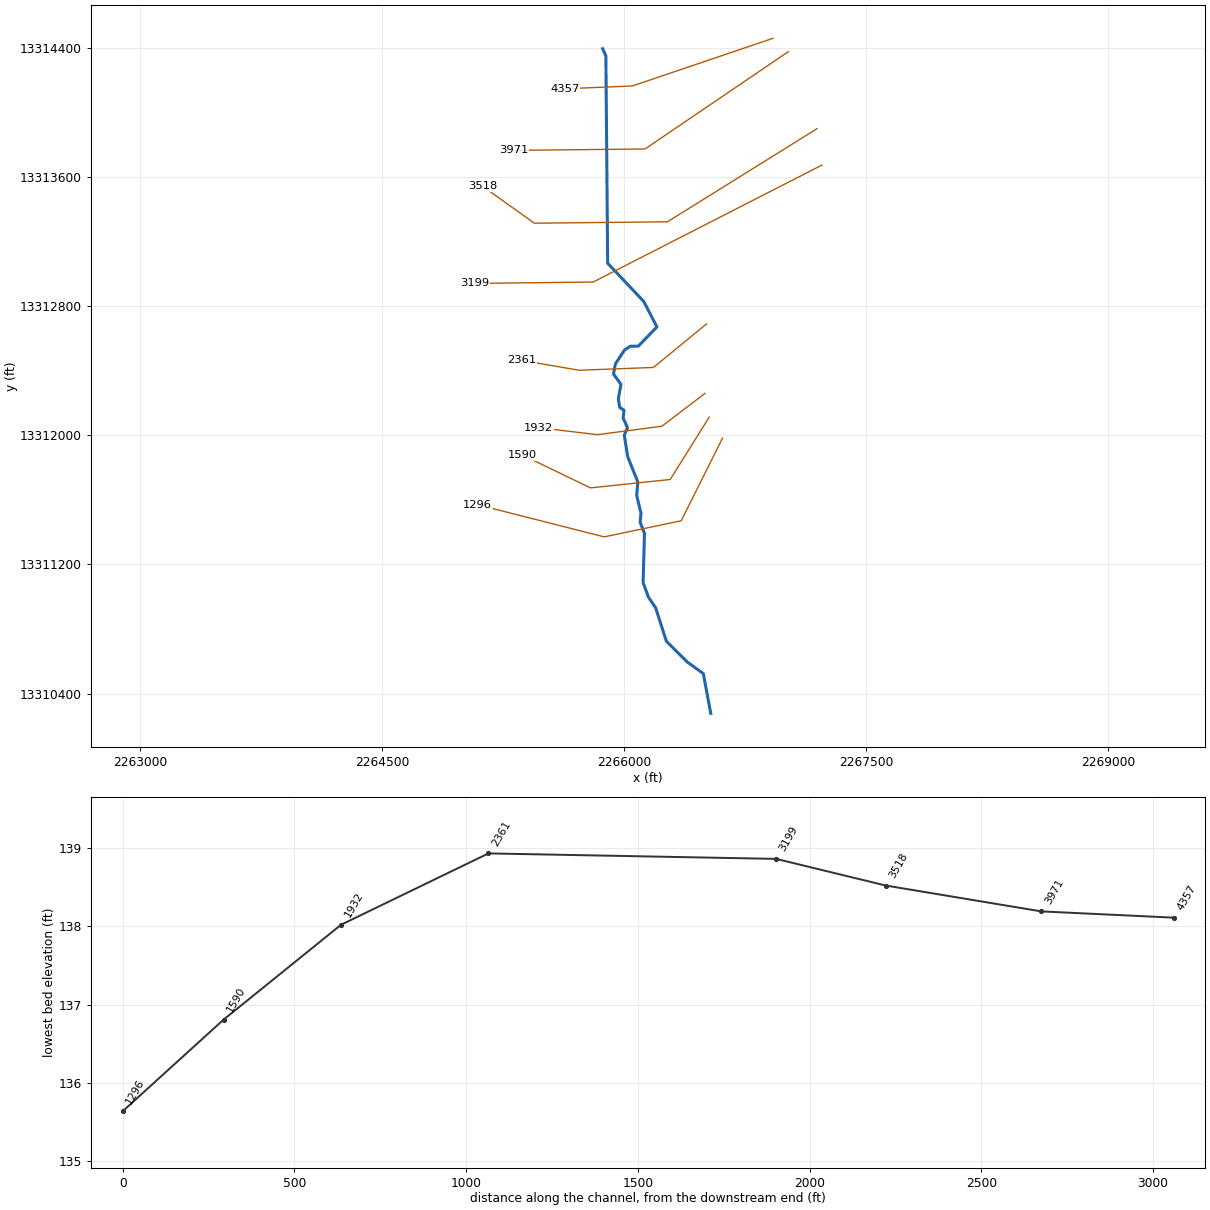
--- UNT053 IN SPCR.prj (project) ---

Proj Title=UNT053 IN SPCR Base Level Engineering
Current Plan=p01
Default Exp/Contr=0.3,0.1
English Units
Geom File=g01
Flow File=f01
Plan File=p01
BEGIN DESCRIPTION:
UNT053 IN SPCR
END DESCRIPTION:

--- UNT053 IN SPCR.p01 (plan) ---

Plan Title=Multiple Run
Short Identifier=Multiple
Geom File=g01
Flow File=f01
Subcritical Flow
K Sum by GR= 0
Std Step Tol= 0.01
Critical Tol= 0.01
Num of Std Step Trials= 20
Max Error Tol= 0.3
Flow Tol Ratio= 0.001
Split Flow NTrial= 30
Split Flow Tol= 0.02
Split Flow Ratio= 0.02
Log Output Level= 0
Friction Slope Method= 1
Unsteady Friction Slope Method= 2
Unsteady Bridges Friction Slope Method= 1
Parabolic Critical Depth
Global Vel Dist=  1 , 1 , 1
Global Log Level= 0
CheckData=True
Encroach Param= -1, 0, 0, 0
BEGIN DESCRIPTION:
Multiple Run
END DESCRIPTION:

--- UNT053 IN SPCR.f01 (steady flow) ---

Flow Title=Multiple
Number of Profiles=7
Profile Names=10-year,25-year,50-year,1pct_min,100-year,1pct_plu,500-year
River Rch & RM= UNT053 IN SPCR,Reach-1,4357
     218     295     356     317     429     580     629
Boundary for River Rch & Prof#=UNT053 IN SPCR,Reach-1,1
Up Type=0
Dn Type=3
Dn Slope=0.005
Boundary for River Rch & Prof#=UNT053 IN SPCR,Reach-1,2
Up Type=0
Dn Type=3
Dn Slope=0.005
Boundary for River Rch & Prof#=UNT053 IN SPCR,Reach-1,3
Up Type=0
Dn Type=3
Dn Slope=0.005
Boundary for River Rch & Prof#=UNT053 IN SPCR,Reach-1,4
Up Type=0
Dn Type=3
Dn Slope=0.005
Boundary for River Rch & Prof#=UNT053 IN SPCR,Reach-1,5
Up Type=0
Dn Type=3
Dn Slope=0.005
Boundary for River Rch & Prof#=UNT053 IN SPCR,Reach-1,6
Up Type=0
Dn Type=3
Dn Slope=0.005
Boundary for River Rch & Prof#=UNT053 IN SPCR,Reach-1,7
Up Type=0
Dn Type=3
Dn Slope=0.005

--- UNT053 IN SPCR.g01 (geometry) ---

Geom Title=Existing Conditions

River Reach=UNT053 IN SPCR,Reach-1
Reach XY= 30
      2265867.72     13314396.85      2265887.68     13314351.84
      2265898.82     13313067.01      2266122.79     13312829.74
      2266204.03     13312672.14      2266088.96     13312553.34
      2266039.07     13312552.59      2266002.92     13312528.82
      2265947.02     13312443.46      2265934.73     13312380.66
      2265981.00     13312316.47      2265965.22     13312226.62
      2265972.57     13312174.60      2266000.06     13312155.43
      2265994.80     13312107.36      2266021.98     13312047.01
      2266001.80     13312001.92      2266023.14     13311866.58
      2266085.70     13311711.89      2266078.74     13311627.31
      2266105.62     13311516.46      2266100.08     13311462.68
      2266126.91     13311391.71      2266118.57     13311087.32
      2266150.96     13310998.20      2266196.14     13310931.20
      2266262.73     13310723.94      2266392.93     13310594.52
      2266491.78     13310523.56      2266537.72     13310276.86

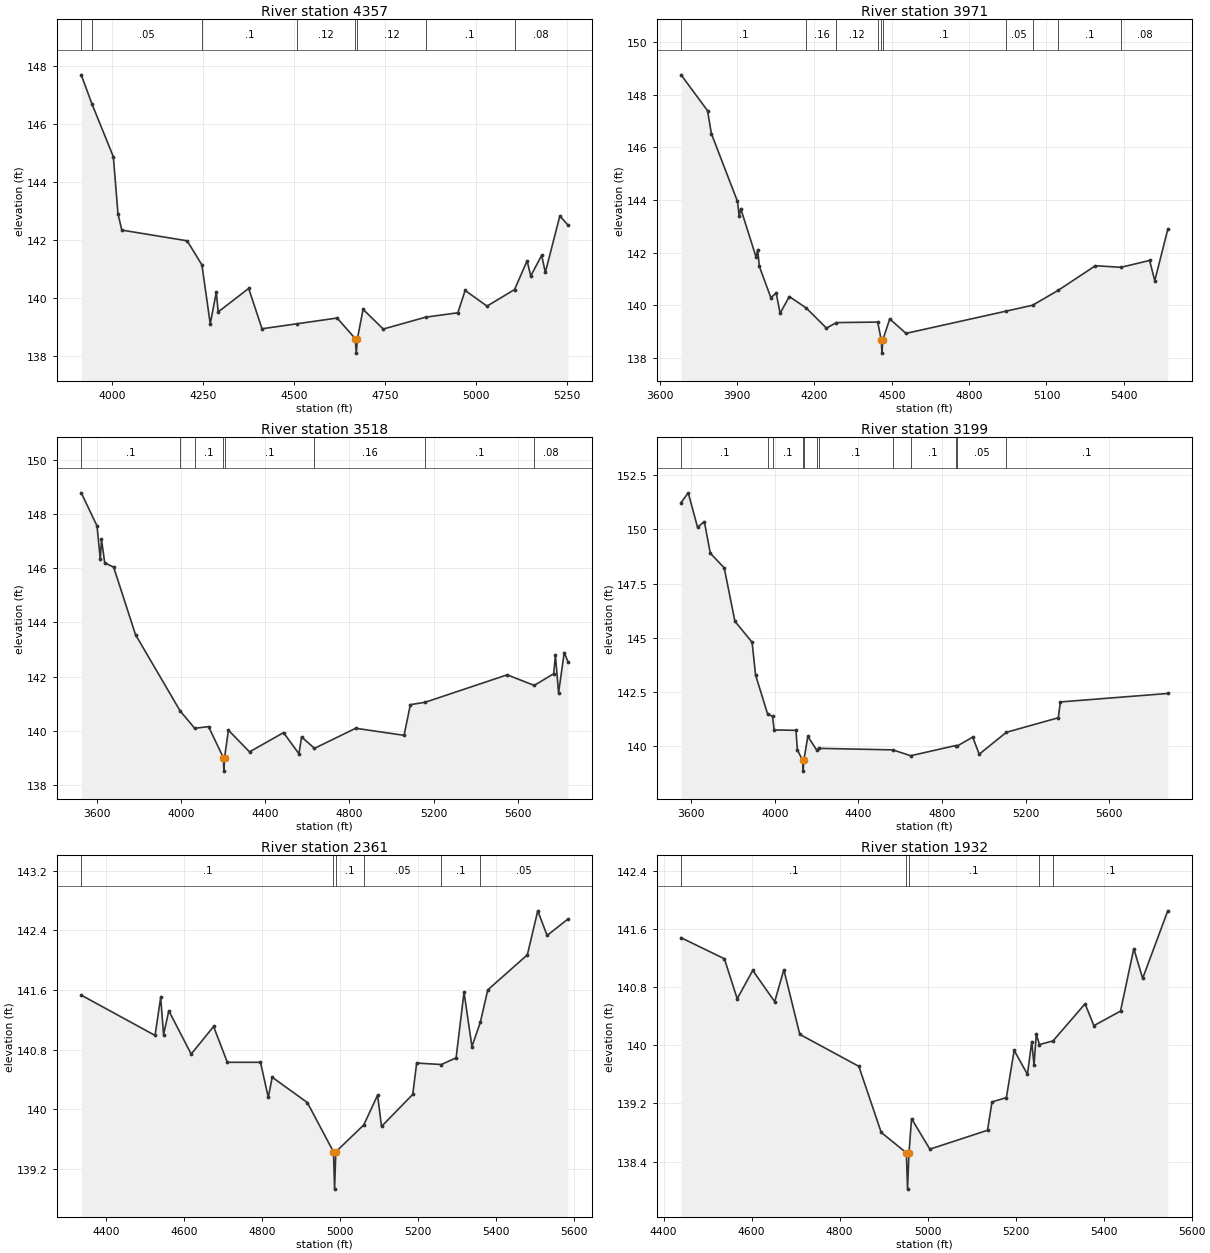
Type RM Length L Ch R = 1,4357,386,386,386
BEGIN DESCRIPTION:
UNT053 IN SPCR 2.0
END DESCRIPTION:
XS GIS Cut Line= 3
      2266923.26     13314461.15      2266052.30     13314165.93
      2265635.59     13314148.57
#Sta/Elev= 30
  3915.6  147.70  3944.6  146.71  4003.7  144.88  4016.5  142.91  4027.0  142.35
  4206.5  141.98  4247.0  141.15  4269.9  139.12  4286.5  140.21  4291.7  139.53
  4375.4  140.34  4412.1  138.95  4507.4  139.12  4618.3  139.32  4668.1  138.61
  4670.9  138.11  4674.1  138.61  4689.6  139.62  4745.0  138.94  4861.8  139.35
  4949.9  139.50  4969.9  140.27  5030.0  139.73  5105.6  140.30  5140.1  141.29
  5150.1  140.77  5180.1  141.48  5190.1  140.89  5230.1  142.84  5252.3  142.52
#Mann=8,-1,0
  3915.6     0.1       0  3944.6    0.05       0  4247.0     0.1       0
  4507.4    0.12       0  4668.1    0.07       0  4674.1    0.12       0
  4861.8     0.1       0  5105.6    0.08       0
Bank Sta=4668.1,4674.1
Exp/Cntr=0.3,0.1

Type RM Length L Ch R = 1,3971,453,453,453
BEGIN DESCRIPTION:
Mapping XS 44c0d5df
END DESCRIPTION:
XS GIS Cut Line= 3
      2267018.70     13314378.66      2266130.43     13313775.31
      2265317.28     13313766.69
#Sta/Elev= 30
  3683.4  148.76  3785.9  147.40  3800.9  146.53  3902.2  143.95  3908.7  143.38
  3914.7  143.68  3974.5  141.83  3980.5  142.12  3986.8  141.49  4031.4  140.30
  4052.4  140.47  4067.3  139.70  4103.2  140.34  4169.3  139.90  4247.0  139.14
  4285.7  139.35  4445.8  139.37  4459.6  138.69  4462.3  138.19  4465.6  138.69
  4492.4  139.49  4555.4  138.94  4941.4  139.78  5046.7  140.01  5144.8  140.57
  5289.9  141.51  5388.8  141.45  5500.0  141.71  5520.0  140.94  5570.4  142.89
#Mann=10,-1,0
  3683.4     0.1       0  4169.3    0.16       0  4285.7    0.12       0
  4445.8     0.1       0  4459.6   0.035       0  4465.6     0.1       0
  4941.4    0.05       0  5046.7    0.16       0  5144.8     0.1       0
  5388.8    0.08       0
Bank Sta=4459.6,4465.6
Exp/Cntr=0.3,0.1

Type RM Length L Ch R = 1,3518,319,319,319
BEGIN DESCRIPTION:
Mapping XS 9f0c5bb1
END DESCRIPTION:
XS GIS Cut Line= 4
      2267196.68     13313901.25      2266269.32     13313323.92
      2265444.66     13313315.24      2265122.40     13313545.06
#Sta/Elev= 30
  3525.9  148.78  3600.8  147.56  3616.2  146.34  3622.1  147.06  3637.4  146.20
  3679.9  146.04  3783.8  143.55  3995.8  140.74  4064.9  140.10  4130.8  140.16
  4201.0  139.02  4203.7  138.52  4207.0  139.02  4225.2  140.03  4325.7  139.23
  4487.2  139.94  4560.4  139.16  4573.0  139.78  4634.3  139.36  4829.9  140.10
  5059.9  139.84  5089.9  140.97  5160.7  141.06  5549.8  142.07  5678.6  141.68
  5770.9  142.11  5779.3  142.79  5794.1  141.40  5821.1  142.89  5838.8  142.55
#Mann=8,-1,0
  3525.9     0.1       0  3995.8    0.16       0  4064.9     0.1       0
  4201.0    0.07       0  4207.0     0.1       0  4634.3    0.16       0
  5160.7     0.1       0  5678.6    0.08       0
Bank Sta=4201,4207
Exp/Cntr=0.3,0.1

Type RM Length L Ch R = 1,3199,838,838,838
BEGIN DESCRIPTION:
Mapping XS 2df00841
END DESCRIPTION:
XS GIS Cut Line= 3
      2267227.01     13313675.53      2265809.25     13312950.66
      2265074.22     13312942.04
#Sta/Elev= 30
  3551.8  151.24  3586.1  151.69  3630.5  150.11  3663.3  150.36  3691.5  148.91
  3758.2  148.23  3809.3  145.77  3891.5  144.80  3908.1  143.29  3965.8  141.49
  3989.1  141.39  3996.9  140.76  4101.3  140.74  4108.0  139.84  4132.8  139.36
  4135.6  138.86  4138.8  139.36  4158.0  140.46  4200.6  139.83  4212.8  139.91
  4564.1  139.84  4649.7  139.57  4864.8  140.04  4871.1  140.01  4946.5  140.43
  4977.4  139.64  5107.4  140.65  5355.7  141.32  5365.7  142.05  5879.2  142.44
#Mann=12,-1,0
  3551.8     0.1       0  3965.8    0.16       0  3989.1     0.1       0
  4132.8   0.035       0  4138.8     0.1       0  4200.6    0.16       0
  4212.8     0.1       0  4564.1    0.16       0  4649.7     0.1       0
  4864.8    0.16       0  4871.1    0.05       0  5107.4     0.1       0
Bank Sta=4132.8,4138.8
Exp/Cntr=0.3,0.1

Type RM Length L Ch R = 1,2361,429,429,429
BEGIN DESCRIPTION:
Mapping XS 29bea9fa
END DESCRIPTION:
XS GIS Cut Line= 4
      2266510.89     13312690.29      2266182.51     13312421.14
      2265722.44     13312403.78      2265365.07     13312464.61
#Sta/Elev= 30
  4336.8  141.53  4526.0  140.99  4540.4  141.50  4547.8  141.00  4561.2  141.32
  4618.6  140.74  4676.0  141.11  4711.2  140.63  4796.2  140.63  4816.2  140.16
  4826.2  140.43  4916.3  140.09  4983.3  139.43  4986.1  138.93  4989.3  139.43
  5060.9  139.79  5096.4  140.19  5106.4  139.77  5186.5  140.20  5196.5  140.62
  5259.8  140.60  5297.6  140.69  5317.9  141.57  5338.2  140.84  5359.9  141.17
  5378.7  141.60  5480.2  142.07  5506.9  142.66  5530.9  142.33  5584.3  142.55
#Mann=6,-1,0
  4336.8     0.1       0  4983.3    0.07       0  4989.3     0.1       0
  5060.9    0.05       0  5259.8     0.1       0  5359.9    0.05       0
Bank Sta=4983.3,4989.3
Exp/Cntr=0.3,0.1

Type RM Length L Ch R = 1,1932,342,342,342
BEGIN DESCRIPTION:
Mapping XS 9ae5905d
END DESCRIPTION:
XS GIS Cut Line= 4
      2266502.26     13312260.64      2266234.59     13312056.56
      2265835.29     13312004.48      2265471.03     13312047.73
#Sta/Elev= 30
  4439.6  141.48  4538.1  141.19  4567.2  140.64  4602.5  141.03  4652.4  140.60
  4673.2  141.04  4709.4  140.15  4843.6  139.71  4894.5  138.80  4951.6  138.52
  4954.3  138.02  4957.6  138.52  4963.4  138.99  5005.0  138.57  5136.1  138.83
  5146.2  139.22  5178.9  139.28  5196.6  139.93  5226.8  139.60  5236.6  140.05
  5241.7  139.73  5246.9  140.15  5254.1  140.01  5284.9  140.06  5357.7  140.57
  5377.8  140.27  5438.3  140.47  5468.5  141.33  5488.6  140.92  5545.7  141.85
#Mann=5,-1,0
  4439.6     0.1       0  4951.6    0.07       0  4957.6     0.1       0
  5254.1    0.05       0  5284.9     0.1       0
Bank Sta=4951.6,4957.6
Exp/Cntr=0.3,0.1

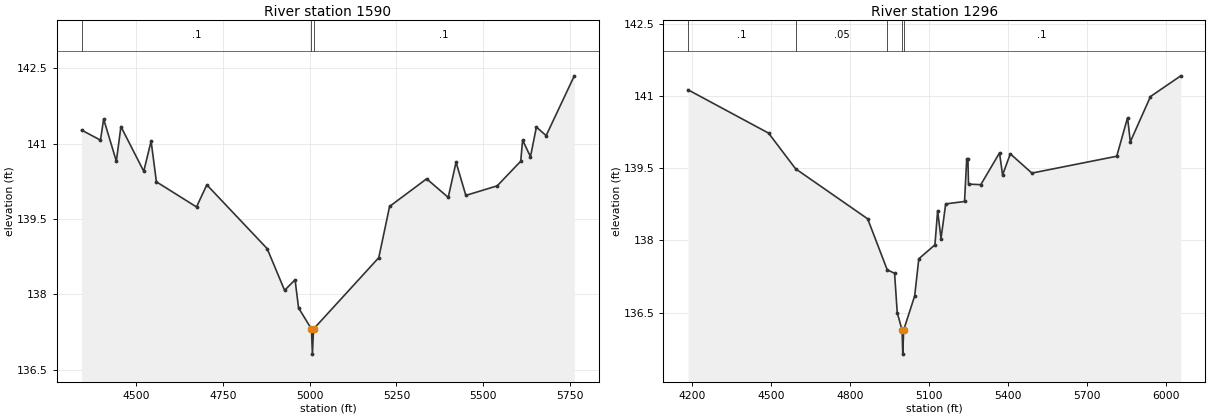
Type RM Length L Ch R = 1,1590,294,294,294
BEGIN DESCRIPTION:
Mapping XS 2453edac
END DESCRIPTION:
XS GIS Cut Line= 4
      2266528.27     13312113.06      2266286.68     13311726.70
      2265791.89     13311674.61      2265371.10     13311877.86
#Sta/Elev= 30
  4342.2  141.27  4396.7  141.07  4405.9  141.49  4442.5  140.65  4455.7  141.34
  4521.5  140.45  4542.7  141.05  4558.0  140.24  4673.6  139.74  4703.3  140.18
  4877.3  138.91  4927.5  138.08  4957.7  138.29  4967.8  137.73  5005.0  137.31
  5007.7  136.81  5011.0  137.31  5199.0  138.73  5230.2  139.75  5337.0  140.30
  5399.2  139.93  5421.8  140.63  5450.0  139.97  5540.4  140.16  5608.2  140.65
  5613.7  141.07  5636.3  140.74  5653.4  141.33  5681.5  141.16  5762.7  142.35
#Mann=3,-1,0
  4342.2     0.1       0  5005.0    0.07       0  5011.0     0.1       0
Bank Sta=5005,5011
Exp/Cntr=0.3,0.1

Type RM Length L Ch R = 1,1296,0,0,0
BEGIN DESCRIPTION:
UNT053 IN SPCR 1.0
END DESCRIPTION:
XS GIS Cut Line= 4
      2266610.74     13311982.85      2266354.65     13311470.69
      2265877.22     13311370.86      2265092.15     13311570.38
#Sta/Elev= 30
  4185.7  141.13  4491.5  140.23  4593.9  139.49  4867.6  138.45  4941.9  137.39
  4969.7  137.32  4979.9  136.50  4998.2  136.14  5000.9  135.64  5004.2  136.14
  5046.1  136.85  5061.7  137.62  5123.0  137.91  5133.2  138.62  5146.0  138.04
  5163.8  138.76  5235.3  138.81  5243.6  139.69  5248.1  139.69  5250.4  139.17
  5297.1  139.16  5368.1  139.82  5379.7  139.36  5409.0  139.80  5490.9  139.40
  5813.0  139.75  5854.1  140.55  5864.6  140.05  5941.1  140.99  6056.1  141.42
#Mann=5,-1,0
  4185.7     0.1       0  4593.9    0.05       0  4941.9     0.1       0
  4998.2    0.07       0  5004.2     0.1       0
Bank Sta=4998.2,5004.2
Exp/Cntr=0.3,0.1

Chan Stop Cuts=-1