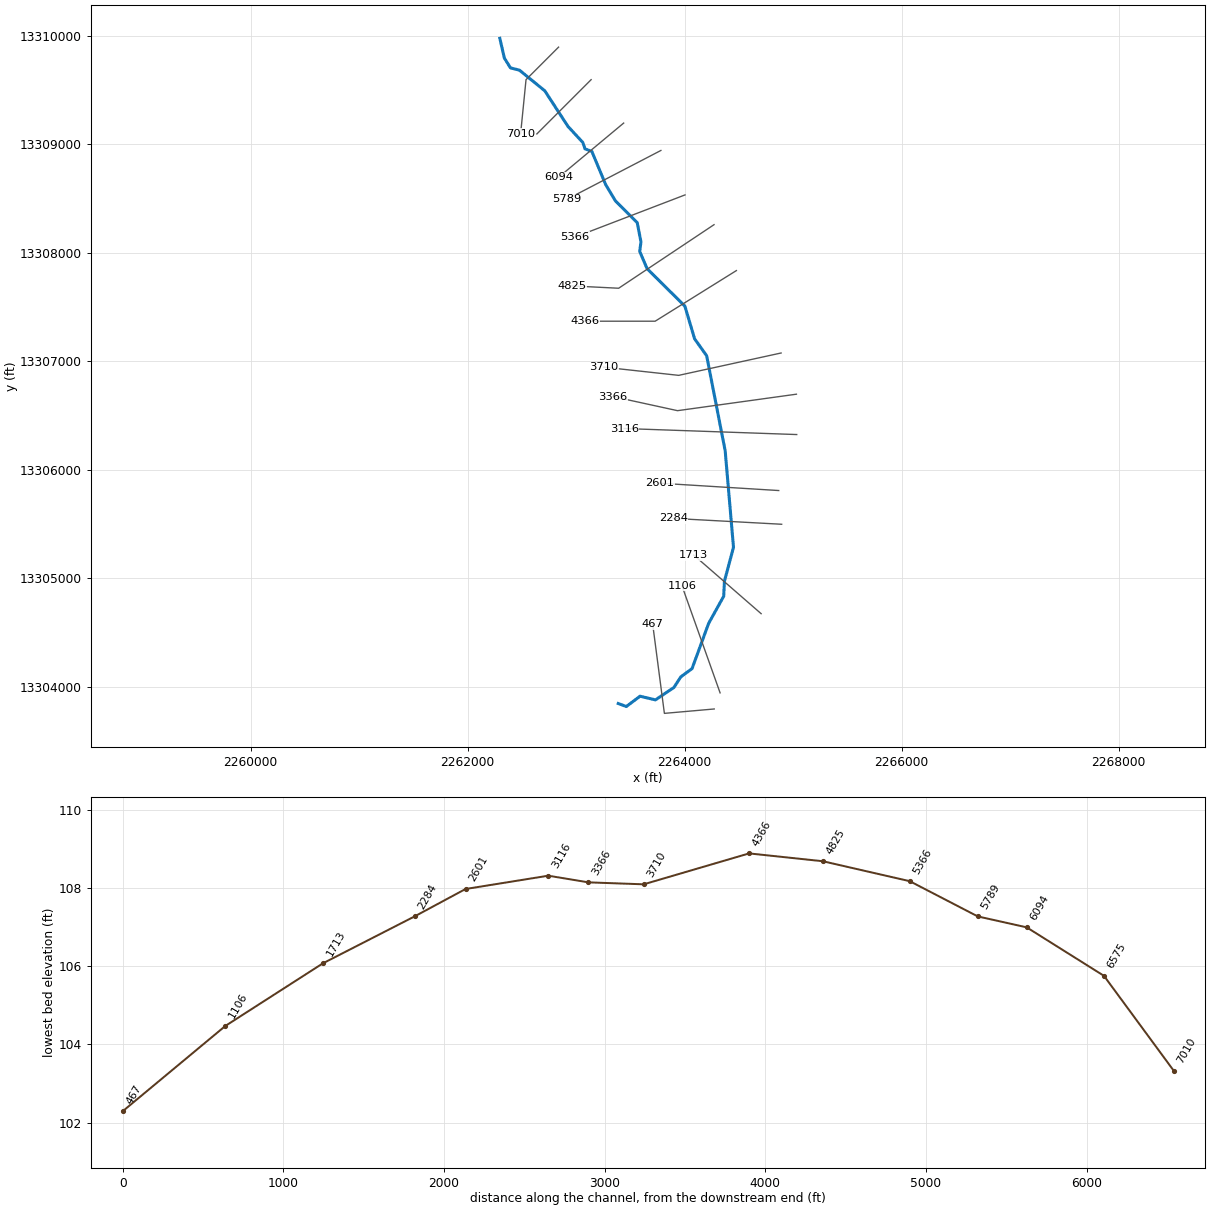
--- UNT054 IN SPCR.prj (project) ---

Proj Title=UNT054 IN SPCR Base Level Engineering
Current Plan=p01
Default Exp/Contr=0.3,0.1
English Units
Geom File=g01
Flow File=f01
Plan File=p01
BEGIN DESCRIPTION:
UNT054 IN SPCR
END DESCRIPTION:

--- UNT054 IN SPCR.p01 (plan) ---

Plan Title=Multiple Run
Short Identifier=Multiple
Geom File=g01
Flow File=f01
Subcritical Flow
K Sum by GR= 0
Std Step Tol= 0.01
Critical Tol= 0.01
Num of Std Step Trials= 20
Max Error Tol= 0.3
Flow Tol Ratio= 0.001
Split Flow NTrial= 30
Split Flow Tol= 0.02
Split Flow Ratio= 0.02
Log Output Level= 0
Friction Slope Method= 1
Unsteady Friction Slope Method= 2
Unsteady Bridges Friction Slope Method= 1
Parabolic Critical Depth
Global Vel Dist=  1 , 1 , 1
Global Log Level= 0
CheckData=True
Encroach Param= -1, 0, 0, 0
BEGIN DESCRIPTION:
Multiple Run
END DESCRIPTION:

--- UNT054 IN SPCR.f01 (steady flow) ---

Flow Title=Multiple
Number of Profiles=7
Profile Names=10-year,25-year,50-year,1pct_min,100-year,1pct_plu,500-year
River Rch & RM= UNT054 IN SPCR,Reach-1,7010
     112     145     170     147     199     269     275
River Rch & RM= UNT054 IN SPCR,Reach-1,5366
     129     168     198     171     232     313     322
River Rch & RM= UNT054 IN SPCR,Reach-1,2601
     139     181     214     185     251     339     351
Boundary for River Rch & Prof#=UNT054 IN SPCR,Reach-1,1
Up Type=0
Dn Type=3
Dn Slope=0.005
Boundary for River Rch & Prof#=UNT054 IN SPCR,Reach-1,2
Up Type=0
Dn Type=3
Dn Slope=0.005
Boundary for River Rch & Prof#=UNT054 IN SPCR,Reach-1,3
Up Type=0
Dn Type=3
Dn Slope=0.005
Boundary for River Rch & Prof#=UNT054 IN SPCR,Reach-1,4
Up Type=0
Dn Type=3
Dn Slope=0.005
Boundary for River Rch & Prof#=UNT054 IN SPCR,Reach-1,5
Up Type=0
Dn Type=3
Dn Slope=0.005
Boundary for River Rch & Prof#=UNT054 IN SPCR,Reach-1,6
Up Type=0
Dn Type=3
Dn Slope=0.005
Boundary for River Rch & Prof#=UNT054 IN SPCR,Reach-1,7
Up Type=0
Dn Type=3
Dn Slope=0.005

--- UNT054 IN SPCR.g01 (geometry) ---

Geom Title=Existing Conditions

River Reach=UNT054 IN SPCR,Reach-1
Reach XY= 30
      2262296.32     13309977.86      2262337.72     13309796.85
      2262393.97     13309705.35      2262476.73     13309684.65
      2262710.25     13309494.63      2262924.30     13309166.16
      2263061.35     13309017.87      2263081.53     13308959.13
      2263144.71     13308934.96      2263271.96     13308629.22
      2263361.89     13308479.38      2263562.46     13308279.39
      2263597.11     13308102.39      2263585.78     13308013.61
      2263653.57     13307854.81      2264001.93     13307509.42
      2264091.45     13307208.40      2264202.72     13307051.85
      2264373.58     13306175.23      2264449.97     13305286.34
      2264366.64     13304973.84      2264359.69     13304834.95
      2264220.80     13304584.95      2264068.03     13304168.28
      2263963.86     13304091.89      2263901.36     13303994.67
      2263730.63     13303880.01      2263588.67     13303913.94
      2263461.97     13303818.90      2263387.72     13303846.86

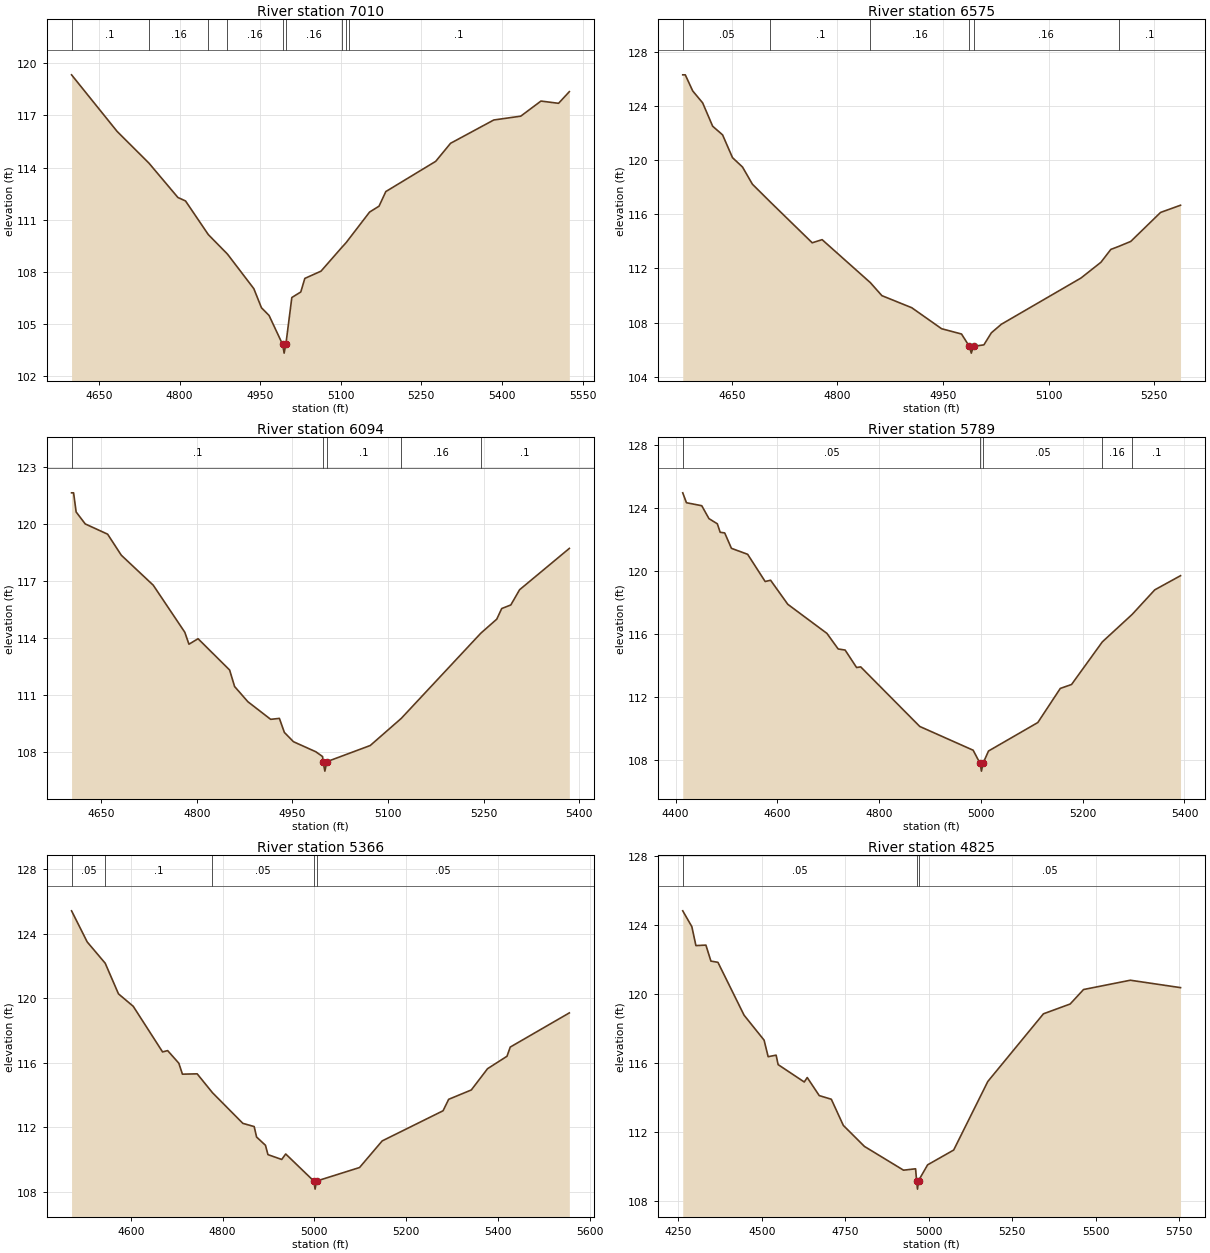
Type RM Length L Ch R = 1,7010,435,435,435
BEGIN DESCRIPTION:
UNT054 IN SPCR 10.0
END DESCRIPTION:
XS GIS Cut Line= 3
      2262837.74     13309896.87      2262537.72     13309596.85
      2262487.72     13309096.84
#Sta/Elev= 30
  4598.7  119.34  4683.6  116.08  4742.7  114.26  4796.7  112.28  4810.9  112.08
  4853.4  110.14  4889.0  109.02  4938.1  107.03  4952.3  105.93  4966.4  105.49
  4991.7  103.82  4994.5  103.32  4997.7  103.82  5008.8  106.52  5025.5  106.84
  5033.0  107.62  5063.2  108.04  5101.4  109.39  5110.2  109.69  5114.6  109.87
  5153.6  111.44  5171.2  111.78  5183.8  112.62  5276.7  114.36  5304.4  115.40
  5384.8  116.74  5435.0  116.96  5472.7  117.83  5505.4  117.70  5525.5  118.37
#Mann=9,-1,0
  4598.7     0.1       0  4742.7    0.16       0  4853.4     0.1       0
  4889.0    0.16       0  4991.7    0.07       0  4997.7    0.16       0
  5101.4    0.05       0  5110.2    0.16       0  5114.6     0.1       0
Bank Sta=4991.7,4997.7
Exp/Cntr=0.3,0.1

Type RM Length L Ch R = 1,6575,481,481,481
BEGIN DESCRIPTION:
UNT054 IN SPCR 9.0
END DESCRIPTION:
XS GIS Cut Line= 3
      2263137.74     13309596.87      2262837.72     13309296.85
      2262637.74     13309096.88
#Sta/Elev= 30
  4580.4  126.28  4584.0  126.28  4594.6  125.09  4608.7  124.21  4622.9  122.49
  4637.0  121.85  4651.1  120.17  4665.3  119.48  4679.4  118.21  4704.8  116.90
  4764.3  113.89  4778.4  114.12  4846.9  110.95  4863.3  109.99  4905.7  109.10
  4948.1  107.55  4976.4  107.16  4987.5  106.25  4990.3  105.75  4993.5  106.25
  5008.2  106.36  5018.8  107.25  5033.0  107.88  5146.1  111.29  5174.4  112.45
  5188.5  113.40  5199.6  113.62  5216.8  113.99  5259.2  116.13  5287.5  116.66
#Mann=6,-1,0
  4580.4    0.05       0  4704.8     0.1       0  4846.9    0.16       0
  4987.5    0.07       0  4993.5    0.16       0  5199.6     0.1       0
Bank Sta=4987.5,4993.5
Exp/Cntr=0.3,0.1

Type RM Length L Ch R = 1,6094,305,305,305
BEGIN DESCRIPTION:
UNT054 IN SPCR 8.0
END DESCRIPTION:
XS GIS Cut Line= 3
      2263437.72     13309196.85      2263137.72     13308946.85
      2262837.73     13308696.87
#Sta/Elev= 30
  4603.5  121.66  4606.7  121.66  4610.7  120.65  4625.0  120.02  4660.1  119.48
  4681.6  118.37  4731.7  116.79  4781.2  114.31  4787.7  113.68  4802.0  113.97
  4851.5  112.32  4859.3  111.45  4880.1  110.65  4915.9  109.72  4929.6  109.77
  4937.4  109.03  4951.7  108.54  4986.8  108.01  4997.3  107.76  4998.2  107.49
  5000.9  106.99  5004.2  107.49  5072.1  108.34  5120.8  109.77  5245.6  114.26
  5270.6  115.00  5278.4  115.56  5292.7  115.75  5306.4  116.55  5384.5  118.73
#Mann=5,-1,0
  4603.5     0.1       0  4998.2    0.07       0  5004.2     0.1       0
  5120.8    0.16       0  5245.6     0.1       0
Bank Sta=4998.2,5004.2
Exp/Cntr=0.3,0.1

Type RM Length L Ch R = 1,5789,423,423,423
BEGIN DESCRIPTION:
UNT054 IN SPCR 7.0
END DESCRIPTION:
XS GIS Cut Line= 2
      2263780.92     13308944.31      2262912.86     13308492.92
#Sta/Elev= 30
  4413.9  124.97  4421.2  124.34  4451.3  124.15  4465.4  123.33  4481.9  123.00
  4487.5  122.46  4496.4  122.42  4509.6  121.44  4541.5  121.06  4575.9  119.33
  4586.6  119.41  4620.4  117.88  4697.3  116.03  4719.4  115.04  4733.1  114.97
  4755.6  113.86  4763.7  113.90  4879.8  110.11  4984.7  108.60  4998.2  107.77
  5001.0  107.27  5004.2  107.77  5014.9  108.55  5111.8  110.36  5156.0  112.53
  5178.1  112.78  5238.6  115.49  5297.3  117.24  5341.7  118.80  5392.3  119.70
#Mann=5,-1,0
  4413.9    0.05       0  4998.2   0.035       0  5004.2    0.05       0
  5238.6    0.16       0  5297.3     0.1       0
Bank Sta=4998.2,5004.2
Exp/Cntr=0.3,0.1

Type RM Length L Ch R = 1,5366,541,541,541
BEGIN DESCRIPTION:
UNT054 IN SPCR 6.0
END DESCRIPTION:
XS GIS Cut Line= 2
      2264003.16     13308534.59      2262990.96     13308146.35
#Sta/Elev= 30
  4471.1  125.43  4505.2  123.50  4544.4  122.18  4573.3  120.28  4605.4  119.51
  4669.3  116.68  4680.4  116.76  4704.7  115.98  4712.6  115.30  4744.7  115.32
  4778.0  114.15  4844.1  112.25  4868.8  112.05  4874.1  111.40  4893.4  110.89
  4898.8  110.31  4928.8  110.01  4937.5  110.35  4998.7  108.67  5001.5  108.17
  5004.7  108.67  5098.3  109.51  5147.6  111.16  5280.2  113.03  5292.4  113.74
  5341.7  114.32  5377.1  115.64  5419.4  116.41  5426.5  116.98  5555.2  119.10
#Mann=5,-1,0
  4471.1    0.05       0  4544.4     0.1       0  4778.0    0.05       0
  4998.7   0.035       0  5004.7    0.05       0
Bank Sta=4998.7,5004.7
Exp/Cntr=0.3,0.1

Type RM Length L Ch R = 1,4825,459,459,459
BEGIN DESCRIPTION:
UNT054 IN SPCR 5.0
END DESCRIPTION:
XS GIS Cut Line= 3
      2264270.55     13308260.28      2263391.66     13307674.35
      2262957.60     13307696.06
#Sta/Elev= 30
  4263.0  124.84  4290.3  123.92  4302.5  122.82  4332.4  122.85  4347.4  121.92
  4368.4  121.85  4446.7  118.78  4506.7  117.33  4518.8  116.37  4542.7  116.46
  4548.7  115.91  4627.0  114.90  4635.9  115.16  4671.9  114.11  4708.0  113.90
  4744.0  112.38  4807.2  111.16  4924.3  109.78  4960.4  109.86  4963.4  109.18
  4966.1  108.68  4969.4  109.18  4996.4  110.09  5074.5  110.95  5176.7  114.93
  5343.3  118.86  5423.4  119.43  5463.4  120.27  5603.6  120.81  5753.9  120.38
#Mann=3,-1,0
  4263.0    0.05       0  4963.4    0.03       0  4969.4    0.05       0
Bank Sta=4963.4,4969.4
Exp/Cntr=0.3,0.1

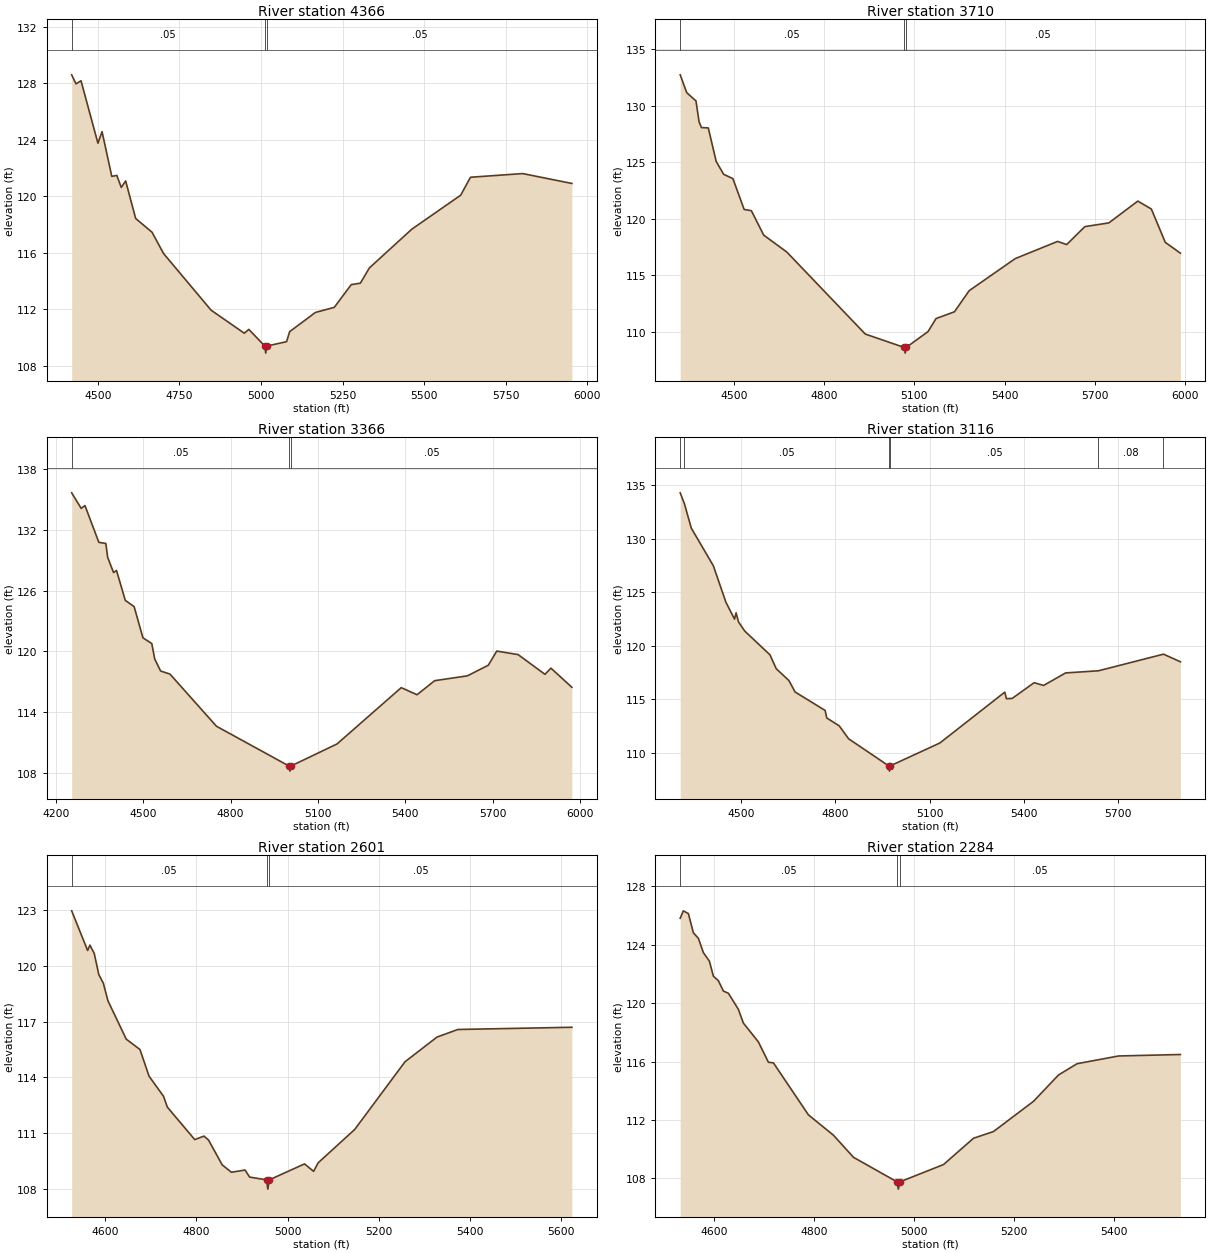
Type RM Length L Ch R = 1,4366,656,656,656
BEGIN DESCRIPTION:
UNT054 IN SPCR 4.0
END DESCRIPTION:
XS GIS Cut Line= 3
      2264476.76     13307837.14      2263728.03     13307370.53
      2263076.95     13307370.53
#Sta/Elev= 30
  4419.6  128.58  4432.9  127.94  4448.2  128.16  4500.1  123.74  4512.7  124.56
  4542.6  121.39  4558.0  121.46  4571.6  120.61  4585.1  121.07  4615.8  118.41
  4665.9  117.44  4701.3  115.93  4847.0  111.92  4948.7  110.29  4962.7  110.56
  5011.6  109.38  5014.4  108.88  5017.6  109.38  5078.3  109.69  5087.8  110.40
  5166.8  111.76  5224.6  112.12  5276.6  113.73  5304.5  113.83  5332.1  114.91
  5462.1  117.65  5612.1  120.06  5642.1  121.33  5802.1  121.59  5952.9  120.89
#Mann=3,-1,0
  4419.6    0.05       0  5011.6    0.03       0  5017.6    0.05       0
Bank Sta=5011.6,5017.6
Exp/Cntr=0.3,0.1

Type RM Length L Ch R = 1,3710,344,344,344
BEGIN DESCRIPTION:
UNT054 IN SPCR 3.0
END DESCRIPTION:
XS GIS Cut Line= 3
      2264889.01     13307077.56      2263945.04     13306871.40
      2263251.69     13306947.24
#Sta/Elev= 30
  4321.3  132.73  4343.0  131.15  4373.8  130.42  4384.0  128.58  4392.0  128.06
  4414.7  128.03  4441.0  125.06  4465.9  123.92  4496.6  123.54  4534.0  120.81
  4558.0  120.70  4599.0  118.54  4675.9  117.04  4936.8  109.78  5066.8  108.59
  5069.6  108.09  5072.8  108.59  5145.7  110.00  5172.2  111.15  5233.5  111.75
  5282.5  113.62  5435.7  116.46  5576.5  117.98  5606.7  117.70  5667.1  119.29
  5747.0  119.62  5843.3  121.55  5888.4  120.85  5934.6  117.90  5985.0  116.94
#Mann=3,-1,0
  4321.3    0.05       0  5066.8    0.03       0  5072.8    0.05       0
Bank Sta=5066.8,5072.8
Exp/Cntr=0.3,0.1

Type RM Length L Ch R = 1,3366,250,250,250
BEGIN DESCRIPTION:
UNT054 IN SPCR 2.0
END DESCRIPTION:
XS GIS Cut Line= 3
      2265030.12     13306697.79      2263934.19     13306545.88
      2263337.44     13306676.08
#Sta/Elev= 30
  4254.5  135.68  4287.2  134.14  4300.1  134.42  4347.8  130.78  4371.8  130.67
  4378.1  129.29  4398.3  127.79  4408.4  128.00  4438.5  125.04  4468.9  124.42
  4499.2  121.33  4529.5  120.77  4539.6  119.24  4559.8  118.05  4592.1  117.74
  4751.6  112.58  5001.0  108.64  5003.7  108.14  5007.0  108.64  5165.5  110.83
  5385.9  116.40  5440.1  115.70  5500.6  117.09  5613.2  117.57  5684.8  118.62
  5713.9  120.02  5787.2  119.67  5879.3  117.72  5899.8  118.33  5971.7  116.44
#Mann=3,-1,0
  4254.5    0.05       0  5001.0    0.03       0  5007.0    0.05       0
Bank Sta=5001,5007
Exp/Cntr=0.3,0.1

Type RM Length L Ch R = 1,3116,515,515,515
BEGIN DESCRIPTION:
Mapping XS 1efec577
END DESCRIPTION:
XS GIS Cut Line= 2
      2265033.10     13306325.74      2263442.77     13306381.30
#Sta/Elev= 30
  4306.0  134.27  4319.2  133.27  4341.4  130.97  4411.4  127.47  4451.5  124.06
  4478.8  122.49  4483.8  123.08  4491.5  122.23  4511.5  121.37  4591.6  119.16
  4611.6  117.86  4651.6  116.77  4671.6  115.69  4767.1  113.97  4772.1  113.27
  4811.7  112.54  4841.7  111.33  4968.8  108.81  4971.5  108.31  4974.8  108.81
  5131.9  110.93  5338.7  115.68  5343.7  115.07  5362.0  115.09  5432.1  116.56
  5462.1  116.30  5532.1  117.47  5636.5  117.67  5843.5  119.22  5897.3  118.51
#Mann=6,-1,0
  4306.0     0.1       0  4319.2    0.05       0  4968.8    0.04       0
  4974.8    0.05       0  5636.5    0.08       0  5843.5    0.05       0
Bank Sta=4968.8,4974.8
Exp/Cntr=0.3,0.1

Type RM Length L Ch R = 1,2601,317,317,317
BEGIN DESCRIPTION:
Mapping XS d19cec7e
END DESCRIPTION:
XS GIS Cut Line= 2
      2264867.12     13305809.66      2263772.60     13305877.22
#Sta/Elev= 30
  4526.4  122.98  4561.4  120.84  4566.4  121.13  4575.9  120.68  4585.9  119.54
  4595.9  119.07  4605.9  118.13  4646.0  116.06  4676.1  115.50  4696.1  114.06
  4727.7  112.98  4736.2  112.39  4796.3  110.64  4816.3  110.83  4826.4  110.62
  4856.4  109.28  4876.5  108.88  4906.5  109.00  4916.5  108.62  4953.6  108.47
  4956.4  107.97  4959.6  108.47  5036.8  109.33  5056.8  108.93  5066.8  109.39
  5147.0  111.19  5257.2  114.84  5327.3  116.17  5373.0  116.58  5623.0  116.70
#Mann=3,-1,0
  4526.4    0.05       0  4953.6   0.035       0  4959.6    0.05       0
Bank Sta=4953.6,4959.6
Exp/Cntr=0.3,0.1

Type RM Length L Ch R = 1,2284,571,571,571
BEGIN DESCRIPTION:
Mapping XS b96e5e0a
END DESCRIPTION:
XS GIS Cut Line= 2
      2264894.06     13305498.87      2263894.12     13305552.92
#Sta/Elev= 30
  4532.2  125.80  4538.5  126.31  4548.6  126.12  4558.6  124.80  4568.6  124.43
  4578.6  123.45  4590.6  122.87  4598.6  121.84  4608.6  121.53  4618.7  120.82
  4628.7  120.67  4648.7  119.57  4658.7  118.63  4688.8  117.34  4708.8  115.95
  4718.8  115.91  4788.9  112.35  4839.0  110.96  4879.0  109.45  4966.2  107.77
  4968.9  107.27  4972.2  107.77  5059.3  108.95  5119.4  110.75  5159.4  111.21
  5239.6  113.28  5289.6  115.08  5326.7  115.85  5409.8  116.38  5533.6  116.48
#Mann=3,-1,0
  4532.2    0.05       0  4966.2   0.035       0  4972.2    0.05       0
Bank Sta=4966.2,4972.2
Exp/Cntr=0.3,0.1

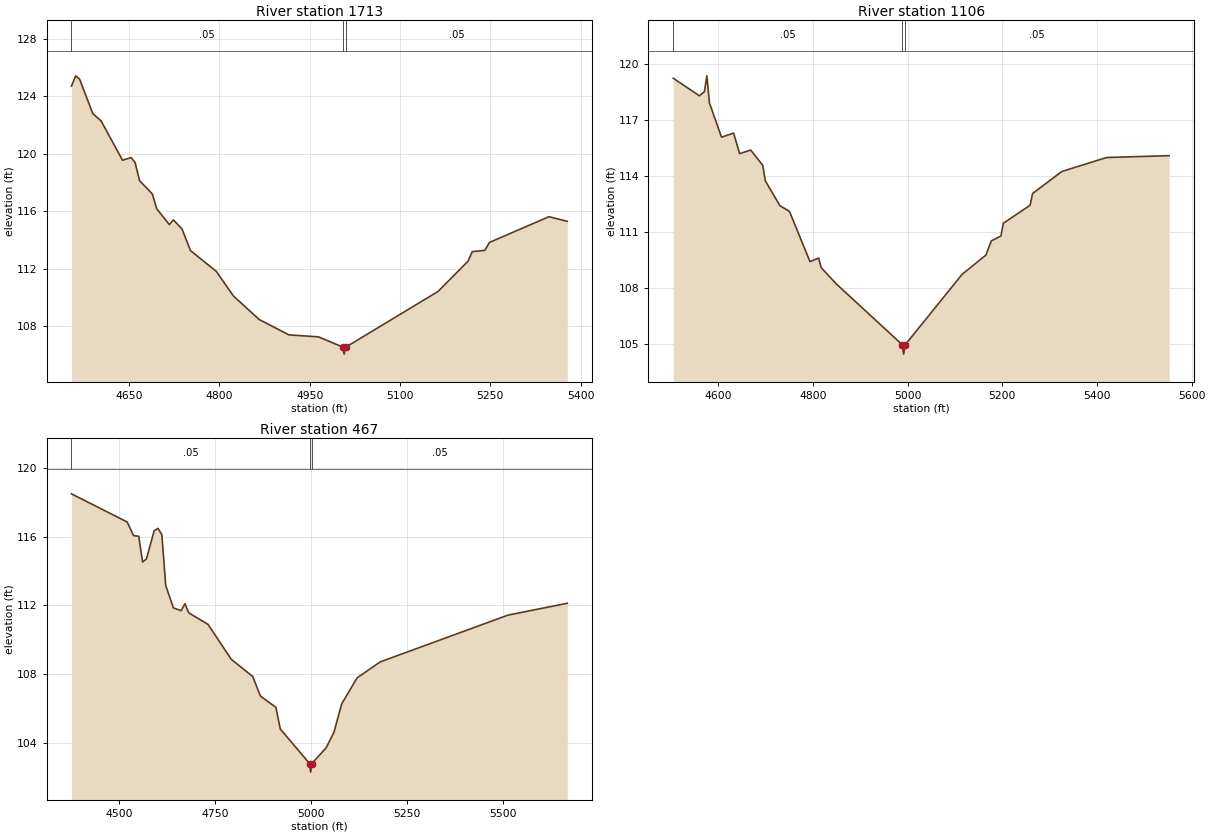
Type RM Length L Ch R = 1,1713,607,607,607
BEGIN DESCRIPTION:
Mapping XS 7283611c
END DESCRIPTION:
XS GIS Cut Line= 2
      2264704.91     13304674.58      2264083.34     13305215.07
#Sta/Elev= 30
  4554.3  124.71  4561.3  125.43  4567.9  125.19  4589.8  122.80  4603.6  122.29
  4639.1  119.56  4653.4  119.74  4660.0  119.40  4667.6  118.13  4688.5  117.22
  4696.1  116.17  4717.0  115.08  4723.6  115.41  4737.9  114.78  4752.1  113.27
  4794.9  111.83  4823.3  110.12  4866.1  108.48  4915.5  107.41  4964.8  107.27
  5004.6  106.57  5007.3  106.07  5010.6  106.57  5163.3  110.43  5213.2  112.54
  5220.2  113.20  5241.1  113.29  5248.7  113.84  5347.5  115.63  5378.0  115.31
#Mann=3,-1,0
  4554.3    0.05       0  5004.6    0.03       0  5010.6    0.05       0
Bank Sta=5004.6,5010.6
Exp/Cntr=0.3,0.1

Type RM Length L Ch R = 1,1106,639,639,639
BEGIN DESCRIPTION:
Mapping XS c49ee2d8
END DESCRIPTION:
XS GIS Cut Line= 2
      2264326.54     13303944.89      2263975.22     13304931.30
#Sta/Elev= 30
  4505.3  119.26  4560.5  118.32  4571.0  118.54  4576.3  119.39  4581.7  117.93
  4607.2  116.10  4632.7  116.32  4645.4  115.22  4668.8  115.41  4694.3  114.59
  4699.6  113.76  4730.5  112.43  4750.7  112.12  4794.0  109.43  4812.3  109.62
  4817.6  109.11  4848.5  108.26  4989.0  104.97  4991.7  104.47  4995.0  104.97
  5115.3  108.75  5165.5  109.78  5176.9  110.54  5197.1  110.80  5202.4  111.49
  5258.8  112.45  5264.1  113.08  5325.7  114.26  5420.3  115.01  5552.4  115.11
#Mann=3,-1,0
  4505.3    0.05       0  4989.0    0.03       0  4995.0    0.05       0
Bank Sta=4989,4995
Exp/Cntr=0.3,0.1

Type RM Length L Ch R = 1,467,0,0,0
BEGIN DESCRIPTION:
UNT054 IN SPCR 1.0
END DESCRIPTION:
XS GIS Cut Line= 3
      2264272.48     13303796.23      2263813.06     13303755.69
      2263704.95     13304580.03
#Sta/Elev= 30
  4376.1  118.49  4521.4  116.85  4538.0  116.06  4551.5  116.02  4561.6  114.52
  4571.6  114.70  4591.7  116.34  4601.7  116.48  4611.8  116.11  4621.8  113.16
  4641.9  111.85  4662.0  111.69  4672.0  112.09  4682.0  111.56  4732.2  110.89
  4792.5  108.86  4848.6  107.86  4868.7  106.72  4909.1  106.06  4920.5  104.80
  4996.9  102.79  4999.6  102.29  5002.9  102.79  5040.2  103.71  5060.4  104.61
  5080.5  106.26  5120.9  107.78  5181.4  108.71  5514.2  111.43  5668.7  112.12
#Mann=3,-1,0
  4376.1    0.05       0  4996.9    0.03       0  5002.9    0.05       0
Bank Sta=4996.9,5002.9
Exp/Cntr=0.3,0.1

Chan Stop Cuts=-1