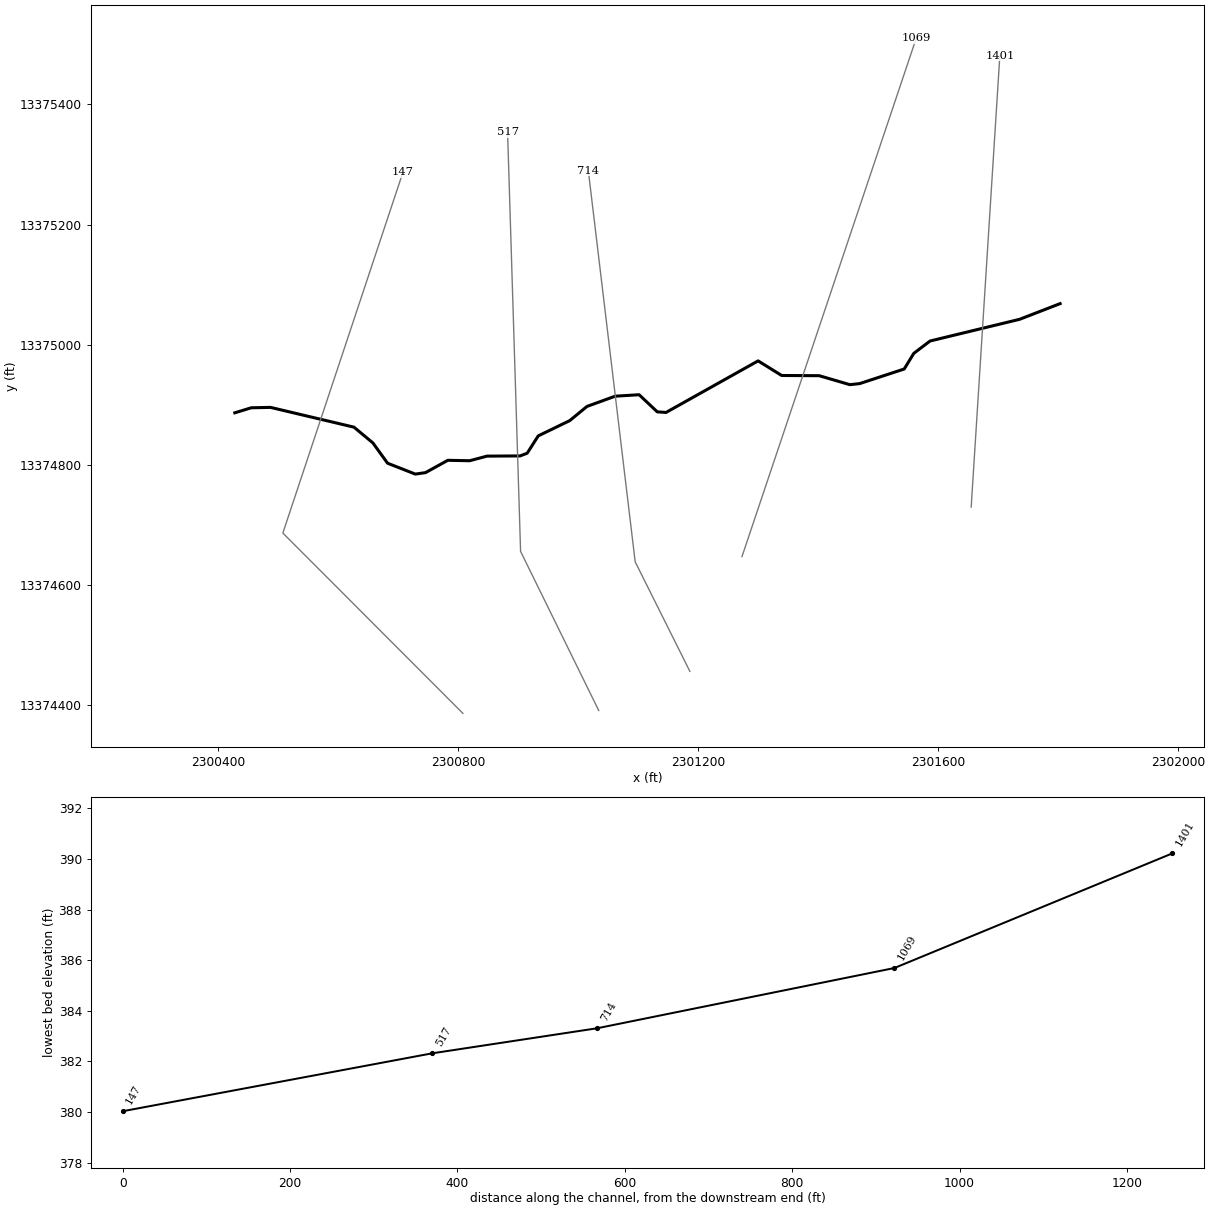
--- UNT0731 IN SPCR.prj (project) ---

Proj Title=UNT0731 IN SPCR Base Level Engineering
Current Plan=p01
Default Exp/Contr=0.3,0.1
English Units
Geom File=g01
Flow File=f01
Plan File=p01
Y Axis Title=Elevation
X Axis Title(PF)=Main Channel Distance
X Axis Title(XS)=Station
BEGIN DESCRIPTION:
UNT0731 IN SPCR
END DESCRIPTION:
DSS Export Rating Curves= 0
DSS Export Rating Curve Sorted= 0
DSS Export Volume Flow Curves= 0
DXF OffsetX= 0
DXF OffsetY= 0
DXF ScaleX= 1
DXF ScaleY= 10

--- UNT0731 IN SPCR.p01 (plan) ---

Plan Title=Multiple Run
Short Identifier=Multiple
Geom File=g01
Flow File=f01
Subcritical Flow
K Sum by GR= 0
Std Step Tol= 0.01
Critical Tol= 0.01
Num of Std Step Trials= 20
Max Error Tol= 0.3
Flow Tol Ratio= 0.001
Split Flow NTrial= 30
Split Flow Tol= 0.02
Split Flow Ratio= 0.02
Log Output Level= 0
Friction Slope Method= 1
Unsteady Friction Slope Method= 2
Unsteady Bridges Friction Slope Method= 1
Parabolic Critical Depth
Global Vel Dist=  1 , 1 , 1
Global Log Level= 0
CheckData=True
Encroach Param= -1, 0, 0, 0
BEGIN DESCRIPTION:
Multiple Run
END DESCRIPTION:

--- UNT0731 IN SPCR.f01 (steady flow) ---

Flow Title=Multiple
Number of Profiles=7
Profile Names=10-year,25-year,50-year,1pct_min,100-year,1pct_plu,500-year
River Rch & RM= UNT0731 IN SPCR,Reach-1,1401
     296     400     484     429     580     785     835
Boundary for River Rch & Prof#=UNT0731 IN SPCR,Reach-1,1
Up Type=0
Dn Type=3
Dn Slope=0.005
Boundary for River Rch & Prof#=UNT0731 IN SPCR,Reach-1,2
Up Type=0
Dn Type=3
Dn Slope=0.005
Boundary for River Rch & Prof#=UNT0731 IN SPCR,Reach-1,3
Up Type=0
Dn Type=3
Dn Slope=0.005
Boundary for River Rch & Prof#=UNT0731 IN SPCR,Reach-1,4
Up Type=0
Dn Type=3
Dn Slope=0.005
Boundary for River Rch & Prof#=UNT0731 IN SPCR,Reach-1,5
Up Type=0
Dn Type=3
Dn Slope=0.005
Boundary for River Rch & Prof#=UNT0731 IN SPCR,Reach-1,6
Up Type=0
Dn Type=3
Dn Slope=0.005
Boundary for River Rch & Prof#=UNT0731 IN SPCR,Reach-1,7
Up Type=0
Dn Type=3
Dn Slope=0.005

--- UNT0731 IN SPCR.g01 (geometry) ---

Geom Title=Existing Conditions
Program Version=4.10

River Reach=UNT0731 IN SPCR ,Reach-1
Reach XY= 30
      2301802.99     13375068.56      2301735.61     13375042.49
      2301586.28     13375006.34       2301559.2     13374985.84
      2301543.23     13374959.79      2301468.91     13374935.46
      2301452.59     13374933.72      2301401.53     13374948.65
      2301339.01     13374948.98      2301299.76     13374973.28
      2301146.27     13374887.46      2301131.69      13374888.5
      2301101.47     13374916.97      2301061.53     13374914.53
      2301014.64     13374897.51      2300985.82     13374873.88
      2300933.39     13374848.52      2300914.98     13374819.69
      2300903.18     13374815.17      2300847.96     13374814.81
      2300819.13     13374807.16      2300782.66     13374807.85
      2300745.51     13374787.35      2300728.49     13374784.92
      2300682.27     13374803.03      2300657.81     13374836.82
      2300626.28     13374863.02      2300487.25      13374895.9
      2300455.18     13374895.26      2300427.72     13374886.86

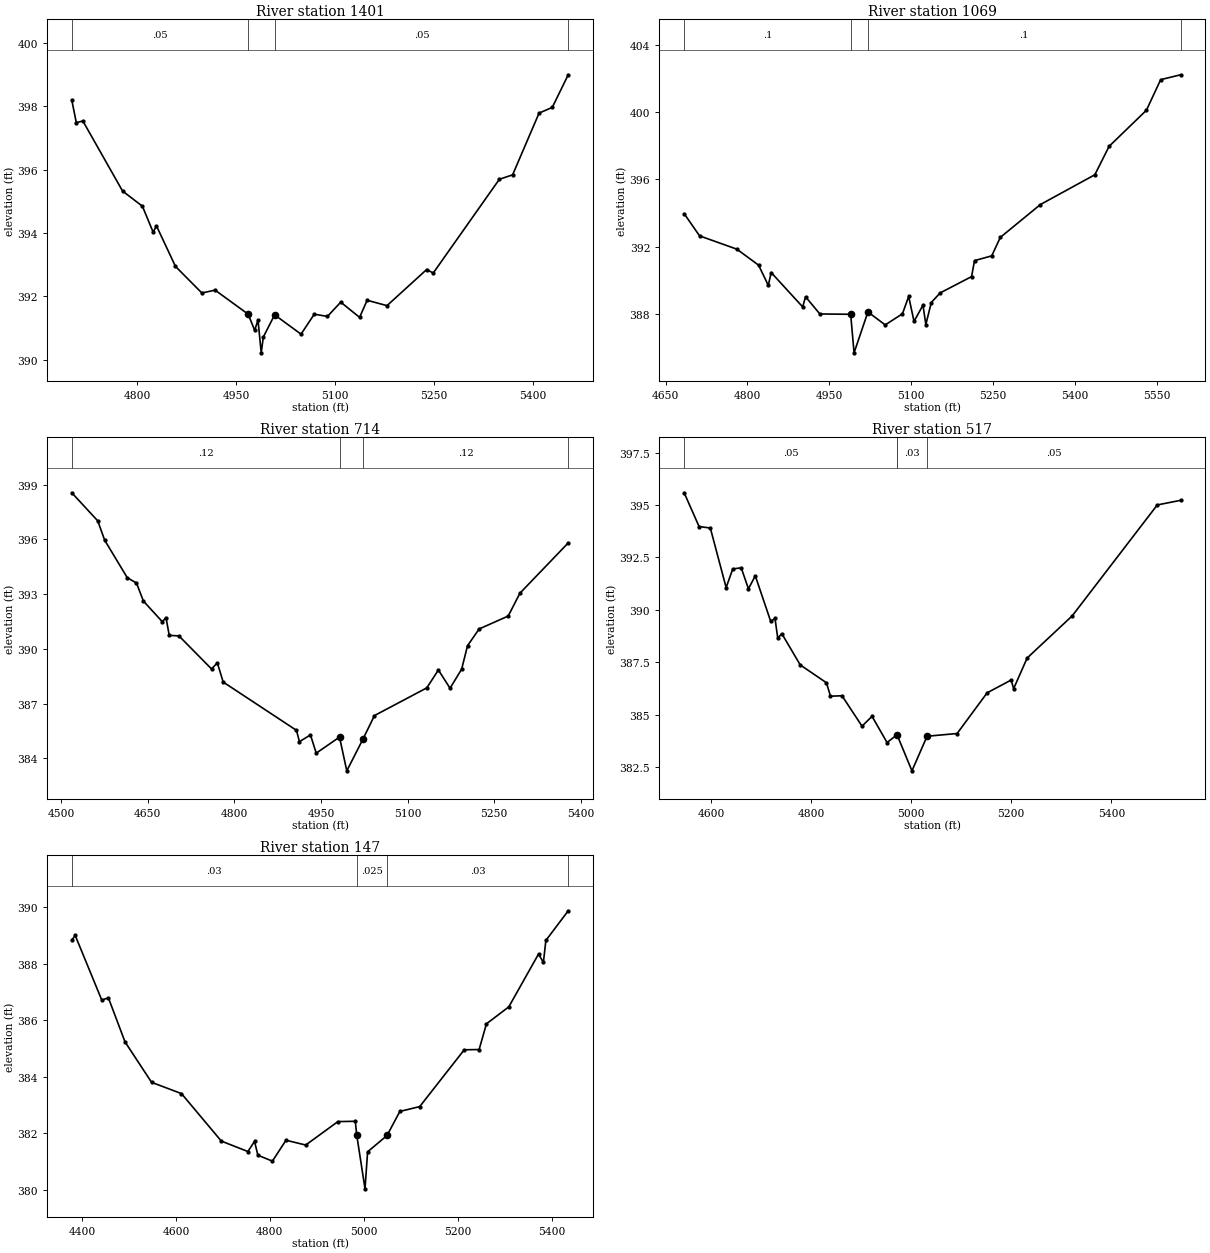
Type RM Length L Ch R = 1 ,1401    ,332,332,332
BEGIN DESCRIPTION:
UNT0731 IN SPCR 2.0
END DESCRIPTION:
XS GIS Cut Line= 2
      2301654.82     13374730.11      2301702.56       13375481.
#Sta/Elev= 30
  4701.1   398.2  4707.9  397.49  4717.9  397.54    4778  395.33  4808.1  394.85
  4824.4  394.03  4829.4  394.23  4858.2  392.95  4898.2  392.11  4918.3   392.2
  4968.4  391.44  4978.3  390.93  4983.3  391.26  4988.2  390.22  4991.4  390.72
  5008.5  391.42  5048.5  390.81  5068.6  391.44  5088.6  391.37  5108.7  391.82
  5137.3  391.34  5148.7  391.88  5178.8  391.71  5238.9  392.85  5248.9  392.74
  5349.1   395.7  5369.2  395.84  5409.3  397.79  5429.3  397.97  5453.5     399
#Mann= 4 ,-1 , 0
  4701.1     .05       0  4968.4     .07       0  5008.5     .05       0
  5453.5     .05       0
Bank Sta=4968.4,5008.5
XS Rating Curve= 0 ,0
Exp/Cntr=0.3,0.1

Type RM Length L Ch R = 1 ,1069    ,355,355,355
BEGIN DESCRIPTION:
Mapping XS 856d168f
END DESCRIPTION:
XS GIS Cut Line= 2
      2301272.87     13374647.62       2301563.2     13375509.96
#Sta/Elev= 30
  4684.1  393.96  4712.3  392.64  4780.6  391.85  4820.5   390.9  4838.3   389.7
  4843.6  390.46  4901.3  388.42  4906.6  389.02  4932.8     388  4989.3  387.98
  4995.5  385.69  5020.9  388.12  5052.6  387.35  5084.2  388.01  5095.6  389.04
  5105.4  387.56  5121.8  388.52  5127.1  387.37    5137  388.68  5153.3  389.25
  5210.9  390.22  5216.3  391.17  5247.8  391.45  5263.6  392.55    5337   394.5
  5436.8  396.27    5463  397.96  5531.3   400.1  5557.5  401.92    5594  402.21
#Mann= 4 ,-1 , 0
  4684.1      .1       0  4989.3     .07       0  5020.9      .1       0
    5594     .05       0
Bank Sta=4989.3,5020.9
XS Rating Curve= 0 ,0
Exp/Cntr=0.3,0.1

Type RM Length L Ch R = 1 ,714     ,197,197,197
BEGIN DESCRIPTION:
Mapping XS 171dd09a
END DESCRIPTION:
XS GIS Cut Line= 3
      2301186.05     13374456.69      2301094.92     13374638.95
      2301016.79     13375290.01
#Sta/Elev= 30
  4518.6  398.56  4563.5  397.02  4575.5  395.96  4614.7   393.9  4630.6  393.61
  4642.6  392.62  4675.3  391.49  4681.7  391.71  4687.3  390.74  4704.1  390.71
  4760.5   388.9  4770.6  389.23  4780.7  388.18  4907.6  385.53  4912.7  384.91
  4931.8  385.28  4941.8  384.28  4982.1  385.16  4994.7  383.31  5022.4  385.03
  5042.6  386.34  5133.2  387.86  5153.3  388.84  5173.5  387.84  5193.6  388.89
  5203.7  390.17  5223.8  391.09  5274.2   391.8  5294.4  393.05  5378.1  395.81
#Mann= 4 ,-1 , 0
  4518.6     .12       0  4982.1     .05       0  5022.4     .12       0
  5378.1     .05       0
Bank Sta=4982.1,5022.4
XS Rating Curve= 0 ,0
Exp/Cntr=0.3,0.1

Type RM Length L Ch R = 1 ,517     ,370,370,370
BEGIN DESCRIPTION:
Mapping XS ef073fb6
END DESCRIPTION:
XS GIS Cut Line= 3
      2301034.14     13374391.58      2300903.95     13374656.31
       2300882.3     13375353.46
#Sta/Elev= 30
    4546  395.58  4575.8  393.97  4598.3   393.9  4629.9  391.06  4643.2  391.95
  4660.1     392  4674.5     391  4688.2  391.62    4719  389.45  4727.6  389.59
  4733.1  388.65  4741.3  388.86  4778.1  387.37  4830.5  386.52  4838.5  385.88
  4861.6   385.9  4901.6  384.45  4921.6  384.92  4951.6  383.67  4971.6  384.04
  5001.4  382.32  5031.6  383.97  5091.7   384.1  5151.7  386.04  5199.7  386.65
  5204.7  386.24  5231.7   387.7  5321.8  389.71  5491.9     395  5538.5  395.22
#Mann= 4 ,-1 , 0
    4546     .05       0  4971.6      .1       0  4971.6     .03       0
  5031.6     .05       0
Bank Sta=4971.6,5031.6
XS Rating Curve= 0 ,0
Exp/Cntr=0.3,0.1

Type RM Length L Ch R = 1 ,147     ,0,0,0
BEGIN DESCRIPTION:
UNT0731 IN SPCR 1.0
END DESCRIPTION:
XS GIS Cut Line= 3
      2300807.84     13374386.79      2300507.81     13374686.82
      2300707.82     13375286.85
#Sta/Elev= 30
  4378.4  388.83  4385.6     389  4442.2  386.71  4456.3  386.79  4491.7  385.23
  4548.2   383.8  4611.9   383.4  4696.7  381.72  4753.3  381.35  4767.4  381.71
  4774.5  381.22  4805.4  381.01  4834.4  381.75  4876.4  381.58  4944.9  382.41
  4981.9  382.42 4985.01  381.93  5002.6  380.03  5008.1  381.34 5049.56  381.92
  5076.8  382.77    5119  382.94  5213.8  384.95  5245.5  384.96  5261.1  385.87
  5308.7  386.47    5372  388.34  5382.3  388.04  5387.6  388.82  5435.2  389.87
#Mann= 4 ,-1 , 0
  4378.4     .03       0 4985.01    .025       0 5049.56     .03       0
  5435.2      .1       0
Bank Sta=4985.01,5049.56
XS Rating Curve= 0 ,0
Exp/Cntr=0.3,0.1

Chan Stop Cuts=-1
Use User Specified Reach Order=0
Composite Channel Slope=5