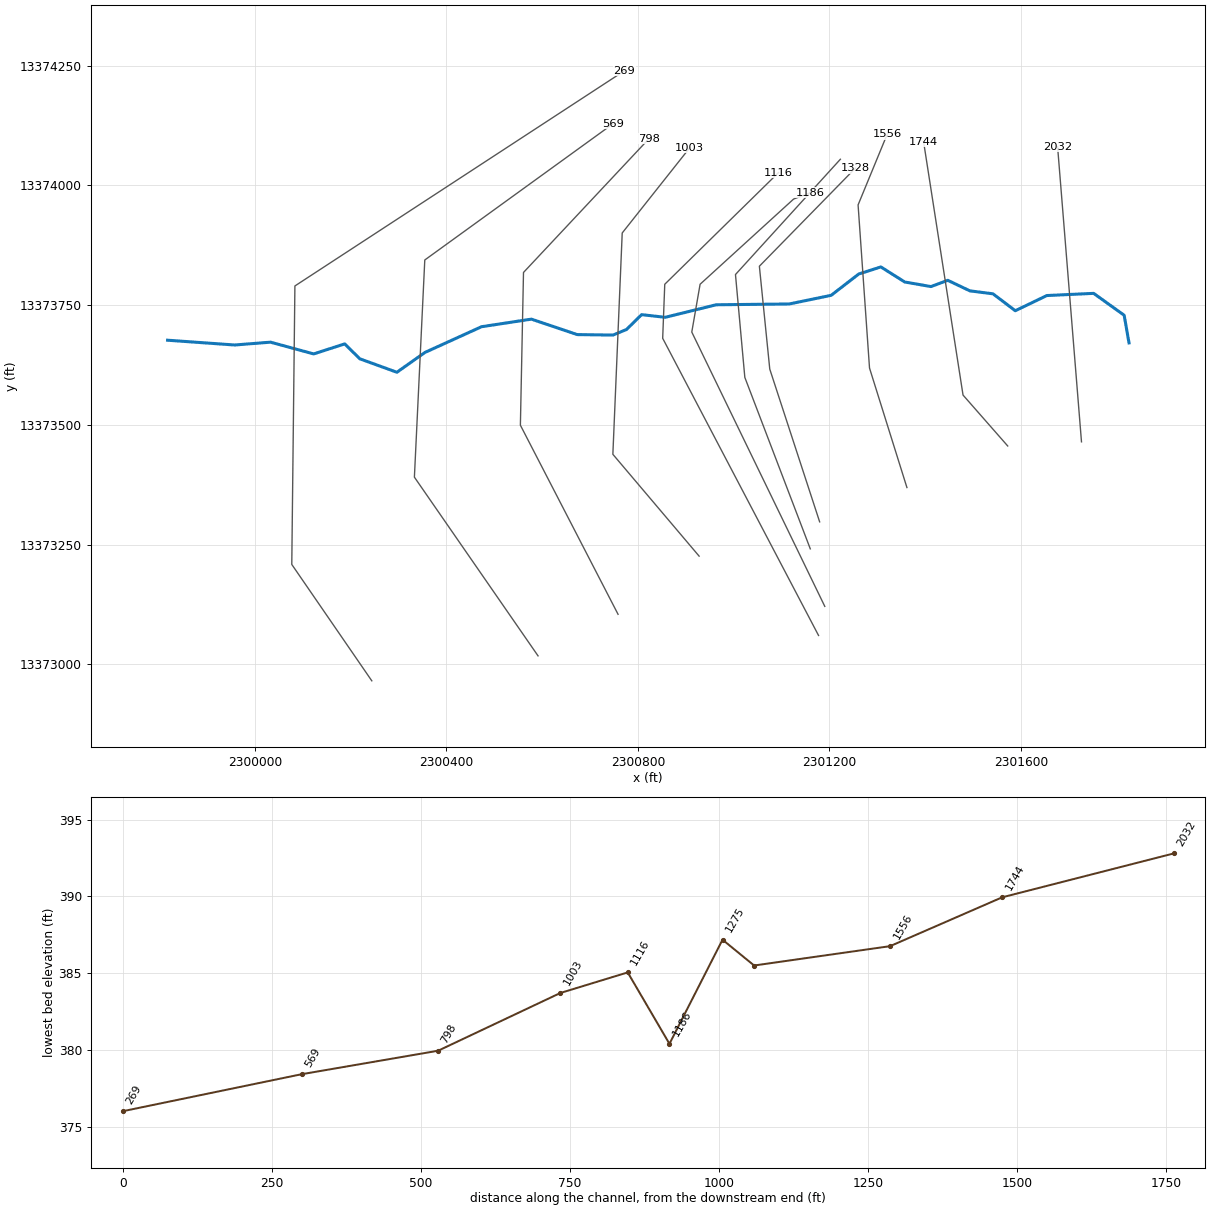
--- UNT0733 IN SPCR.prj (project) ---

Proj Title=UNT0733 IN SPCR Base Level Engineering
Current Plan=p01
Default Exp/Contr=0.3,0.1
English Units
Geom File=g01
Flow File=f01
Plan File=p01
BEGIN DESCRIPTION:
UNT0733 IN SPCR
END DESCRIPTION:

--- UNT0733 IN SPCR.p01 (plan) ---

Plan Title=Multiple Run
Short Identifier=Multiple
Geom File=g01
Flow File=f01
Subcritical Flow
K Sum by GR= 0
Std Step Tol= 0.01
Critical Tol= 0.01
Num of Std Step Trials= 20
Max Error Tol= 0.3
Flow Tol Ratio= 0.001
Split Flow NTrial= 30
Split Flow Tol= 0.02
Split Flow Ratio= 0.02
Log Output Level= 0
Friction Slope Method= 1
Unsteady Friction Slope Method= 2
Unsteady Bridges Friction Slope Method= 1
Parabolic Critical Depth
Global Vel Dist=  1 , 1 , 1
Global Log Level= 0
CheckData=True
Encroach Param= -1, 0, 0, 0
BEGIN DESCRIPTION:
Multiple Run
END DESCRIPTION:

--- UNT0733 IN SPCR.f01 (steady flow) ---

Flow Title=Multiple
Number of Profiles=7
Profile Names=10-year,25-year,50-year,1pct_min,100-year,1pct_plu,500-year
River Rch & RM= UNT0733 IN SPCR,Reach-1,2032
     329     450     548     490     663     896     970
Boundary for River Rch & Prof#=UNT0733 IN SPCR,Reach-1,1
Up Type=0
Dn Type=3
Dn Slope=0.005
Boundary for River Rch & Prof#=UNT0733 IN SPCR,Reach-1,2
Up Type=0
Dn Type=3
Dn Slope=0.005
Boundary for River Rch & Prof#=UNT0733 IN SPCR,Reach-1,3
Up Type=0
Dn Type=3
Dn Slope=0.005
Boundary for River Rch & Prof#=UNT0733 IN SPCR,Reach-1,4
Up Type=0
Dn Type=3
Dn Slope=0.005
Boundary for River Rch & Prof#=UNT0733 IN SPCR,Reach-1,5
Up Type=0
Dn Type=3
Dn Slope=0.005
Boundary for River Rch & Prof#=UNT0733 IN SPCR,Reach-1,6
Up Type=0
Dn Type=3
Dn Slope=0.005
Boundary for River Rch & Prof#=UNT0733 IN SPCR,Reach-1,7
Up Type=0
Dn Type=3
Dn Slope=0.005

--- UNT0733 IN SPCR.g01 (geometry) ---

Geom Title=Existing Conditions

River Reach=UNT0733 IN SPCR,Reach-1
Reach XY= 30
      2301825.66     13373671.22      2301815.54     13373729.02
      2301751.80     13373774.69      2301654.08     13373770.14
      2301588.20     13373738.41      2301541.52     13373773.77
      2301493.47     13373779.88      2301447.21     13373801.91
      2301412.03     13373788.89      2301357.29     13373798.42
      2301307.40     13373829.89      2301261.24     13373815.10
      2301203.65     13373770.61      2301116.13     13373752.53
      2300963.49     13373750.84      2300857.05     13373724.68
      2300807.73     13373730.23      2300776.29     13373699.32
      2300748.05     13373687.58      2300673.26     13373688.58
      2300577.63     13373720.84      2300473.50     13373705.04
      2300355.18     13373651.27      2300296.65     13373609.91
      2300219.29     13373637.98      2300187.62     13373669.12
      2300122.84     13373648.21      2300032.73     13373672.75
      2299957.83     13373666.85      2299817.72     13373676.85

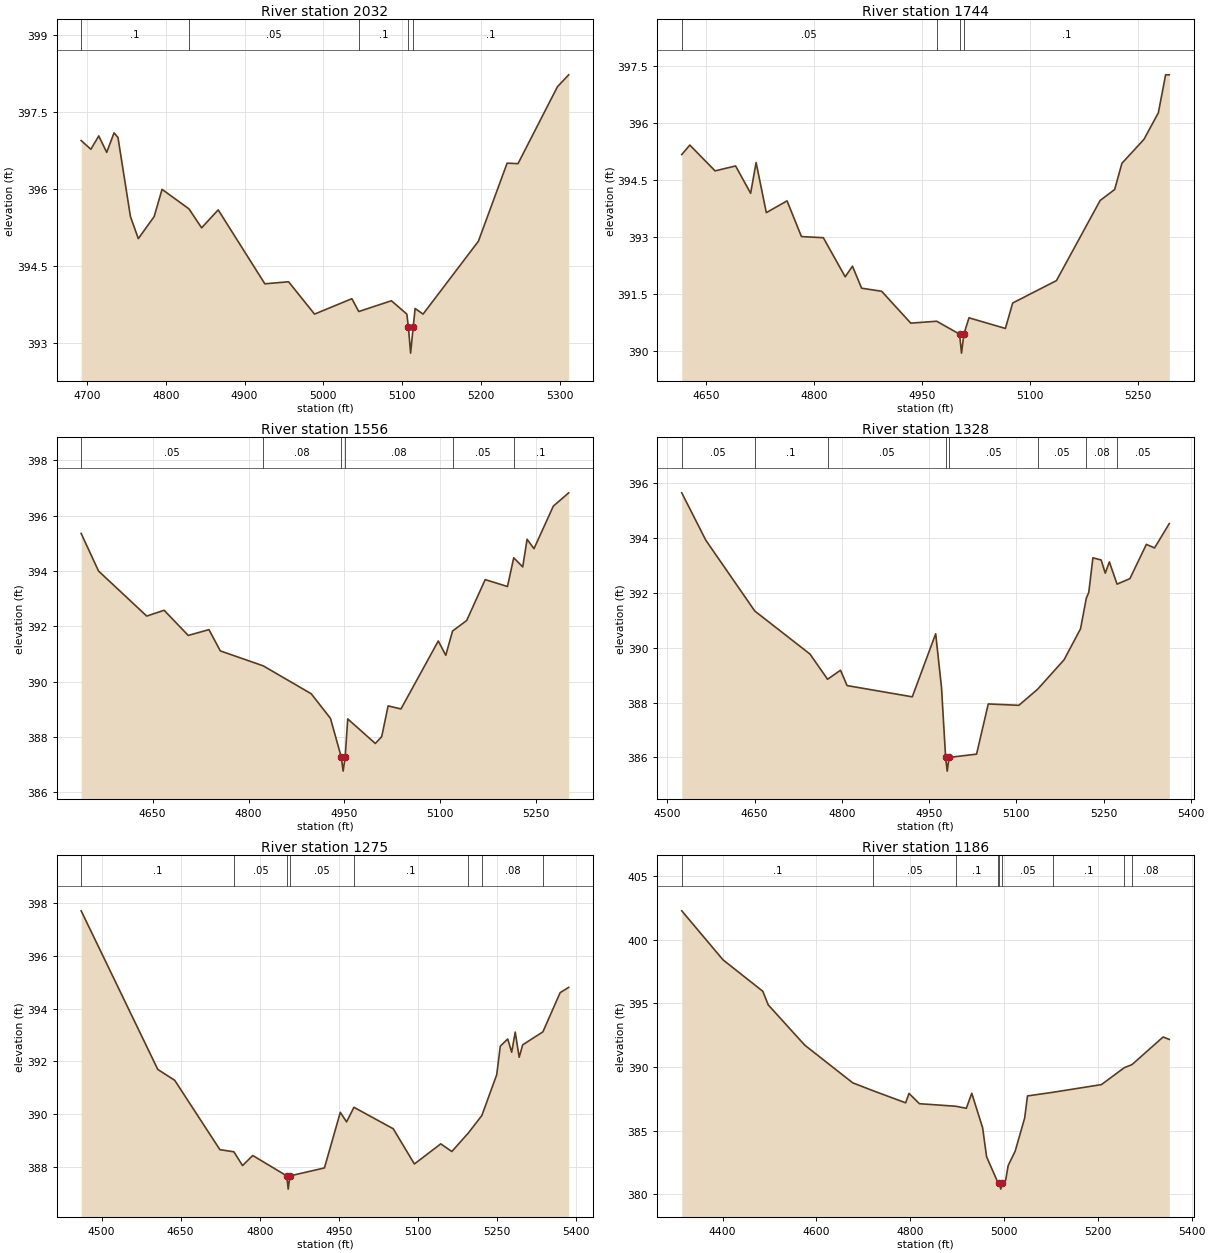
Type RM Length L Ch R = 1,2032,288,288,288
BEGIN DESCRIPTION:
UNT0733 IN SPCR 3.0
END DESCRIPTION:
XS GIS Cut Line= 2
      2301726.43     13373464.60      2301676.51     13374080.98
#Sta/Elev= 30
  4692.7  396.94  4705.0  396.77  4715.0  397.03  4725.1  396.71  4734.4  397.09
  4739.4  397.00  4755.2  395.46  4765.2  395.03  4785.3  395.46  4795.3  395.99
  4829.4  395.61  4845.5  395.24  4866.5  395.59  4925.7  394.15  4955.8  394.19
  4988.7  393.56  5036.1  393.86  5044.8  393.61  5086.2  393.82  5105.8  393.56
  5107.8  393.30  5110.6  392.80  5113.8  393.30  5116.3  393.67  5126.4  393.56
  5196.6  394.98  5233.0  396.50  5246.8  396.49  5296.9  397.99  5311.1  398.22
#Mann=5,-1,0
  4692.7     0.1       0  4829.4    0.05       0  5044.8     0.1       0
  5107.8    0.03       0  5113.8     0.1       0
Bank Sta=5107.8,5113.8
Exp/Cntr=0.3,0.1

Type RM Length L Ch R = 1,1744,188,188,188
BEGIN DESCRIPTION:
Mapping XS 8f78590d
END DESCRIPTION:
XS GIS Cut Line= 3
      2301572.34     13373455.94      2301479.03     13373562.27
      2301396.56     13374091.82
#Sta/Elev= 30
  4616.1  395.17  4627.3  395.42  4662.4  394.74  4690.9  394.87  4711.8  394.15
  4719.4  394.96  4733.6  393.64  4762.4  393.95  4782.4  393.01  4812.8  392.98
  4843.2  391.95  4853.3  392.23  4866.0  391.65  4893.8  391.57  4934.3  390.73
  4970.3  390.78  5002.1  390.44  5004.8  389.94  5008.1  390.44  5015.2  390.87
  5065.8  390.59  5075.9  391.26  5136.7  391.85  5197.4  393.96  5217.6  394.25
  5227.7  394.94  5258.3  395.57  5278.3  396.27  5288.4  397.27  5293.5  397.27
#Mann=4,-1,0
  4616.1    0.05       0  4970.3     0.1       0  5002.1    0.07       0
  5008.1     0.1       0
Bank Sta=5002.1,5008.1
Exp/Cntr=0.3,0.1

Type RM Length L Ch R = 1,1556,228,228,228
BEGIN DESCRIPTION:
Mapping XS a00983ec
END DESCRIPTION:
XS GIS Cut Line= 4
      2301361.85     13373369.12      2301283.72     13373618.70
      2301259.85     13373959.41      2301320.63     13374107.02
#Sta/Elev= 30
  4538.2  395.36  4565.4  394.00  4640.8  392.37  4668.0  392.58  4705.7  391.67
  4738.1  391.88  4755.9  391.11  4823.0  390.57  4898.1  389.56  4928.2  388.67
  4945.2  387.26  4948.0  386.76  4951.2  387.26  4955.2  388.65  4998.4  387.76
  5008.4  388.01  5018.4  389.12  5038.5  389.01  5096.9  391.47  5108.6  390.95
  5119.2  391.83  5141.3  392.21  5170.3  393.69  5205.1  393.44  5214.9  394.48
  5229.0  394.15  5235.8  395.15  5246.6  394.81  5276.9  396.35  5300.9  396.83
#Mann=6,-1,0
  4538.2    0.05       0  4823.0    0.08       0  4945.2    0.07       0
  4951.2    0.08       0  5119.2    0.05       0  5214.9     0.1       0
Bank Sta=4945.2,4951.2
Exp/Cntr=0.3,0.1

Type RM Length L Ch R = 1,1328,53,53,53
BEGIN DESCRIPTION:
UNT0733 IN SPCR 2.0
END DESCRIPTION:
XS GIS Cut Line= 4
      2301179.57     13373297.47      2301075.39     13373616.53
      2301053.69     13373831.37      2301254.13     13374036.12
#Sta/Elev= 30
  4524.7  395.65  4566.1  393.92  4650.2  391.34  4745.1  389.77  4775.4  388.85
  4797.6  389.18  4808.9  388.62  4921.0  388.21  4961.2  390.51  4971.2  388.56
  4978.3  386.00  4981.0  385.50  4984.3  386.00  5031.5  386.12  5051.6  387.95
  5104.2  387.90  5136.6  388.49  5181.9  389.56  5210.2  390.69  5220.2  391.81
  5224.4  392.02  5231.5  393.28  5245.7  393.20  5252.7  392.72  5259.8  393.13
  5273.0  392.32  5295.1  392.52  5323.4  393.77  5337.5  393.64  5362.8  394.53
#Mann=8,-1,0
  4524.7    0.05       0  4650.2     0.1       0  4775.4    0.05       0
  4978.3    0.07       0  4984.3    0.05       0  5136.6    0.05       0
  5220.2    0.08       0  5273.0    0.05       0
Bank Sta=4978.3,4984.3
Exp/Cntr=0.3,0.1

Type RM Length L Ch R = 1,1275,89,89,89
BEGIN DESCRIPTION:
Mapping XS f13cbdff
END DESCRIPTION:
XS GIS Cut Line= 4
      2301160.02     13373241.10      2301023.31     13373599.17
      2301003.77     13373814.01      2301222.83     13374054.76
#Sta/Elev= 30
  4461.3  397.69  4606.6  391.70  4638.7  391.29  4724.4  388.67  4750.9  388.59
  4767.3  388.07  4786.7  388.45  4851.2  387.68  4853.9  387.18  4857.2  387.68
  4922.6  387.98  4952.7  390.08  4964.6  389.72  4978.6  390.27  5053.1  389.46
  5093.2  388.13  5143.2  388.89  5164.2  388.60  5195.5  389.30  5221.1  389.96
  5249.3  391.50  5256.1  392.58  5270.2  392.85  5277.7  392.35  5284.4  393.11
  5291.9  392.16  5298.6  392.63  5336.9  393.12  5369.6  394.60  5385.8  394.80
#Mann=8,-1,0
  4461.3     0.1       0  4750.9    0.05       0  4851.2    0.07       0
  4857.2    0.05       0  4978.6     0.1       0  5195.5    0.05       0
  5221.1    0.08       0  5336.9    0.05       0
Bank Sta=4851.2,4857.2
Exp/Cntr=0.3,0.1

Type RM Length L Ch R = 1,1186,70,70,70
BEGIN DESCRIPTION:
Mapping XS 0c25ed8c
END DESCRIPTION:
XS GIS Cut Line= 5
      2301190.30     13373120.94      2300912.52     13373693.87
      2300929.88     13373793.69      2301125.19     13373971.65
      2301159.96     13373984.68
#Sta/Elev= 30
  4312.9  402.26  4400.9  398.41  4485.7  395.94  4497.3  394.87  4575.1  391.71
  4677.4  388.75  4720.7  388.13  4790.2  387.18  4797.4  387.92  4819.6  387.11
  4897.0  386.91  4919.6  386.75  4931.2  387.93  4954.3  385.22  4962.8  382.94
  4986.1  380.99  4990.3  380.90  4993.0  380.40  4996.3  380.90  5003.4  381.09
  5008.8  382.25  5023.7  383.38  5044.0  385.99  5050.0  387.72  5104.9  388.01
  5207.6  388.61  5256.4  389.94  5272.8  390.18  5339.1  392.35  5352.3  392.16
#Mann=9,-1,0
  4312.9     0.1       0  4720.7    0.05       0  4897.0     0.1       0
  4986.1    0.05       0  4990.3    0.03       0  4996.3    0.05       0
  5104.9     0.1       0  5256.4    0.05       0  5272.8    0.08       0
Bank Sta=4990.3,4996.3
Exp/Cntr=0.3,0.1

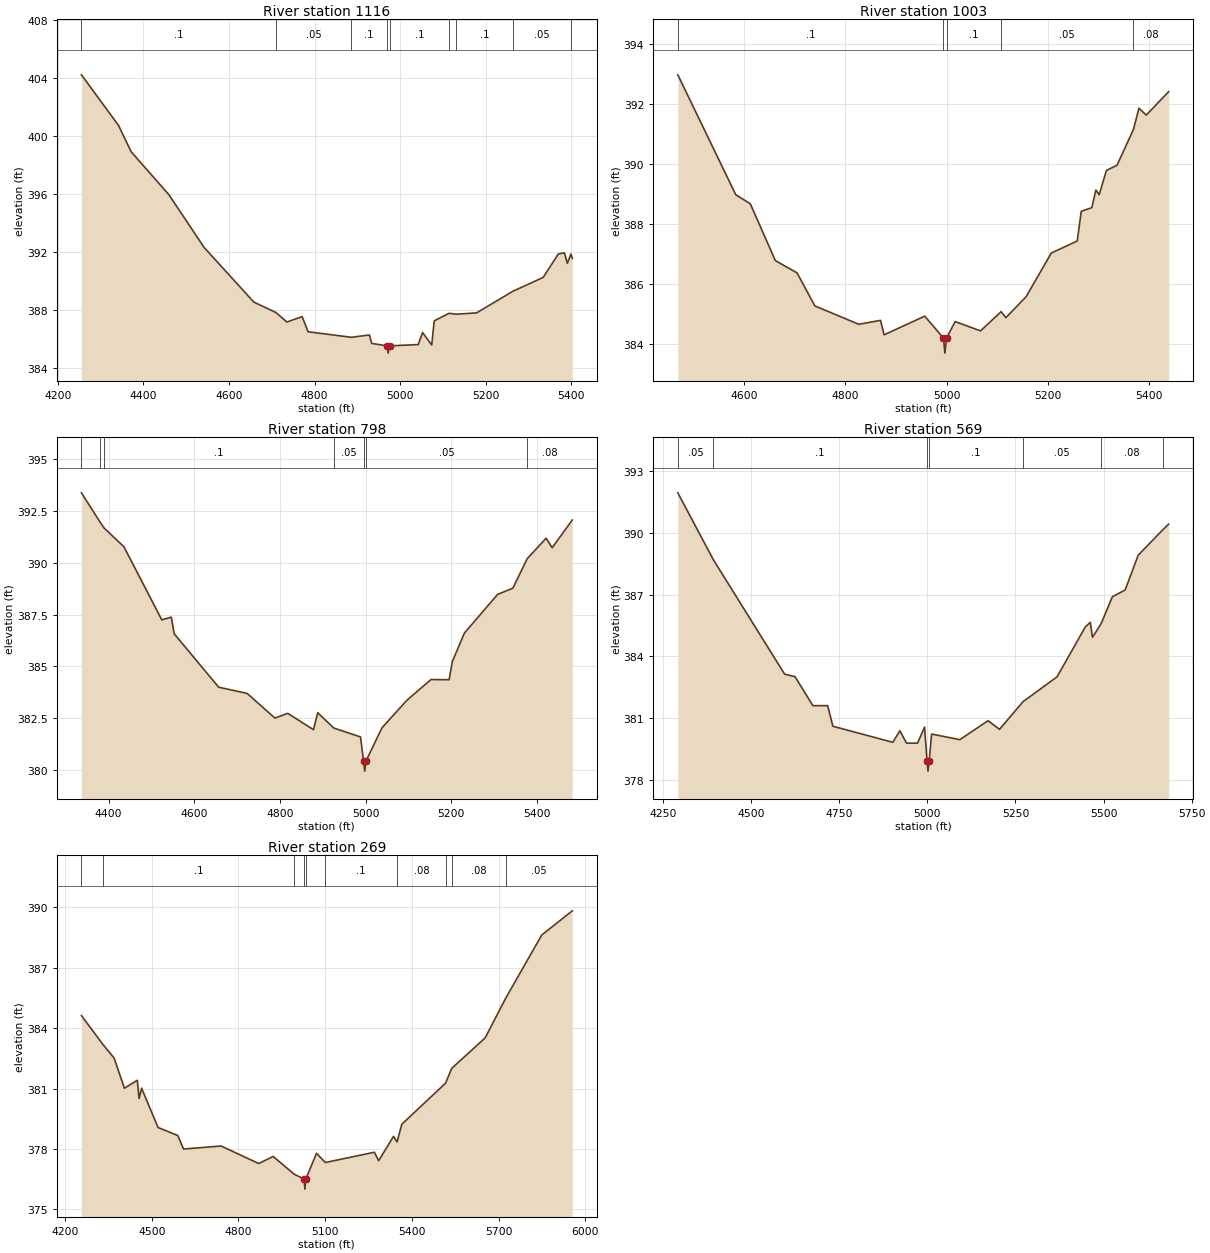
Type RM Length L Ch R = 1,1116,113,113,113
BEGIN DESCRIPTION:
Mapping XS 64eb93c3
END DESCRIPTION:
XS GIS Cut Line= 4
      2301177.27     13373060.20      2300851.75     13373680.85
      2300856.09     13373793.69      2301093.74     13374027.02
#Sta/Elev= 30
  4255.3  404.20  4341.9  400.72  4371.4  398.91  4459.6  395.95  4542.2  392.31
  4658.2  388.56  4710.1  387.84  4735.1  387.19  4771.0  387.56  4784.8  386.52
  4885.9  386.14  4928.0  386.30  4933.6  385.72  4969.2  385.55  4971.9  385.05
  4975.2  385.55  5042.2  385.64  5052.2  386.47  5073.7  385.61  5079.5  387.27
  5114.1  387.79  5131.3  387.73  5178.5  387.82  5262.9  389.30  5334.1  390.26
  5369.4  391.87  5383.6  391.95  5390.7  391.23  5398.9  391.87  5402.1  391.56
#Mann=9,-1,0
  4255.3     0.1       0  4710.1    0.05       0  4885.9     0.1       0
  4969.2    0.07       0  4975.2     0.1       0  5114.1    0.05       0
  5131.3     0.1       0  5262.9    0.05       0  5398.9    0.08       0
Bank Sta=4969.2,4975.2
Exp/Cntr=0.3,0.1

Type RM Length L Ch R = 1,1003,205,205,205
BEGIN DESCRIPTION:
Mapping XS 5a8f0c93
END DESCRIPTION:
XS GIS Cut Line= 4
      2300927.84     13373225.88      2300747.70     13373438.58
      2300767.23     13373900.82      2300908.31     13374078.80
#Sta/Elev= 30
  4469.5  392.97  4583.9  388.98  4612.5  388.68  4661.9  386.79  4704.8  386.38
  4739.9  385.28  4826.6  384.67  4869.4  384.80  4876.6  384.32  4956.7  384.94
  4993.7  384.21  4996.5  383.71  4999.7  384.21  5016.7  384.76  5066.8  384.45
  5107.5  385.09  5116.8  384.89  5156.9  385.59  5206.4  387.04  5257.6  387.44
  5265.6  388.43  5286.4  388.55  5294.5  389.14  5300.9  388.98  5315.3  389.79
  5336.1  389.96  5368.5  391.15  5379.4  391.86  5393.8  391.63  5438.0  392.41
#Mann=5,-1,0
  4469.5     0.1       0  4993.7    0.07       0  4999.7     0.1       0
  5107.5    0.05       0  5368.5    0.08       0
Bank Sta=4993.7,4999.7
Exp/Cntr=0.3,0.1

Type RM Length L Ch R = 1,798,229,229,229
BEGIN DESCRIPTION:
Mapping XS 9123311d
END DESCRIPTION:
XS GIS Cut Line= 4
      2300758.53     13373104.42      2300554.56     13373499.34
      2300561.07     13373818.35      2300823.18     13374097.80
#Sta/Elev= 30
  4336.4  393.38  4380.7  391.94  4389.4  391.68  4435.5  390.78  4524.1  387.25
  4546.3  387.38  4553.0  386.58  4657.0  384.00  4723.5  383.70  4788.4  382.51
  4818.4  382.74  4878.4  381.95  4888.4  382.77  4925.9  382.03  4988.4  381.60
  4995.4  380.45  4998.2  379.95  5001.4  380.45  5038.5  382.04  5096.7  383.37
  5152.9  384.37  5195.4  384.36  5202.7  385.23  5231.0  386.61  5308.7  388.48
  5344.4  388.78  5377.7  390.20  5422.0  391.19  5436.2  390.73  5483.1  392.07
#Mann=7,-1,0
  4336.4     0.1       0  4380.7    0.05       0  4389.4     0.1       0
  4925.9    0.05       0  4995.4    0.03       0  5001.4    0.05       0
  5377.7    0.08       0
Bank Sta=4995.4,5001.4
Exp/Cntr=0.3,0.1

Type RM Length L Ch R = 1,569,300,300,300
BEGIN DESCRIPTION:
Mapping XS ba8fdb41
END DESCRIPTION:
XS GIS Cut Line= 4
      2300591.44     13373017.59      2300333.20     13373390.83
      2300354.90     13373844.39      2300747.68     13374128.66
#Sta/Elev= 30
  4291.9  391.94  4392.4  388.70  4595.0  383.13  4624.5  383.01  4675.2  381.60
  4717.1  381.60  4731.9  380.60  4902.0  379.82  4922.0  380.38  4941.0  379.78
  4972.1  379.78  4992.1  380.56  4999.1  378.92  5001.8  378.42  5005.1  378.92
  5012.1  380.22  5092.2  379.95  5172.3  380.87  5204.7  380.45  5271.3  381.79
  5368.0  383.00  5447.7  385.41  5462.4  385.65  5468.6  384.92  5493.0  385.58
  5525.0  386.89  5561.3  387.22  5598.3  388.91  5668.5  390.15  5684.7  390.42
#Mann=7,-1,0
  4291.9    0.05       0  4392.4     0.1       0  4999.1    0.07       0
  5005.1     0.1       0  5271.3    0.05       0  5493.0    0.08       0
  5668.5    0.05       0
Bank Sta=4999.1,5005.1
Exp/Cntr=0.3,0.1

Type RM Length L Ch R = 1,269,0,0,0
BEGIN DESCRIPTION:
UNT0733 IN SPCR 1.0
END DESCRIPTION:
XS GIS Cut Line= 4
      2300244.24     13372965.46      2300077.12     13373208.54
      2300083.64     13373790.14      2300771.54     13374239.34
#Sta/Elev= 30
  4256.7  384.62  4331.5  383.18  4369.5  382.52  4405.3  381.02  4450.0  381.41
  4456.1  380.51  4464.7  381.02  4521.7  379.07  4590.0  378.67  4610.0  378.00
  4740.0  378.15  4870.0  377.28  4920.0  377.63  4992.9  376.75  5027.0  376.51
  5029.8  376.01  5033.0  376.51  5070.0  377.79  5100.5  377.33  5270.0  377.84
  5285.1  377.42  5336.5  378.63  5348.6  378.35  5365.1  379.23  5516.6  381.27
  5537.6  382.00  5653.2  383.51  5726.7  385.54  5849.3  388.62  5954.9  389.82
#Mann=10,-1,0
  4256.7    0.05       0  4331.5     0.1       0  4992.9    0.08       0
  5027.0    0.07       0  5033.0    0.08       0  5100.5     0.1       0
  5348.6    0.08       0  5516.6    0.05       0  5537.6    0.08       0
  5726.7    0.05       0
Bank Sta=5027,5033
Exp/Cntr=0.3,0.1

Chan Stop Cuts=-1