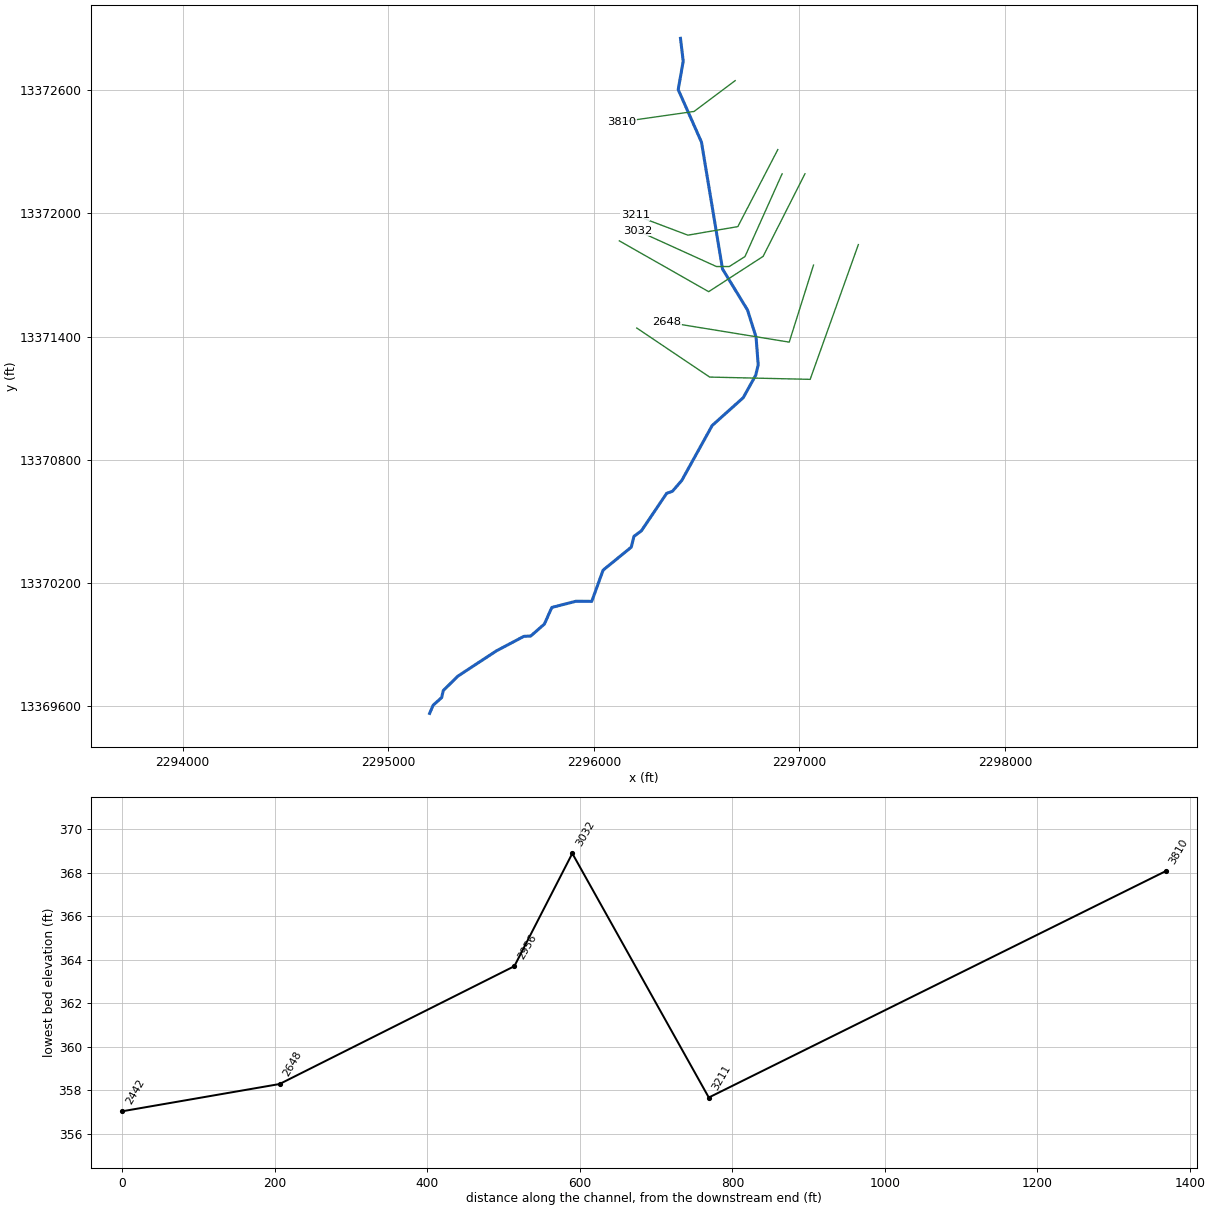
--- UNT0736 IN SPCR.prj (project) ---

Proj Title=UNT0736 IN SPCR Base Level Engineering
Current Plan=p01
Default Exp/Contr=0.3,0.1
English Units
Geom File=g01
Flow File=f01
Plan File=p01
Y Axis Title=Elevation
X Axis Title(PF)=Main Channel Distance
X Axis Title(XS)=Station
BEGIN DESCRIPTION:
UNT0736 IN SPCR
END DESCRIPTION:
DSS Export Rating Curves= 0
DSS Export Rating Curve Sorted= 0
DSS Export Volume Flow Curves= 0
DXF OffsetX= 0
DXF OffsetY= 0
DXF ScaleX= 1
DXF ScaleY= 10

--- UNT0736 IN SPCR.p01 (plan) ---

Plan Title=Multiple Run
Short Identifier=Multiple
Geom File=g01
Flow File=f01
Subcritical Flow
K Sum by GR= 0
Std Step Tol= 0.01
Critical Tol= 0.01
Num of Std Step Trials= 20
Max Error Tol= 0.3
Flow Tol Ratio= 0.001
Split Flow NTrial= 30
Split Flow Tol= 0.02
Split Flow Ratio= 0.02
Log Output Level= 0
Friction Slope Method= 1
Unsteady Friction Slope Method= 2
Unsteady Bridges Friction Slope Method= 1
Parabolic Critical Depth
Global Vel Dist=  1 , 1 , 1
Global Log Level= 0
CheckData=True
Encroach Param= -1, 0, 0, 0
BEGIN DESCRIPTION:
Multiple Run
END DESCRIPTION:

--- UNT0736 IN SPCR.f01 (steady flow) ---

Flow Title=Multiple
Number of Profiles=7
Profile Names=10-year,25-year,50-year,1pct_min,100-year,1pct_plu,500-year
River Rch & RM= UNT0736 IN SPCR,Reach-1,3810
     296     402     486     432     584     789     842
Boundary for River Rch & Prof#=UNT0736 IN SPCR,Reach-1,1
Up Type=0
Dn Type=3
Dn Slope=0.005
Boundary for River Rch & Prof#=UNT0736 IN SPCR,Reach-1,2
Up Type=0
Dn Type=3
Dn Slope=0.005
Boundary for River Rch & Prof#=UNT0736 IN SPCR,Reach-1,3
Up Type=0
Dn Type=3
Dn Slope=0.005
Boundary for River Rch & Prof#=UNT0736 IN SPCR,Reach-1,4
Up Type=0
Dn Type=3
Dn Slope=0.005
Boundary for River Rch & Prof#=UNT0736 IN SPCR,Reach-1,5
Up Type=0
Dn Type=3
Dn Slope=0.005
Boundary for River Rch & Prof#=UNT0736 IN SPCR,Reach-1,6
Up Type=0
Dn Type=3
Dn Slope=0.005
Boundary for River Rch & Prof#=UNT0736 IN SPCR,Reach-1,7
Up Type=0
Dn Type=3
Dn Slope=0.005

--- UNT0736 IN SPCR.g01 (geometry) ---

Geom Title=Existing Conditions
Program Version=4.10

River Reach=UNT0736 IN SPCR ,Reach-1
Reach XY= 30
      2296421.68     13372852.82      2296434.95     13372741.61
      2296410.61     13372603.14      2296523.74      13372347.7
      2296626.17     13371729.64       2296747.7     13371529.99
      2296789.37     13371398.04      2296799.78     13371262.63
      2296787.63     13371212.28      2296726.87     13371102.91
      2296575.83     13370967.49      2296428.12     13370700.21
      2296382.47     13370647.29      2296354.18     13370636.92
      2296231.62     13370454.86      2296195.25     13370427.79
      2296182.37     13370375.24      2296045.28      13370263.3
      2295990.05     13370111.19      2295913.44     13370111.86
      2295795.71     13370081.65      2295759.71     13370000.74
      2295693.39     13369942.56      2295659.74     13369940.82
      2295526.14     13369870.16      2295337.07     13369745.91
      2295267.72     13369676.85      2295259.86     13369642.73
      2295218.88       13369606.      2295201.26     13369565.79

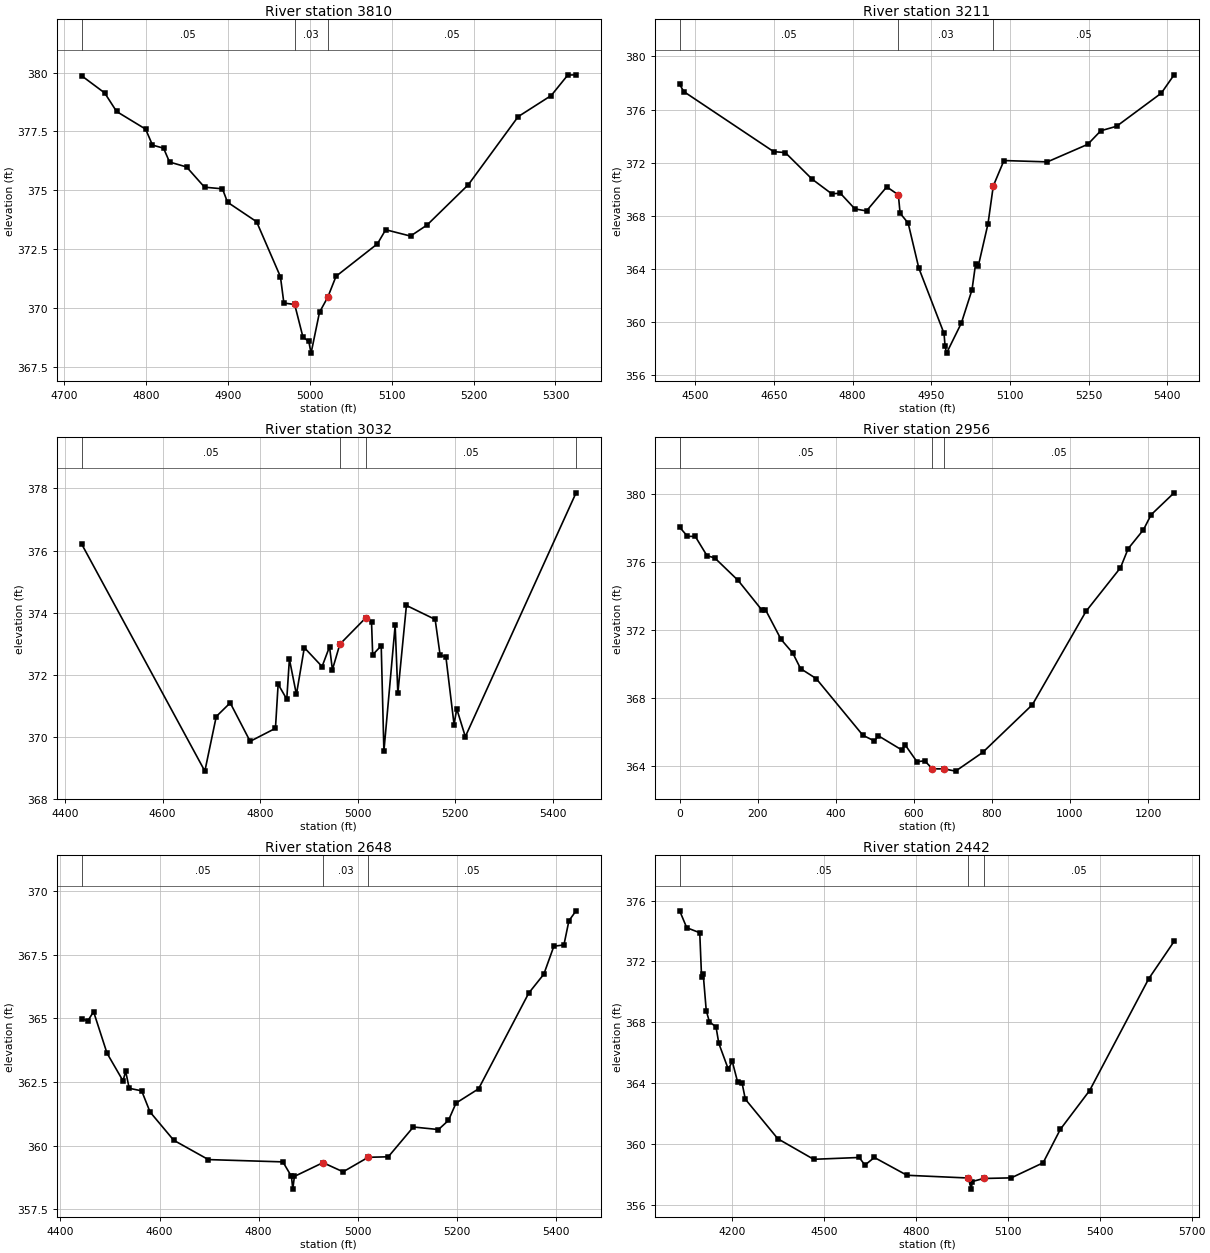
Type RM Length L Ch R = 1 ,3810    ,599,599,599
BEGIN DESCRIPTION:
UNT0736 IN SPCR 2.0
END DESCRIPTION:
XS GIS Cut Line= 3
      2296687.73     13372646.86      2296487.72     13372496.85
      2296137.68     13372446.85
#Sta/Elev= 30
  4721.5  379.87  4749.6  379.14  4764.2  378.35  4799.6   377.6    4808  376.92
  4821.5  376.79  4828.8   376.2  4849.6  375.99  4871.5  375.13  4893.4  375.06
  4899.6  374.49  4935.1  373.66  4964.2  371.32  4968.4   370.2  4981.6  370.14
  4991.7  368.75  4998.8  368.57  5001.6  368.07  5011.9  369.81    5022  370.45
  5032.1  371.34  5082.6  372.72  5092.7  373.32    5123  373.05  5143.2  373.52
  5193.7  375.24  5254.4  378.13  5294.8  379.03    5315   379.9  5325.1  379.91
#Mann= 3 , 0 , 0
  4721.5     .05       0  4981.6     .03       0    5022     .05       0
Bank Sta=4981.6,5022
XS Rating Curve= 0 ,0
Exp/Cntr=0.3,0.1

Type RM Length L Ch R = 1 ,3211    ,179,179,179
BEGIN DESCRIPTION:
Mapping XS 8fb87ad9
END DESCRIPTION:
XS GIS Cut Line= 4
      2296895.14     13372311.03      2296700.71     13371936.06
      2296457.66     13371894.39      2296201.75     13371991.22
#Sta/Elev= 30
  4470.3  377.89  4478.1  377.35  4649.5  372.83  4671.6  372.76  4722.8  370.76
  4760.1  369.66  4776.6   369.7  4804.4  368.52  4826.5  368.37  4865.1  370.18
  4887.2  369.58  4890.5   368.2  4905.9  367.45  4926.2  364.07  4974.3  359.15
  4976.3  358.17  4979.1  357.67  5007.3  359.93  5027.6  362.43  5034.3  364.34
  5039.4  364.19  5058.1   367.4  5068.2  370.25  5088.5  372.16  5171.3  372.06
  5248.3  373.38  5273.1   374.4  5303.3  374.74  5388.5  377.23  5412.9  378.61
#Mann= 3 , 0 , 0
  4470.3     .05       0  4887.2     .03       0  5068.2     .05       0
Bank Sta=4887.2,5068.2
XS Rating Curve= 0 ,0
Exp/Cntr=0.3,0.1

Type RM Length L Ch R = 1 ,3032    ,76,76,76
BEGIN DESCRIPTION:
Mapping XS cd5f07f2
END DESCRIPTION:
XS GIS Cut Line= 5
        2296916.     13372193.02      2296735.43     13371790.22
      2296659.04     13371741.61      2296596.54     13371741.61
      2296214.61     13371915.22
#Sta/Elev= 30
  4433.8  376.21  4686.5  368.89  4709.9  370.65  4738.5  371.09  4779.4  369.85
  4831.3  370.27  4836.8  371.69  4854.5  371.21  4859.9   372.5  4874.3  371.36
  4890.5  372.87  4926.9  372.26  4942.2   372.9  4948.1  372.16  4963.4  372.98
  5017.1  373.84  5028.3  373.71  5030.7  372.64  5048.2  372.93  5053.7  369.53
  5076.8  373.59  5082.3   371.4  5099.9  374.23  5158.8  373.78  5169.1  372.62
  5180.8  372.58  5197.6  370.39  5203.1   370.9  5220.7     370  5447.8  377.86
#Mann= 4 ,-1 , 0
  4433.8     .05       0  4963.4     .03       0  5017.1     .05       0
  5447.8     .05       0
Bank Sta=4963.4,5017.1
XS Rating Curve= 0 ,0
Exp/Cntr=0.3,0.1

Type RM Length L Ch R = 1 ,2956    ,308,308,308
BEGIN DESCRIPTION:
Mapping XS 36c2cdd4
END DESCRIPTION:
XS GIS Cut Line= 4
       2297027.1       13372193.     2296823.631    13371791.076
     2296558.874    13371619.201     2296124.322    13371866.611
#Sta/Elev= 30
       0378.046819.97969377.512939.95938377.508269.92891376.3769 89.9086376.2424
149.8477374.9171209.7867373.2026219.7766373.2009 259.736371.4527289.7055370.6525
309.6852 369.735349.6446369.1505469.3464365.8153499.0515365.4779508.9532365.7862
568.3635 364.961578.2651365.2288607.9703364.2596627.7737 364.313647.5771363.8401
677.2822363.8381706.9873363.7064776.2081 364.804903.7455367.61451041.094373.1048
1129.389375.6668 1149.01376.78641188.252377.90161207.873378.78321266.737380.0717
#Mann= 3 , 0 , 0
       0     .05       0647.5771     .03       0677.2822     .05       0
Bank Sta=647.5771,677.2822
XS Rating Curve= 0 ,0
Exp/Cntr=0.3,0.1

Type RM Length L Ch R = 1 ,2648    ,206,206,206
BEGIN DESCRIPTION:
Mapping XS 9add60e1
END DESCRIPTION:
XS GIS Cut Line= 3
      2297068.76     13371748.55      2296950.71     13371373.56
      2296353.51     13371470.77
#Sta/Elev= 30
  4442.8  364.99  4455.1  364.89  4466.9  365.26    4494  363.63  4526.4  362.54
  4531.6  362.92  4538.9  362.25    4564  362.15  4580.9  361.32  4628.7  360.21
  4698.7  359.45  4849.1  359.36  4866.4  358.79  4869.1  358.29  4872.4  358.79
  4930.1  359.33  4970.7  358.97  5021.3  359.54  5061.9  359.56  5112.5  360.73
  5163.2  360.63  5183.4  360.99  5198.7  361.67  5244.2  362.23  5345.5  365.99
  5375.9  366.73  5396.2  367.83  5416.5  367.88  5426.6  368.83    5441  369.22
#Mann= 3 , 0 , 0
  4442.8     .05       0  4930.1     .03       0  5021.3     .05       0
Bank Sta=4930.1,5021.3
XS Rating Curve= 0 ,0
Exp/Cntr=0.3,0.1

Type RM Length L Ch R = 1 ,2442    ,0,0,0
BEGIN DESCRIPTION:
UNT0736 IN SPCR 1.0
END DESCRIPTION:
XS GIS Cut Line= 4
      2297286.97     13371848.54      2297052.59     13371192.28
      2296563.68     13371203.36      2296209.15     13371442.08
#Sta/Elev= 30
  4029.4  375.33  4052.4  374.22  4094.9  373.89  4100.9  370.95  4106.2  371.17
  4116.1  368.77  4126.3  368.04    4148   367.7  4157.1  366.62  4187.9  364.93
  4201.1  365.43  4218.7  364.06  4232.9  364.02  4243.6  362.95  4349.7  360.35
  4466.6     359  4615.2  359.12  4633.9  358.62  4664.7  359.12  4771.1  357.95
  4971.2  357.77  4980.9  357.04  4984.2  357.54  5021.2  357.74  5111.2  357.78
  5215.3  358.77  5271.5  360.97  5367.1  363.52    5560  370.87  5642.7  373.32
#Mann= 3 , 0 , 0
  4029.4     .05       0  4971.2     .03       0  5021.2     .05       0
Bank Sta=4971.2,5021.2
XS Rating Curve= 0 ,0
Exp/Cntr=0.3,0.1

Chan Stop Cuts=-1
Use User Specified Reach Order=0
Composite Channel Slope=5