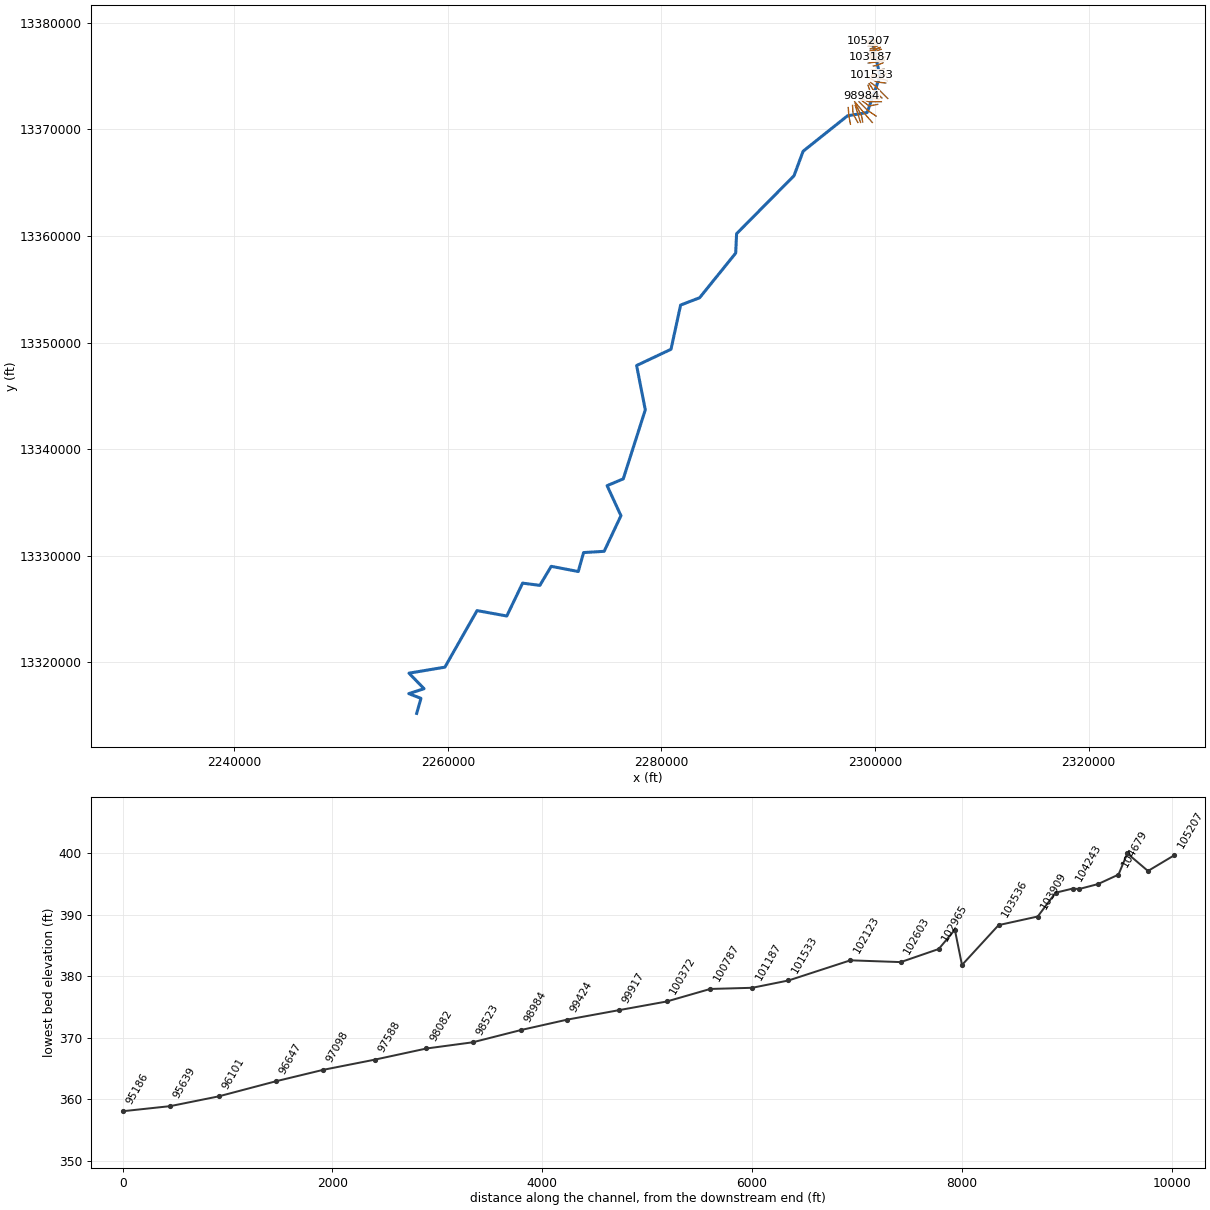
--- VATOSS GULLY.prj (project) ---

Proj Title=VATOSS GULLY Base Level Engineering
Current Plan=p01
Default Exp/Contr=0.3,0.1
English Units
Geom File=g01
Flow File=f01
Plan File=p01
Y Axis Title=Elevation
X Axis Title(PF)=Main Channel Distance
X Axis Title(XS)=Station
BEGIN DESCRIPTION:
VATOSS GULLY
END DESCRIPTION:
DSS Export Rating Curves= 0
DSS Export Rating Curve Sorted= 0
DSS Export Volume Flow Curves= 0
DXF OffsetX= 0
DXF OffsetY= 0
DXF ScaleX= 1
DXF ScaleY= 10

--- VATOSS GULLY.p01 (plan) ---

Plan Title=Multiple Run
Short Identifier=Multiple
Geom File=g01
Flow File=f01
Subcritical Flow
K Sum by GR= 0
Std Step Tol= 0.01
Critical Tol= 0.01
Num of Std Step Trials= 20
Max Error Tol= 0.3
Flow Tol Ratio= 0.001
Split Flow NTrial= 30
Split Flow Tol= 0.02
Split Flow Ratio= 0.02
Log Output Level= 0
Friction Slope Method= 1
Unsteady Friction Slope Method= 2
Unsteady Bridges Friction Slope Method= 1
Parabolic Critical Depth
Global Vel Dist=  1 , 1 , 1
Global Log Level= 0
CheckData=True
Encroach Param= -1, 0, 0, 0
BEGIN DESCRIPTION:
Multiple Run
END DESCRIPTION:

--- VATOSS GULLY.f01 (steady flow) ---

Flow Title=Multiple
Program Version=4.10
Number of Profiles= 7
Profile Names=10-year,25-year,50-year,1pct_min,100-year,1pct_plu,500-year
River Rch & RM=VATOSS GULLY,Reach-1         ,105207
     530     739     912     822    1112    1504    1658
River Rch & RM=VATOSS GULLY,Reach-1         ,101187
     688     973    1212    1101    1489    2014    2258
River Rch & RM=VATOSS GULLY,Reach-1         ,100372
     991    1424    1792    1643    2221    3004    3430
River Rch & RM=VATOSS GULLY,Reach-1         ,99917
     991    1424    1792    1643    2221    3004    3430
River Rch & RM=VATOSS GULLY,Reach-1         ,94582
    1222    1775    2249    2074    2805    3793    4385
River Rch & RM=VATOSS GULLY,Reach-1         ,91958
    1222    1775    2249    2074    2805    3793    4385
River Rch & RM=VATOSS GULLY,Reach-1         ,87774
    1336    1945    2469    2280    3083    4169    4834
River Rch & RM=VATOSS GULLY,Reach-1         ,82380
    1336    1948    2475    2290    3097    4189    4884
River Rch & RM=VATOSS GULLY,Reach-1         ,74971
    1308    1907    2424    2245    3035    4105    4800
River Rch & RM=VATOSS GULLY,Reach-1         ,70468
    1314    1917    2439    2262    3059    4137    4854
River Rch & RM=VATOSS GULLY,Reach-1         ,64275
    2445    3658    4732    4456    6026    8149    9854
River Rch & RM=VATOSS GULLY,Reach-1         ,63497
    2445    3658    4732    4456    6026    8149    9854
River Rch & RM=VATOSS GULLY,Reach-1         ,60895
    2402    3589    4639    4365    5903    7983    9645
River Rch & RM=VATOSS GULLY,Reach-1         ,56992
    2373    3543    4576    4304    5821    7872    9505
River Rch & RM=VATOSS GULLY,Reach-1         ,54619
    2356    3510    4530    4256    5756    7784    9381
River Rch & RM=VATOSS GULLY,Reach-1         ,45786
    2356    3511    4532    4260    5762    7792    9404
River Rch & RM=VATOSS GULLY,Reach-1         ,40848
    2374    3536    4562    4288    5799    7843    9468
River Rch & RM=VATOSS GULLY,Reach-1         ,31313
    2416    3601    4648    4370    5910    7993    9658
River Rch & RM=VATOSS GULLY,Reach-1         ,30208
    2427    3618    4672    4396    5944    8039    9725
River Rch & RM=VATOSS GULLY,Reach-1         ,29309
    2403    3576    4613    4335    5863    7929    9574
River Rch & RM=VATOSS GULLY,Reach-1         ,19413
    2456    3659    4723    4444    6010    8128    9843
River Rch & RM=VATOSS GULLY,Reach-1         ,19005
    2456    3659    4723    4444    6010    8128    9843
River Rch & RM=VATOSS GULLY,Reach-1         ,10161
    2511    3742    4831    4547    6149    8316   10072
Boundary for River Rch & Prof#=VATOSS GULLY,Reach-1         , 1
Up Type= 0
Dn Type= 3
Dn Slope=0.005
Boundary for River Rch & Prof#=VATOSS GULLY,Reach-1         , 2
Up Type= 0
Dn Type= 3
Dn Slope=0.005
Boundary for River Rch & Prof#=VATOSS GULLY,Reach-1         , 3
Up Type= 0
Dn Type= 3
Dn Slope=0.005
Boundary for River Rch & Prof#=VATOSS GULLY,Reach-1         , 4
Up Type= 0
Dn Type= 3
Dn Slope=0.005
Boundary for River Rch & Prof#=VATOSS GULLY,Reach-1         , 5
Up Type= 0
Dn Type= 3
Dn Slope=0.005
Boundary for River Rch & Prof#=VATOSS GULLY,Reach-1         , 6
Up Type= 0
Dn Type= 3
Dn Slope=0.005
Boundary for River Rch & Prof#=VATOSS GULLY,Reach-1         , 7
Up Type= 0
Dn Type= 3
Dn Slope=0.005
DSS Import GetInterval= 0
DSS Import GetPeak= 0
DSS Import FillOption= 0

--- VATOSS GULLY.g01 (geometry) ---

Geom Title=Existing Conditions
Program Version=4.10

River Reach=VATOSS GULLY    ,Reach-1
Reach XY= 30
      2299689.99     13378543.82       2300456.7     13374976.09
      2299252.59     13371579.29      2297413.93     13371271.88
      2293262.28     13367949.82      2292406.06     13365646.98
      2287032.76     13360209.48      2286948.05     13358386.84
      2283568.04     13354197.15      2281791.62     13353514.44
      2280892.15     13349364.15      2277673.27     13347839.27
      2278485.64     13343682.62      2276422.87      13337204.1
      2274910.51      13336565.7      2276206.87     13333747.31
      2274632.77       13330404.      2272707.72     13330286.86
      2272211.66     13328508.52      2269677.67     13328995.77
      2268616.78     13327209.15      2267001.05     13327418.92
      2265519.84     13324335.15       2262735.7     13324841.88
      2259724.53     13319533.54      2256363.14     13318969.36
      2257776.12     13317511.05      2256345.05     13317050.16
      2257485.66     13316605.95      2257084.22     13315196.81

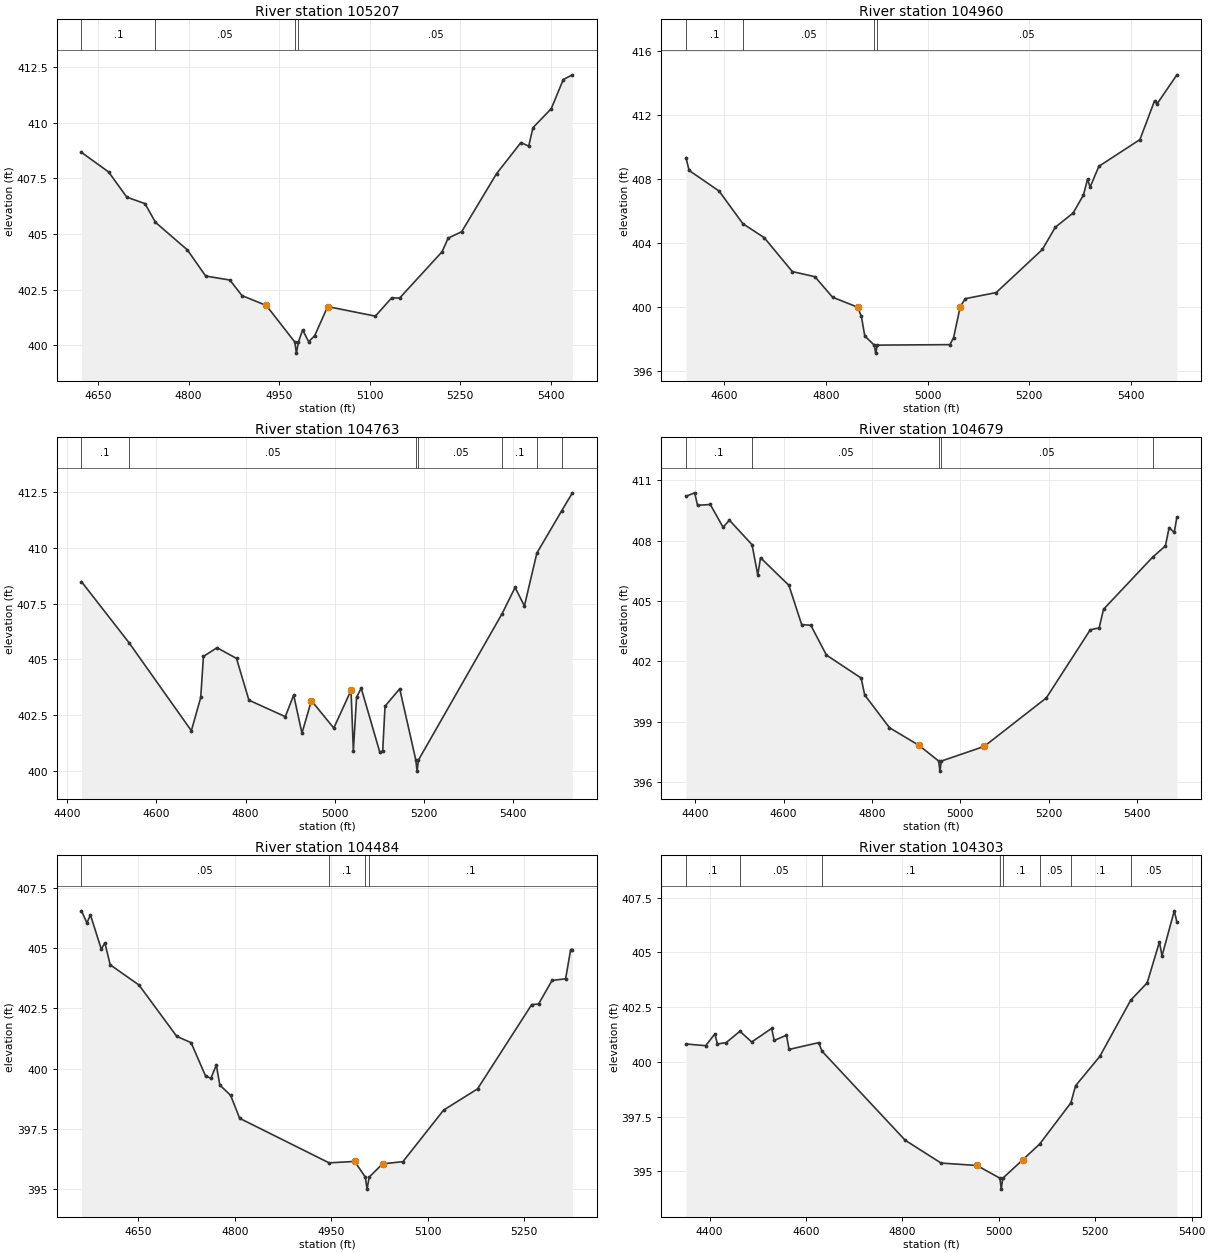
Type RM Length L Ch R = 1 ,105207  ,247,247,247
BEGIN DESCRIPTION:
VATOSS GULLY 167.0
END DESCRIPTION:
XS GIS Cut Line= 2
      2300182.55     13378388.08      2299372.72     13378315.17
#Sta/Elev= 30
  4622.5  408.66  4667.5  407.78  4697.6  406.65  4727.7  406.36  4745.1  405.52
    4798  404.28  4828.2  403.11  4868.3  402.93  4888.4  402.23  4928.6  401.79
  4975.8  400.15  4978.5  399.65  4981.8  400.15  4988.8  400.69  4998.8  400.16
  5008.9  400.44  5030.2  401.74  5109.3  401.31  5136.2  402.13  5149.4  402.12
  5219.7   404.2  5229.8  404.81  5252.2   405.1  5310.1  407.71  5350.3   409.1
  5363.2  408.94  5370.3  409.77  5400.5  410.62  5420.5  411.93  5435.6  412.14
#Mann= 4 ,-1 , 0
  4622.5      .1       0  4745.1     .05       0  4975.8     .04       0
  4981.8     .05       0
Bank Sta=4928.6,5030.2
XS Rating Curve= 0 ,0
Exp/Cntr=0.3,0.1

Type RM Length L Ch R = 1 ,104960  ,197,197,197
BEGIN DESCRIPTION:
Mapping XS 7a852284
END DESCRIPTION:
XS GIS Cut Line= 4
      2300216.42     13378325.57      2299974.26      13378208.4
      2299888.32     13378112.04      2299325.78     13378197.99
#Sta/Elev= 30
  4524.1  409.33  4530.4  408.53  4589.3  407.25  4636.2  405.21  4678.2  404.34
  4733.7  402.22  4778.2   401.9  4812.9  400.62  4862.2     400  4869.7  399.43
  4876.4   398.2  4895.1  397.63  4897.9  397.13  4901.1  397.63  5044.2  397.66
  5051.4   398.1  5064.5  400.04  5074.6  400.53  5135.3  400.91  5226.3   403.6
  5251.8  404.99    5287  405.88  5307.2     407  5315.3  407.99  5320.3  407.49
  5337.6  408.79  5418.5  410.46  5447.3  412.88  5452.3  412.69  5491.3   414.5
#Mann= 4 ,-1 , 0
  4524.1      .1       0  4636.2     .05       0  4895.1    .035       0
  4901.1     .05       0
Bank Sta=4862.2,5064.5
XS Rating Curve= 0 ,0
Exp/Cntr=0.3,0.1

Type RM Length L Ch R = 1 ,104763  ,84,84,84
BEGIN DESCRIPTION:
Mapping XS 4e9abcc2
END DESCRIPTION:
XS GIS Cut Line= 6
      2300231.85     13378283.38       2299988.8     13378118.46
      2299910.67     13377975.23      2299901.99     13377931.82
      2299810.85     13377927.48      2299324.74     13378075.05
#Sta/Elev= 30
    4432  408.48  4538.4  405.75  4678.3   401.8  4699.3  403.29  4705.4  405.13
  4735.8  405.52  4779.5  405.04  4807.3  403.17  4888.9  402.43  4907.6   403.4
  4926.2  401.69  4947.4  403.15  4997.5  401.92  5036.2  403.61  5041.4   400.9
  5048.6   403.3    5059  403.71  5100.8  400.83  5107.2   400.9  5112.4   402.9
  5145.3  403.68  5181.4  400.49  5184.2  399.99  5187.4  400.49  5374.9  407.05
  5403.9  408.22  5424.8  407.39  5452.7  409.76  5508.5  411.66  5532.4  412.46
#Mann= 7 ,-1 , 0
    4432      .1       0  4538.4     .05       0  5181.4     .03       0
  5187.4     .05       0  5374.9      .1       0  5452.7     .05       0
  5508.5      .1       0
Bank Sta=4947.4,5036.2
XS Rating Curve= 0 ,0
Exp/Cntr=0.3,0.1

Type RM Length L Ch R = 1 ,104679  ,195,195,195
BEGIN DESCRIPTION:
Mapping XS d51b03d7
END DESCRIPTION:
XS GIS Cut Line= 3
      2300357.75     13378144.52      2299971.44     13377840.68
       2299351.7     13377862.35
#Sta/Elev= 30
  4378.9  410.21  4398.7  410.38  4405.1  409.76    4434   409.8  4462.9  408.67
  4477.3  409.02  4528.6   407.8  4541.5   406.3  4547.8  407.15    4612  405.78
  4640.9  403.83  4661.7  403.79    4697  402.31  4775.6  401.17  4783.6  400.33
  4839.7   398.7  4906.6  397.82  4951.2  397.04  4953.9  396.54  4957.2  397.04
  5054.2  397.77  5194.8  400.18  5294.4  403.57  5314.4  403.66  5324.4  404.59
  5435.5  407.18  5464.5  407.74  5472.9  408.65  5484.5  408.41  5490.5  409.18
#Mann= 5 ,-1 , 0
  4378.9      .1       0  4528.6     .05       0  4951.2     .03       0
  4957.2     .05       0  5435.5      .1       0
Bank Sta=4906.6,5054.2
XS Rating Curve= 0 ,0
Exp/Cntr=0.3,0.1

Type RM Length L Ch R = 1 ,104484  ,181,181,181
BEGIN DESCRIPTION:
VATOSS GULLY 166.0
END DESCRIPTION:
XS GIS Cut Line= 3
      2300237.74     13377846.87      2299837.72     13377646.85
      2299537.69     13377546.84
#Sta/Elev= 30
  4561.5  406.55  4569.9  406.05  4575.5  406.38  4592.3  404.96  4597.9  405.22
  4606.2  404.31    4651  403.47  4709.7  401.34    4732  401.08  4754.4   399.7
  4762.8   399.6  4771.2  400.15  4776.7  399.32  4793.5  398.89  4807.5  397.94
  4946.6  396.09  4986.4  396.15  5002.9   395.5  5005.7     395  5008.9   395.5
  5029.8  396.05  5061.4  396.14  5124.7  398.28  5177.4  399.16  5261.7  402.66
  5272.3  402.68  5293.3  403.66  5314.4  403.73  5322.3  404.94    5325  404.94
#Mann= 4 ,-1 , 0
  4561.5     .05       0  4946.6      .1       0  5002.9     .07       0
  5008.9      .1       0
Bank Sta=4986.4,5029.8
XS Rating Curve= 0 ,0
Exp/Cntr=0.3,0.1

Type RM Length L Ch R = 1 ,104303  ,60,60,60
BEGIN DESCRIPTION:
Mapping XS ccec1a29
END DESCRIPTION:
XS GIS Cut Line= 2
       2300466.2      13377693.1      2299507.04     13377350.23
#Sta/Elev= 30
  4350.8  400.82  4391.7  400.74  4410.8  401.28  4416.1  400.82  4434.1  400.88
  4462.8   401.4  4487.2  400.91  4528.6  401.53  4533.9  400.98  4559.4  401.22
  4564.7  400.57  4626.2  400.88  4633.1  400.49  4805.8  396.42  4880.2  395.38
  4954.5  395.27  5002.2  394.69  5004.9  394.19  5008.2  394.69  5050.1  395.54
  5084.7  396.25  5149.4  398.13  5159.1  398.91  5209.4  400.25  5273.6  402.82
  5307.7  403.61  5333.2  405.48  5338.5  404.84    5364   406.9  5369.4  406.39
#Mann= 8 ,-1 , 0
  4350.8      .1       0  4462.8     .05       0  4633.1      .1       0
  5002.2     .07       0  5008.2      .1       0  5084.7     .05       0
  5149.4      .1       0  5273.6     .05       0
Bank Sta=4954.5,5050.1
XS Rating Curve= 0 ,0
Exp/Cntr=0.3,0.1

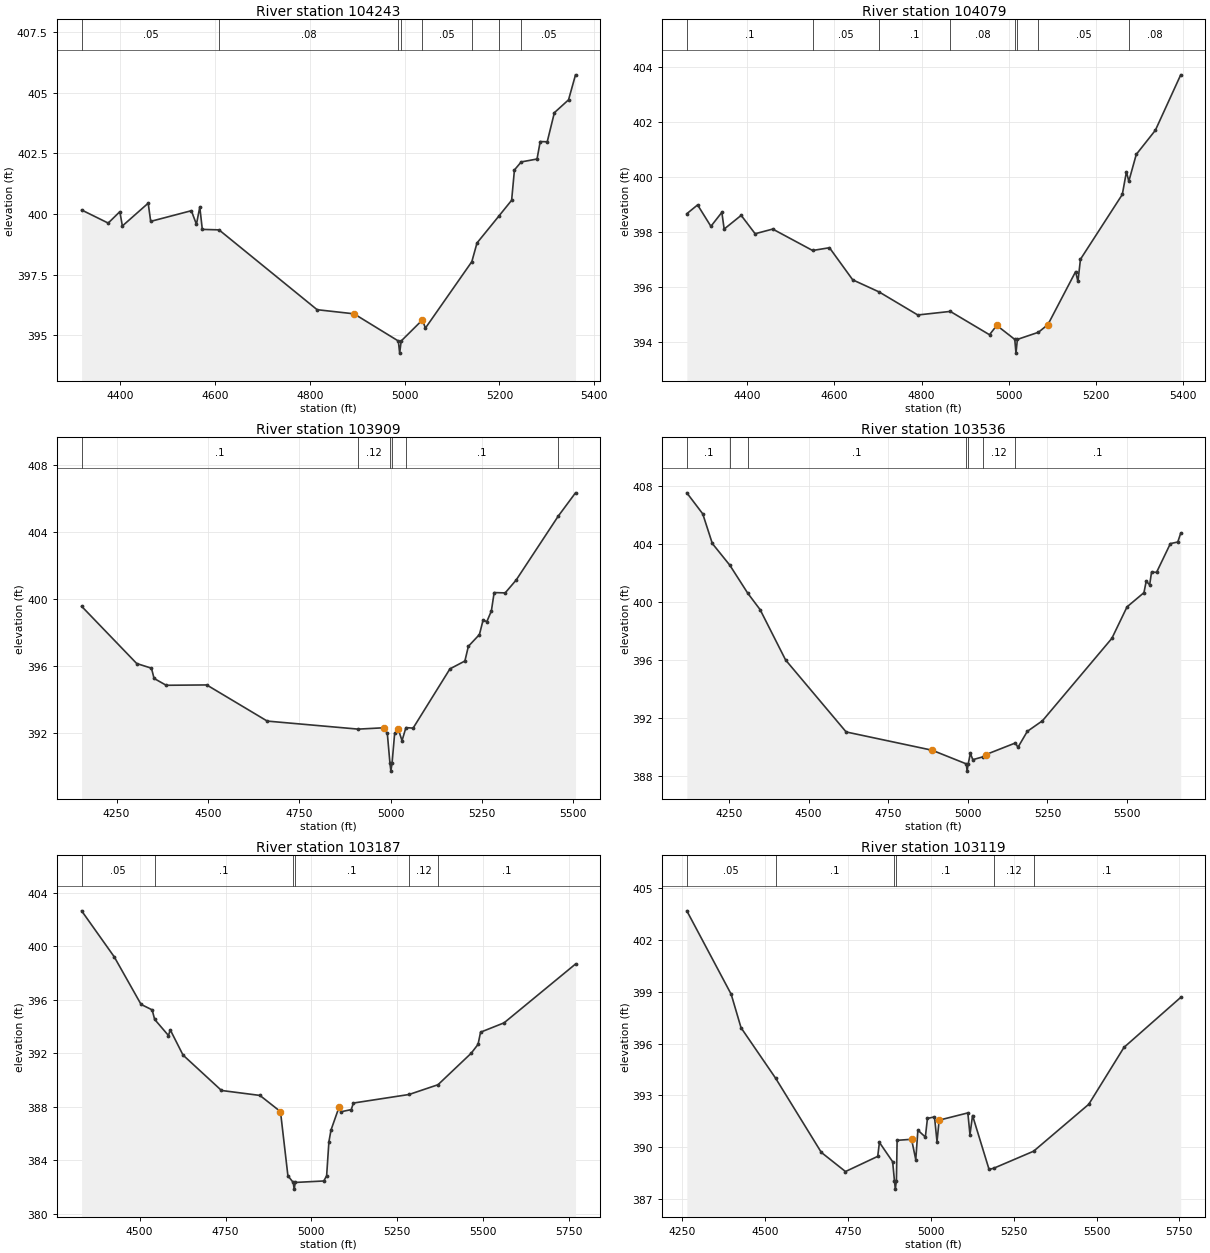
Type RM Length L Ch R = 1 ,104243  ,164,164,164
BEGIN DESCRIPTION:
Mapping XS c7a0ca2b
END DESCRIPTION:
XS GIS Cut Line= 2
      2300483.62     13377662.74      2299512.02     13377285.38
#Sta/Elev= 30
  4318.3  400.17  4374.4  399.63    4399   400.1  4404.3  399.51  4458.8  400.45
  4464.1   399.7  4549.9  400.14  4560.6  399.58  4567.7  400.29    4573  399.37
  4608.3  399.35  4815.3  396.06  4893.2  395.89  4986.7  394.77  4989.5  394.27
  4992.7  394.77  5037.6  395.64  5043.8   395.3  5141.8  398.04  5152.7  398.81
  5198.5  399.91  5225.8  400.57  5231.7  401.82    5246  402.15  5279.4  402.27
  5286.1  402.99  5300.9  402.98    5316  404.18  5345.9  404.71  5360.6  405.74
#Mann= 8 ,-1 , 0
  4318.3     .05       0  4608.3     .08       0  4986.7     .07       0
  4992.7     .08       0  5037.6     .05       0  5141.8      .1       0
  5198.5     .08       0    5246     .05       0
Bank Sta=4893.2,5037.6
XS Rating Curve= 0 ,0
Exp/Cntr=0.3,0.1

Type RM Length L Ch R = 1 ,104079  ,170,170,170
BEGIN DESCRIPTION:
Mapping XS 4f87a8f2
END DESCRIPTION:
XS GIS Cut Line= 2
      2300574.69      13377510.8      2299512.02     13377120.43
#Sta/Elev= 30
  4261.7  398.67  4286.4  398.99  4316.9  398.21    4342  398.72  4347.3  398.11
  4386.3  398.61  4418.3  397.94  4458.6  398.11    4550  397.33  4588.7  397.43
    4642  396.26  4702.4  395.82  4791.1  394.98  4865.6  395.11  4955.5  394.26
  4972.2   394.6  5013.4  394.09  5016.2  393.59  5019.4  394.09  5067.7  394.35
  5089.4  394.63  5152.9  396.56  5158.2   396.2    5164  397.01  5259.9  399.37
  5269.4   400.2  5274.8  399.85  5291.9  400.83  5335.7  401.71  5393.8  403.73
#Mann= 8 ,-1 , 0
  4261.7      .1       0    4550     .05       0  4702.4      .1       0
  4865.6     .08       0  5013.4     .07       0  5019.4     .08       0
  5067.7     .05       0  5274.8     .08       0
Bank Sta=4972.2,5089.4
XS Rating Curve= 0 ,0
Exp/Cntr=0.3,0.1

Type RM Length L Ch R = 1 ,103909  ,373,373,373
BEGIN DESCRIPTION:
Mapping XS e2ba60f2
END DESCRIPTION:
XS GIS Cut Line= 3
      2300737.26     13377197.98      2299627.91     13377052.15
      2299396.18     13377075.58
#Sta/Elev= 30
  4154.4  399.57  4305.2  396.15  4345.6  395.87  4352.7  395.26  4385.9  394.85
  4496.9  394.87  4662.5  392.71  4911.4  392.23    4981  392.31  4991.1  391.98
  4998.2  390.22  5000.9  389.72  5004.2  390.22  5011.2  391.98  5021.3  392.21
  5031.4  391.54    5042  392.32  5061.7  392.29  5162.5  395.83  5203.4   396.3
    5213  397.18  5243.2  397.88  5253.3  398.75  5263.4  398.65  5275.9  399.29
  5283.5  400.39  5313.7  400.37  5343.8  401.14    5459  404.96  5506.2  406.35
#Mann= 6 ,-1 , 0
  4154.4      .1       0  4911.4     .12       0  4998.2     .07       0
  5004.2     .12       0    5042      .1       0    5459     .08       0
Bank Sta=4981,5021.3
XS Rating Curve= 0 ,0
Exp/Cntr=0.3,0.1

Type RM Length L Ch R = 1 ,103536  ,349,349,349
BEGIN DESCRIPTION:
VATOSS GULLY 164.0
END DESCRIPTION:
XS GIS Cut Line= 3
      2300937.71     13376796.85      2300037.72     13376796.85
      2299437.72     13377046.86
#Sta/Elev= 30
  4118.1   407.5  4168.1  406.05  4198.1  404.01  4253.1  402.51  4309.1  400.59
  4348.1  399.45  4428.1  395.98  4618.1  391.02  4888.1  389.76  4995.1  388.82
  4997.8  388.32  5001.1  388.82  5008.1  389.54  5015.6  389.11  5048.2  389.31
  5056.6  389.46  5149.2  390.26  5157.3  389.96  5186.6  391.06  5234.2  391.79
    5452  397.47  5499.6  399.64  5552.7  400.62  5559.8  401.41  5570.6  401.16
  5576.6  402.04  5592.3  402.02  5635.6     404  5658.9  404.11  5668.1  404.72
#Mann= 7 ,-1 , 0
  4118.1      .1       0  4253.1     .05       0  4309.1      .1       0
  4995.1     .07       0  5001.1      .1       0  5048.2     .12       0
  5149.2      .1       0
Bank Sta=4888.1,5056.6
XS Rating Curve= 0 ,0
Exp/Cntr=0.3,0.1

Type RM Length L Ch R = 1 ,103187  ,68,68,68
BEGIN DESCRIPTION:
Mapping XS eb3b93a0
END DESCRIPTION:
XS GIS Cut Line= 4
      2300817.78     13376568.97      2300214.49     13376456.13
      2300019.18     13376729.57      2299537.38     13376803.36
#Sta/Elev= 30
  4331.3  402.65  4426.2  399.21  4504.3  395.65  4536.6  395.24  4543.8  394.53
  4584.1  393.32  4589.2  393.75  4626.4  391.86  4738.3  389.21  4850.2  388.84
    4910  387.63  4931.6  382.83  4947.1  382.33  4949.8  381.83  4953.1  382.33
  5036.1  382.44  5044.3  382.83  5050.9  385.37    5057  386.25  5080.4  387.96
  5086.5  387.62    5116  387.78  5122.1  388.27  5284.1  388.91  5368.3  389.64
  5464.7  391.99  5484.9  392.66  5492.2  393.57  5560.6  394.27  5768.5  398.67
#Mann= 6 ,-1 , 0
  4331.3     .05       0  4543.8      .1       0  4947.1     .07       0
  4953.1      .1       0  5284.1     .12       0  5368.3      .1       0
Bank Sta=4910,5080.4
XS Rating Curve= 0 ,0
Exp/Cntr=0.3,0.1

Type RM Length L Ch R = 1 ,103119  ,154,154,154
BEGIN DESCRIPTION:
Mapping XS c71bac79
END DESCRIPTION:
XS GIS Cut Line= 4
       2300848.7     13376525.03      2300180.31      13376403.5
      2299967.64      13376672.6      2299500.76     13376702.86
#Sta/Elev= 30
  4263.7   403.7  4397.6  398.86  4427.3  396.92  4531.7  393.99  4669.5  389.69
  4742.4  388.58  4839.7  389.46  4844.8  390.27  4884.7  389.15  4890.1  388.06
  4892.8  387.56  4896.1  388.06  4898.2  390.39  4941.8  390.45  4954.5  389.27
  4960.9  390.98  4983.4  390.58  4989.7  391.66    5011  391.75  5018.6  390.31
    5025  391.56  5111.6  391.98    5118  390.72  5125.8  391.83  5175.7   388.7
  5190.8  388.78  5310.1  389.76  5476.4  392.48  5582.7  395.78  5753.9  398.68
#Mann= 6 ,-1 , 0
  4263.7     .05       0  4531.7      .1       0  4890.1     .07       0
  4896.1      .1       0  5190.8     .12       0  5310.1      .1       0
Bank Sta=4941.8,5025
XS Rating Curve= 0 ,0
Exp/Cntr=0.3,0.1

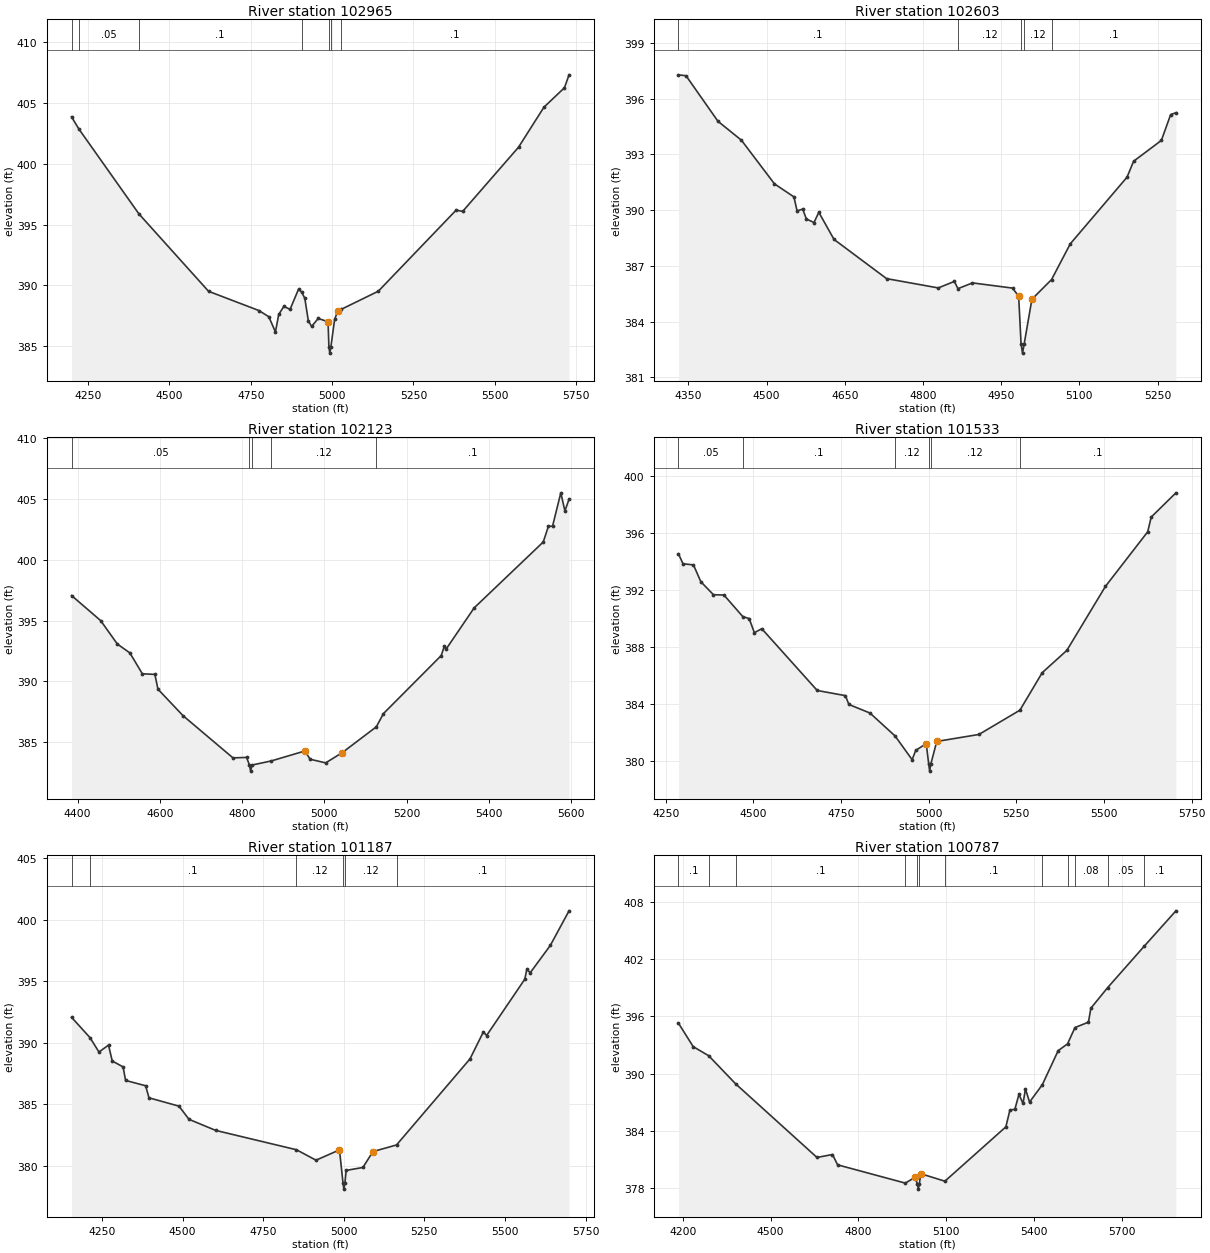
Type RM Length L Ch R = 1 ,102965  ,362,362,362
BEGIN DESCRIPTION:
VATOSS GULLY 163.0
END DESCRIPTION:
XS GIS Cut Line= 3
      2300864.93      13376455.8      2300203.43      13376338.6
      2299353.84     13376221.69
#Sta/Elev= 30
  4198.9  403.85  4220.9  402.87  4406.1  395.87  4620.2  389.51  4774.9  387.93
  4805.4  387.42  4825.7  386.17  4835.9  387.61  4851.6  388.27  4870.7  388.03
  4896.7  389.68    4906  389.46    4916  388.94  4926.9  387.08    4937  386.62
  4957.2  387.28  4987.5  387.01  4990.1  384.93  4992.8  384.43  4996.1  384.93
  5007.7   387.2  5017.8  387.93  5027.3  388.02  5142.1  389.52  5381.2  396.18
  5401.4  396.08    5573  401.35  5651.2  404.64  5714.3  406.24  5728.3   407.3
#Mann= 7 ,-1 , 0
  4198.9      .1       0  4220.9     .05       0  4406.1      .1       0
    4906     .12       0  4990.1     .07       0  4996.1     .12       0
  5027.3      .1       0
Bank Sta=4987.5,5017.8
XS Rating Curve= 0 ,0
Exp/Cntr=0.3,0.1

Type RM Length L Ch R = 1 ,102603  ,480,480,480
BEGIN DESCRIPTION:
VATOSS GULLY 162.0
END DESCRIPTION:
XS GIS Cut Line= 3
      2300737.71     13376246.85      2300137.72     13375996.85
      2299837.74     13375946.86
#Sta/Elev= 30
  4331.1  397.28  4345.7  397.23  4406.9  394.78  4451.9  393.76  4515.3  391.41
  4552.6  390.71  4558.6  389.96  4569.4  390.05  4576.5  389.52  4591.1  389.33
  4600.3  389.88  4629.5  388.42  4730.3  386.31  4829.4  385.81  4860.3  386.16
  4867.1  385.77    4895  386.08  4971.9   385.8  4983.6  385.36  4988.2   382.8
    4991   382.3  4994.2   382.8    5009   385.2  5046.7  386.26  5082.5  388.18
  5191.4  391.77  5204.1  392.63  5257.3  393.75  5275.1  395.14  5285.2  395.24
#Mann= 5 ,-1 , 0
  4331.1      .1       0  4867.1     .12       0  4988.2     .07       0
  4994.2     .12       0  5046.7      .1       0
Bank Sta=4983.6,5009
XS Rating Curve= 0 ,0
Exp/Cntr=0.3,0.1

Type RM Length L Ch R = 1 ,102123  ,590,590,590
BEGIN DESCRIPTION:
VATOSS GULLY 161.0
END DESCRIPTION:
XS GIS Cut Line= 3
       2300837.7     13375646.85      2300237.72     13375546.85
      2299637.76     13375596.85
#Sta/Elev= 30
  4385.1  397.06    4456  394.99  4496.6  393.06    4527  392.33  4557.4  390.61
  4587.8  390.56  4595.4  389.34  4656.3  387.16  4777.9  383.68  4810.9  383.72
    4818  383.09  4820.8  382.59    4824  383.09    4871  383.43  4952.8  384.25
  4965.5  383.57  5003.4  383.27  5043.5  384.11  5126.6  386.24  5143.9  387.33
  5284.4  392.11  5291.9  392.86  5296.9  392.67  5364.6  396.04  5532.7  401.47
  5545.3  402.77  5555.3  402.77  5575.4  405.52  5585.4  404.03  5595.4  404.99
#Mann= 5 ,-1 , 0
  4385.1     .05       0    4818     .07       0    4824     .05       0
    4871     .12       0  5126.6      .1       0
Bank Sta=4952.8,5043.5
XS Rating Curve= 0 ,0
Exp/Cntr=0.3,0.1

Type RM Length L Ch R = 1 ,101533  ,346,346,346
BEGIN DESCRIPTION:
VATOSS GULLY 160.0
END DESCRIPTION:
XS GIS Cut Line= 3
      2301047.19      13375246.6        2300726.     13375029.58
      2299697.38     13375103.36
#Sta/Elev= 30
  4286.3  394.54  4299.3  393.84  4329.2  393.76  4350.2  392.58  4386.2  391.67
  4416.1  391.65  4469.8  390.14    4488     390  4502.9  389.01    4524  389.29
  4682.2  384.96  4762.4   384.6  4772.5  383.98  4832.6  383.38  4904.3  381.77
  4952.9  380.11    4963  380.76    4993  381.24  5000.1  379.81  5002.8  379.31
  5006.1  379.81  5023.1  381.39  5143.4  381.88  5260.2  383.58  5323.9  386.21
  5394.1  387.77  5504.3  392.26  5624.7  396.08  5634.7  397.11  5705.2  398.81
#Mann= 6 ,-1 , 0
  4286.3     .05       0  4469.8      .1       0  4904.3     .12       0
  5000.1     .07       0  5006.1     .12       0  5260.2      .1       0
Bank Sta=4993,5023.1
XS Rating Curve= 0 ,0
Exp/Cntr=0.3,0.1

Type RM Length L Ch R = 1 ,101187  ,400,400,400
BEGIN DESCRIPTION:
VATOSS GULLY 159.0
END DESCRIPTION:
XS GIS Cut Line= 3
      2301129.64     13374591.21      2300626.17     13374725.76
      2299641.81     13374998.95
#Sta/Elev= 30
  4155.9  392.08  4213.1  390.43  4240.9  389.26  4270.6  389.82  4282.1  388.53
  4315.8  388.05  4323.5  386.95  4385.6  386.52    4396  385.54  4489.1  384.86
  4520.2  383.79    4603  382.89  4853.3  381.32  4914.1  380.47  4986.8  381.31
  4997.7  378.62  5000.4  378.12  5003.7  378.62  5007.5  379.64  5059.4  379.88
  5090.5  381.17  5163.7  381.71  5391.5   388.7    5433  390.89    5443   390.6
  5561.3  395.17  5567.9  395.99  5578.3   395.7  5640.6  397.92  5698.6  400.73
#Mann= 6 ,-1 , 0
  4155.9     .05       0  4213.1      .1       0  4853.3     .12       0
  4997.7     .07       0  5003.7     .12       0  5163.7      .1       0
Bank Sta=4986.8,5090.5
XS Rating Curve= 0 ,0
Exp/Cntr=0.3,0.1

Type RM Length L Ch R = 1 ,100787  ,415,415,415
BEGIN DESCRIPTION:
VATOSS GULLY 158.0
END DESCRIPTION:
XS GIS Cut Line= 3
      2300987.73     13374346.85      2300187.72     13374446.85
      2299387.69     13374846.87
#Sta/Elev= 30
  4184.9  395.29  4235.3  392.83  4288.3  391.88  4380.4  388.94  4658.6  381.24
  4711.5  381.55  4729.1  380.47  4960.5  378.56  4993.9  379.17  5002.1  378.43
  5004.9  377.93  5008.1  378.43  5013.5  379.54  5095.8  378.76  5304.2  384.44
  5318.2  386.21  5334.9  386.27  5348.9  387.83  5362.9  386.89  5371.3   388.4
  5385.2  387.03  5428.9  388.85  5483.1  392.41  5515.1  393.12  5540.4  394.82
  5586.5  395.39  5594.9  396.85  5651.9  398.99  5777.8  403.35  5885.6  407.03
#Mann= 12 ,-1 , 0
  4184.9      .1       0  4288.3     .05       0  4380.4      .1       0
  4960.5     .12       0  5002.1     .07       0  5008.1     .12       0
  5095.8      .1       0  5428.9     .08       0  5515.1      .1       0
  5540.4     .08       0  5651.9     .05       0  5777.8      .1       0
Bank Sta=4993.9,5013.5
XS Rating Curve= 0 ,0
Exp/Cntr=0.3,0.1

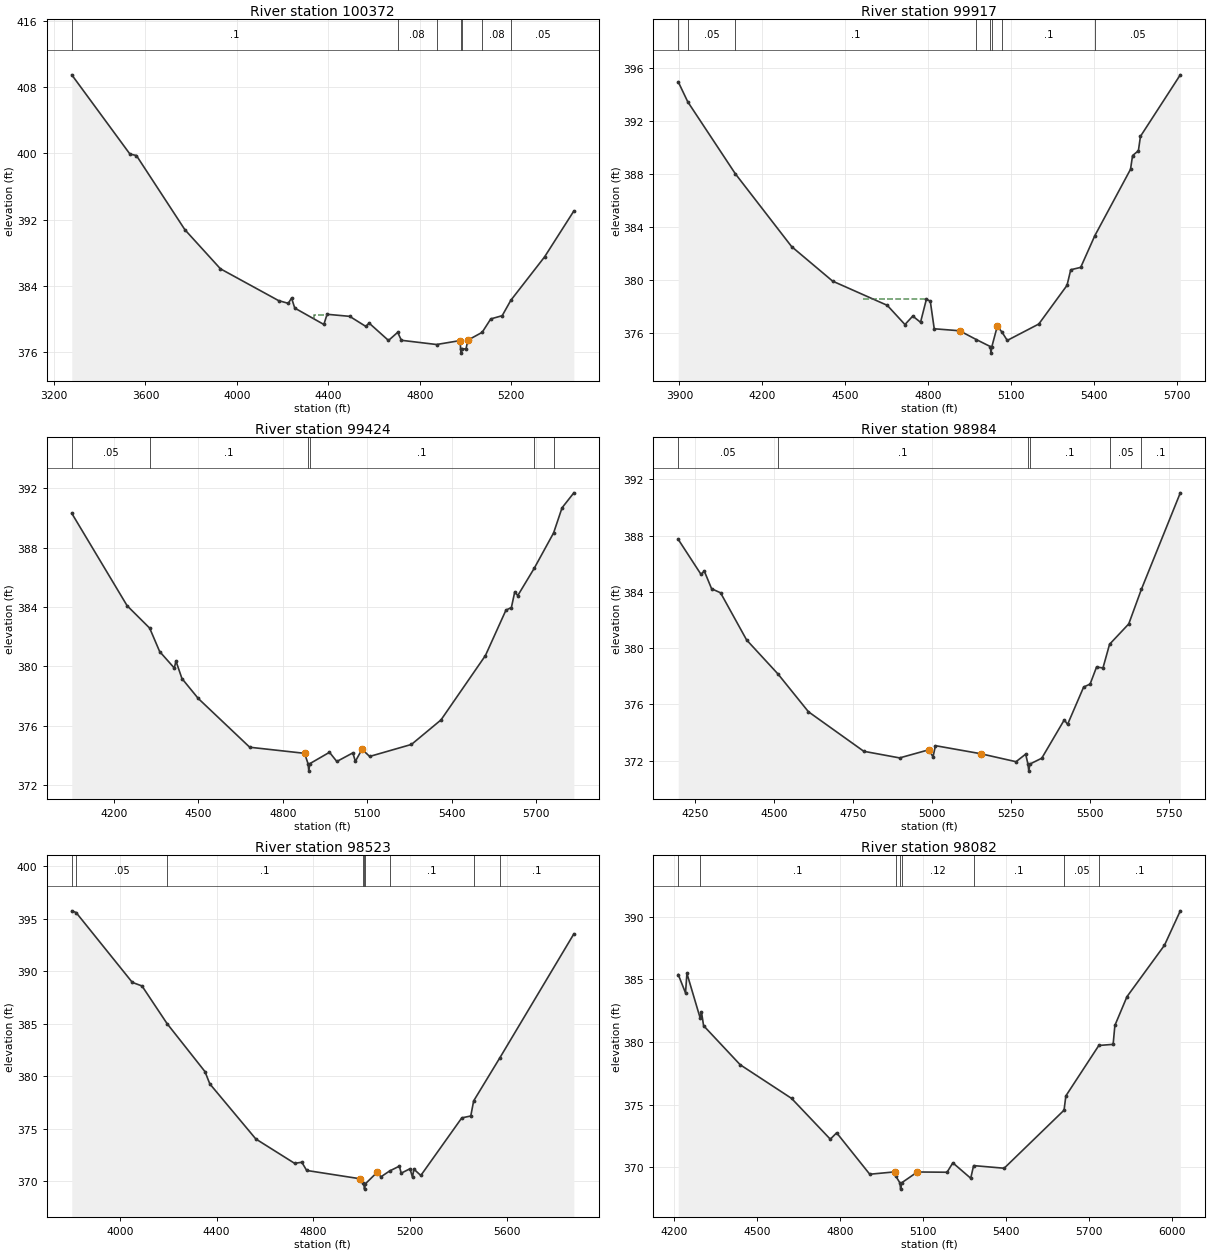
Type RM Length L Ch R = 1 ,100372  ,455,455,455
BEGIN DESCRIPTION:
VATOSS GULLY 157.0
END DESCRIPTION:
XS GIS Cut Line= 3
      2301187.74     13372896.84      2299987.72     13374096.85
       2299587.7     13374396.87
#Sta/Elev= 30
  3277.5  409.49  3532.1  399.92  3560.4  399.75  3772.5  390.79  3928.1  386.07
  4182.6  382.23    4225   381.9  4239.2  382.54  4253.3  381.33  4380.6  379.35
  4394.8  380.58  4493.7  380.33  4564.5  379.11  4578.6  379.52  4663.5  377.42
  4703.7   378.4    4720  377.44  4873.8  376.93  4977.7  377.41  4978.9  376.39
  4981.6  375.89  4984.9  376.39  5002.7   376.4    5011  377.46  5073.3   378.4
    5111  380.02    5161  380.41  5198.9  382.27  5346.5  387.51  5474.6  393.05
#Mann= 7 ,-1 , 0
  3277.5      .1       0  4703.7     .08       0  4873.8     .12       0
  4978.9     .07       0  4984.9     .12       0  5073.3     .08       0
  5198.9     .05       0
#XS Ineff= 1 ,-1
 4335.74 4393.76   380.5
Permanent Ineff=
       F
Bank Sta=4977.7,5011
XS Rating Curve= 0 ,0
Exp/Cntr=0.3,0.1

Type RM Length L Ch R = 1 ,99917   ,493,493,493
BEGIN DESCRIPTION:
VATOSS GULLY 156.0
END DESCRIPTION:
XS GIS Cut Line= 3
      2300637.69     13372946.89      2299837.72     13373696.85
      2299437.69      13374296.9
#Sta/Elev= 30
  3895.5  394.98    3930  393.47    4102  388.04    4306  382.53  4454.5  379.92
  4652.3  378.09  4716.3  376.64  4744.6  377.28  4772.7  376.81    4794  378.56
  4808.1   378.4  4822.3  376.32  4914.1  376.17  4975.1   375.5  5025.1  374.98
  5027.8  374.48  5031.1  374.98  5050.6  376.51  5067.9  376.06  5086.7  375.44
  5200.9  376.68    5303   379.6  5316.5  380.78  5352.6  380.96  5403.6  383.35
  5532.9  388.37  5540.4  389.41  5561.4  389.77  5568.9  390.86  5713.2  395.51
#Mann= 8 ,-1 , 0
  3895.5      .1       0    3930     .05       0    4102      .1       0
  4975.1     .12       0  5025.1     .07       0  5031.1     .12       0
  5067.9      .1       0  5403.6     .05       0
#XS Ineff= 1 ,-1
 4565.22 4793.64  378.56
Permanent Ineff=
       F
Bank Sta=4914.1,5050.6
XS Rating Curve= 0 ,0
Exp/Cntr=0.3,0.1

Type RM Length L Ch R = 1 ,99424   ,440,440,440
BEGIN DESCRIPTION:
VATOSS GULLY 155.0
END DESCRIPTION:
XS GIS Cut Line= 3
      2300387.75     13372846.84      2299587.72     13373346.85
      2299337.71     13374146.87
#Sta/Elev= 30
  4051.2  390.32  4247.6  384.09  4327.6  382.58  4363.1     381    4415  379.89
  4420.9  380.36  4442.2  379.18  4499.9  377.84  4682.7  374.55  4877.3  374.14
  4889.6  373.44  4892.4  372.94  4895.6  373.44  4965.7  374.21  4991.7  373.59
  5048.6  374.17  5057.5   373.6  5081.1  374.41  5108.3  373.93  5256.6  374.74
  5361.3  376.39    5519  380.73  5591.8  383.79  5611.2  383.97  5623.2  385.03
  5633.7  384.77  5692.4  386.62    5761     389  5790.9  390.69  5832.8   391.7
#Mann= 6 ,-1 , 0
  4051.2     .05       0  4327.6      .1       0  4889.6     .07       0
  4895.6      .1       0  5692.4     .05       0    5761      .1       0
Bank Sta=4877.3,5081.1
XS Rating Curve= 0 ,0
Exp/Cntr=0.3,0.1

Type RM Length L Ch R = 1 ,98984   ,461,461,461
BEGIN DESCRIPTION:
VATOSS GULLY 154.0
END DESCRIPTION:
XS GIS Cut Line= 3
       2300287.7     13372796.86      2299487.72     13372996.85
      2298737.68     13373146.86
#Sta/Elev= 30
  4195.7  387.73  4267.8  385.24  4278.1  385.48  4301.3  384.22  4329.7  383.93
  4412.1  380.58  4511.4  378.16    4608  375.47  4783.2  372.66  4896.6  372.19
  4989.4  372.77  5002.3  372.26    5010  373.06  5152.9  372.49  5265.1  371.92
  5295.7  372.46  5302.8  371.75  5305.6  371.25  5308.8  371.75  5346.6  372.17
    5418   374.9  5428.2  374.57  5479.2  377.23  5499.6  377.44    5520  378.65
  5540.4  378.59  5561.2  380.27    5622  381.72    5662  384.18  5785.2  391.04
#Mann= 6 ,-1 , 0
  4195.7     .05       0  4511.4      .1       0  5302.8     .07       0
  5308.8      .1       0  5561.2     .05       0    5662      .1       0
Bank Sta=4989.4,5152.9
XS Rating Curve= 0 ,0
Exp/Cntr=0.3,0.1

Type RM Length L Ch R = 1 ,98523   ,441,441,441
BEGIN DESCRIPTION:
VATOSS GULLY 153.0
END DESCRIPTION:
XS GIS Cut Line= 3
      2300587.76     13372596.85      2299387.72     13372596.85
      2298587.76     13372946.84
#Sta/Elev= 30
    3802  395.77  3819.8  395.61    4052  388.95    4092  388.61  4195.3  385.03
    4352  380.45    4372  379.28    4562  374.03    4722  371.71    4752  371.81
    4772  371.03    4992  370.24  5003.3  369.81    5008  369.75  5010.8  369.25
    5014  369.75  5063.2  370.86  5078.4  370.42  5114.5  370.98  5154.8  371.44
  5162.3  370.77  5198.5  371.19    5209  370.38  5214.5  371.16  5243.3  370.55
  5412.5  376.04  5449.6  376.22  5461.5  377.66  5570.1  381.78  5875.2  393.57
#Mann= 9 ,-1 , 0
    3802      .1       0  3819.8     .05       0  4195.3      .1       0
  5003.3     .12       0    5008     .07       0    5014     .12       0
  5114.5      .1       0  5461.5     .05       0  5570.1      .1       0
Bank Sta=4992,5063.2
XS Rating Curve= 0 ,0
Exp/Cntr=0.3,0.1

Type RM Length L Ch R = 1 ,98082   ,494,494,494
BEGIN DESCRIPTION:
VATOSS GULLY 152.0
END DESCRIPTION:
XS GIS Cut Line= 3
      2300237.72     13372346.86      2299437.72     13372196.85
      2298637.75     13372796.83
#Sta/Elev= 30
  4216.3  385.39  4242.6  383.92  4247.7  385.48  4295.7   381.9  4300.2  382.41
  4307.9   381.3  4440.1  378.18  4625.8  375.49  4765.7  372.23  4788.6  372.74
  4908.2  369.43  4998.9  369.62  5001.7   369.3  5017.1  368.74  5019.8  368.24
  5023.1  368.74  5080.2  369.61  5187.5  369.59  5208.4  370.34    5273  369.11
  5283.4  370.12  5393.8  369.91  5610.2  374.55  5616.7  375.69  5735.8  379.72
  5787.5  379.81  5793.8  381.32  5837.5  383.62    5973  387.73  6030.2  390.48
#Mann= 8 ,-1 , 0
  4216.3     .05       0  4295.7      .1       0  5001.7     .12       0
  5017.1     .07       0  5023.1     .12       0  5283.4      .1       0
  5610.2     .05       0  5735.8      .1       0
Bank Sta=4998.9,5080.2
XS Rating Curve= 0 ,0
Exp/Cntr=0.3,0.1

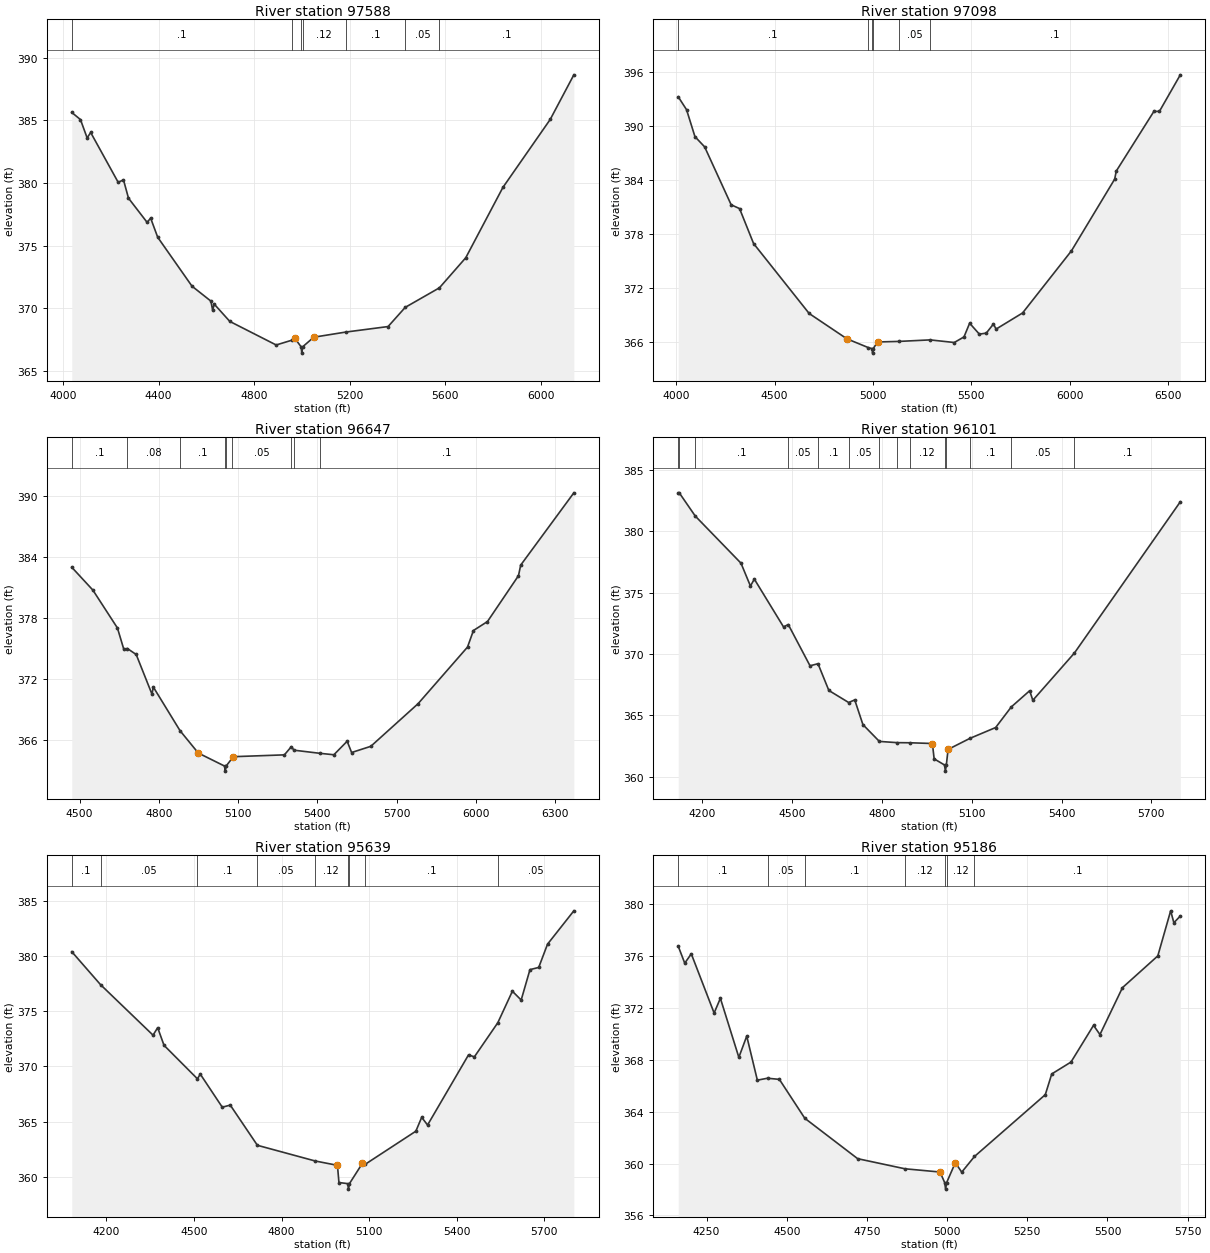
Type RM Length L Ch R = 1 ,97588   ,490,490,490
BEGIN DESCRIPTION:
VATOSS GULLY 151.0
END DESCRIPTION:
XS GIS Cut Line= 3
      2300087.74     13371246.84      2299287.72     13371796.85
      2298487.73     13372596.84
#Sta/Elev= 30
  4036.7  385.62  4073.1  385.05    4101  383.59  4115.9  384.02  4230.9  380.05
  4253.2  380.24  4274.2  378.78  4352.2  376.85  4366.9  377.19  4396.6  375.66
  4540.1  371.76  4619.2  370.57  4626.7  369.83  4632.7  370.34  4698.4  368.95
  4892.5  367.07  4959.8  367.46  4971.1  367.59  4997.1  366.92  4999.8  366.42
  5003.1  366.92    5050  367.69  5183.8   368.1  5361.1  368.54  5432.9  370.07
  5576.1  371.63  5686.4  374.03  5841.9  379.64  6039.9  385.06  6138.9  388.62
#Mann= 7 ,-1 , 0
  4036.7      .1       0  4959.8     .12       0  4997.1     .07       0
  5003.1     .12       0  5183.8      .1       0  5432.9     .05       0
  5576.1      .1       0
Bank Sta=4971.1,5050
XS Rating Curve= 0 ,0
Exp/Cntr=0.3,0.1

Type RM Length L Ch R = 1 ,97098   ,451,451,451
BEGIN DESCRIPTION:
VATOSS GULLY 150.0
END DESCRIPTION:
XS GIS Cut Line= 3
      2299737.73     13370646.85      2299087.72     13371396.85
      2298087.74     13372596.83
#Sta/Elev= 30
  4009.3  393.23  4051.6   391.8  4094.3  388.81  4143.7  387.67  4278.6  381.24
  4321.3  380.82  4392.6  376.94  4675.5  369.17  4867.4  366.36  4975.7  365.39
  4995.5  365.27  4998.2  364.77  5001.5  365.27  5023.3  366.01  5131.6  366.07
  5290.6  366.24  5413.8  365.95  5463.2  366.57  5491.9  368.09  5541.3  366.88
  5576.5  366.99  5612.9     368  5626.6  367.44  5761.3  369.23    6010  376.13
  6229.9  384.09  6237.8  384.98  6429.1   391.6  6457.7  391.62  6563.8  395.67
#Mann= 6 ,-1 , 0
  4009.3      .1       0  4975.7     .12       0  4995.5     .07       0
  5001.5     .12       0  5131.6     .05       0  5290.6      .1       0
Bank Sta=4867.4,5023.3
XS Rating Curve= 0 ,0
Exp/Cntr=0.3,0.1

Type RM Length L Ch R = 1 ,96647   ,546,546,546
BEGIN DESCRIPTION:
VATOSS GULLY 149.0
END DESCRIPTION:
XS GIS Cut Line= 3
      2298837.71     13370696.89      2298737.72     13371246.85
      2298137.73     13372446.84
#Sta/Elev= 30
  4470.4  382.96  4550.4  380.71  4643.2  376.99  4667.3   374.9  4680.7  374.97
  4714.3  374.38    4774  370.48  4779.1  371.18  4880.2  366.89  4949.3  364.69
  5048.7  363.41  5051.5  362.91  5054.7  363.41  5077.9  364.19  5082.5  364.33
  5275.3  364.51  5301.7  365.32  5311.4  364.97  5410.4  364.66  5462.6  364.52
  5512.9  365.85  5529.7  364.74  5602.4  365.35  5781.3  369.54  5968.5  375.11
  5990.9  376.74    6044  377.62  6161.4  382.13  6169.8  383.17    6371  390.28
#Mann= 9 ,-1 , 0
  4470.4      .1       0  4680.7     .08       0  4880.2      .1       0
  5048.7     .07       0  5054.7      .1       0  5077.9     .05       0
  5301.7      .1       0  5311.4     .05       0  5410.4      .1       0
Bank Sta=4949.3,5082.5
XS Rating Curve= 0 ,0
Exp/Cntr=0.3,0.1

Type RM Length L Ch R = 1 ,96101   ,462,462,462
BEGIN DESCRIPTION:
VATOSS GULLY 148.0
END DESCRIPTION:
XS GIS Cut Line= 3
      2298637.72     13370646.85      2298387.72     13371446.85
      2298137.72     13372246.84
#Sta/Elev= 30
  4120.2  383.12  4123.9  383.11    4177  381.23  4329.7  377.39  4361.2  375.53
  4374.3  376.09  4471.7   372.2  4487.6  372.39  4560.2  369.03  4586.8   369.2
  4623.1  367.02  4689.2  366.04  4709.5  366.25  4736.8  364.24  4791.7  362.87
  4851.2  362.77  4894.1  362.76  4968.8   362.7  4974.6  361.45  5009.3  360.95
  5012.1  360.45  5015.3  360.95  5021.2  362.22  5094.2  363.12  5179.9     364
  5232.2  365.68  5293.6     367  5304.1  366.22  5442.9  370.07  5796.5  382.39
#Mann= 14 ,-1 , 0
  4120.2      .1       0  4123.9     .05       0    4177      .1       0
  4487.6     .05       0  4586.8      .1       0  4689.2     .05       0
  4791.7     .12       0  4851.2     .05       0  4894.1     .12       0
  5009.3     .07       0  5015.3     .12       0  5094.2      .1       0
  5232.2     .05       0  5442.9      .1       0
Bank Sta=4968.8,5021.2
XS Rating Curve= 0 ,0
Exp/Cntr=0.3,0.1

Type RM Length L Ch R = 1 ,95639   ,453,453,453
BEGIN DESCRIPTION:
VATOSS GULLY 147.0
END DESCRIPTION:
XS GIS Cut Line= 3
      2298387.73     13370646.84      2297937.72     13371446.85
      2297887.72      13372246.9
#Sta/Elev= 30
  4081.5  380.42  4179.9  377.43  4359.8  372.84  4375.7  373.52  4397.4  371.92
  4511.7  368.88  4521.7   369.3  4596.9   366.3  4624.3  366.49  4717.2  362.84
  4914.5  361.42  4991.4  361.02  4996.5  359.46  5026.5  359.36  5029.2  358.86
  5032.5  359.36    5077  361.21  5087.3  361.13  5259.9  364.12  5279.9  365.38
    5300  364.68  5440.3  371.05  5460.3  370.87  5540.6  373.97  5590.5  376.83
  5620.6  376.03  5650.7  378.79  5680.7  378.99  5710.8   381.1    5801  384.13
#Mann= 9 ,-1 , 0
  4081.5      .1       0  4179.9     .05       0  4511.7      .1       0
  4717.2     .05       0  4914.5     .12       0  5026.5     .07       0
  5032.5     .12       0  5087.3      .1       0  5540.6     .05       0
Bank Sta=4991.4,5077
XS Rating Curve= 0 ,0
Exp/Cntr=0.3,0.1

Type RM Length L Ch R = 1 ,95186   ,604,604,604
BEGIN DESCRIPTION:
VATOSS GULLY 146.0
END DESCRIPTION:
XS GIS Cut Line= 3
      2297687.71      13370496.9      2297537.72     13371296.85
      2297487.72     13372046.89
#Sta/Elev= 30
  4161.5  376.78  4181.8  375.47  4202.2  376.19  4273.4  371.62  4292.9  372.76
  4350.5   368.2  4375.1  369.84  4408.2  366.44  4439.9  366.59  4476.9   366.5
  4556.1   363.5    4721  360.38  4868.5   359.6  4977.9  359.35  4992.4  358.53
  4995.2  358.03  4998.4  358.53  5025.5  360.07  5045.5  359.34  5085.3  360.55
  5306.1  365.32  5326.2  366.92  5386.3  367.84  5456.5  370.67  5476.5  369.96
  5546.7  373.58  5656.9  376.03    5697  379.51    5707  378.59  5727.1  379.11
#Mann= 7 ,-1 , 0
  4161.5      .1       0  4439.9     .05       0  4556.1      .1       0
  4868.5     .12       0  4992.4     .07       0  4998.4     .12       0
  5085.3      .1       0
Bank Sta=4977.9,5025.5
XS Rating Curve= 0 ,0
Exp/Cntr=0.3,0.1