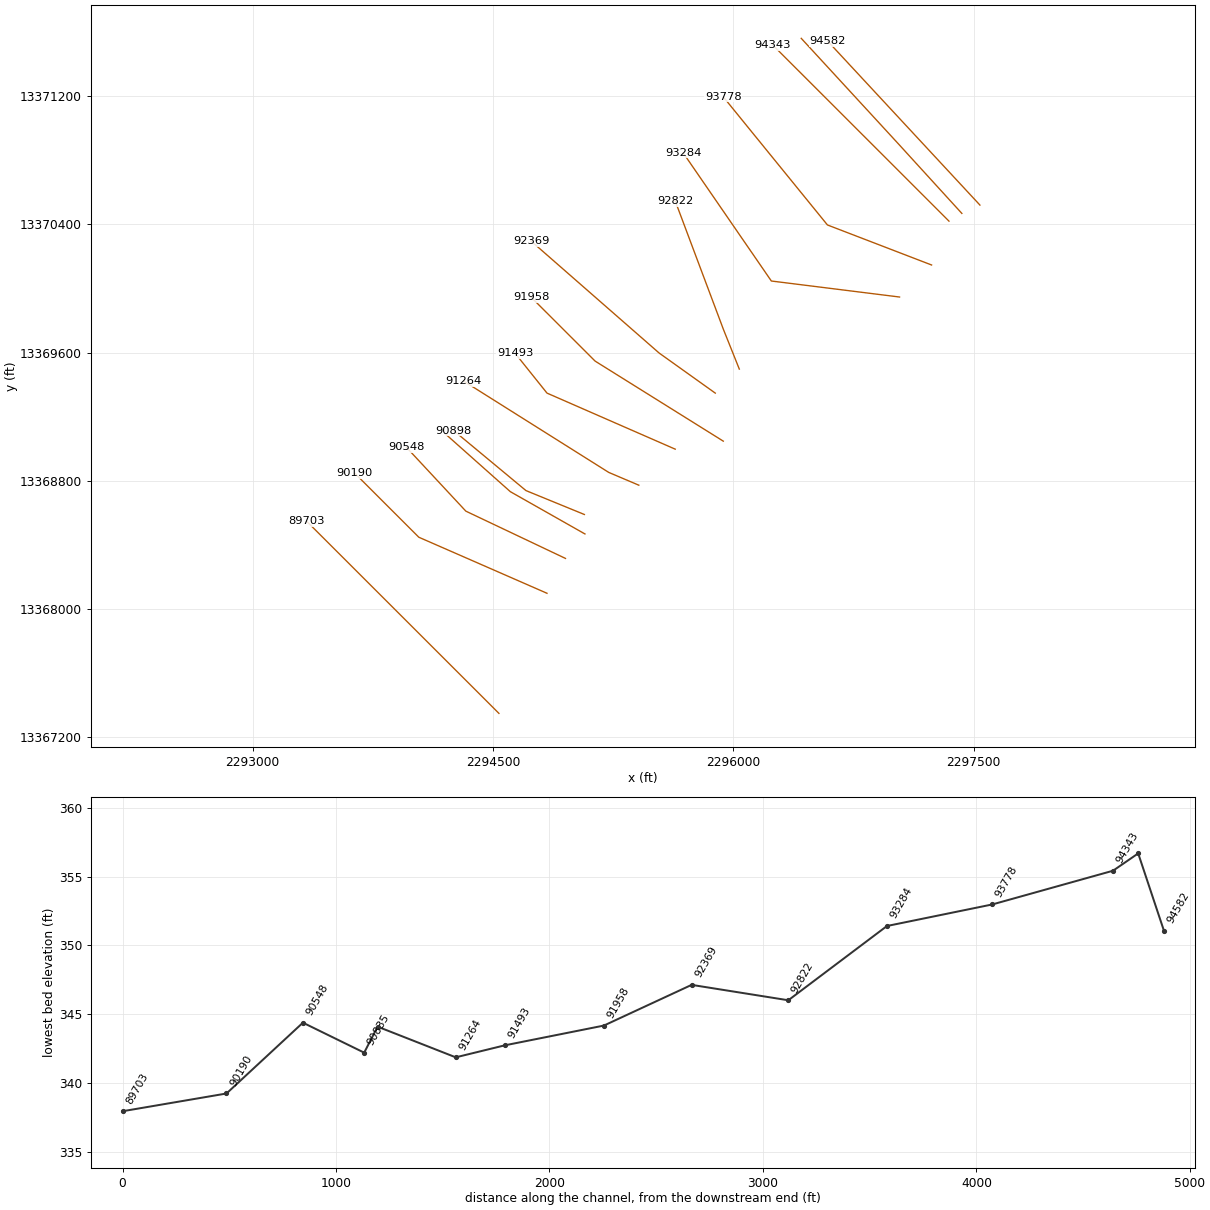
HEC-RAS study VATOSS GULLY.prj: VATOSS GULLY Base Level Engineering

--- VATOSS GULLY.g01 (geometry) --- (continued)

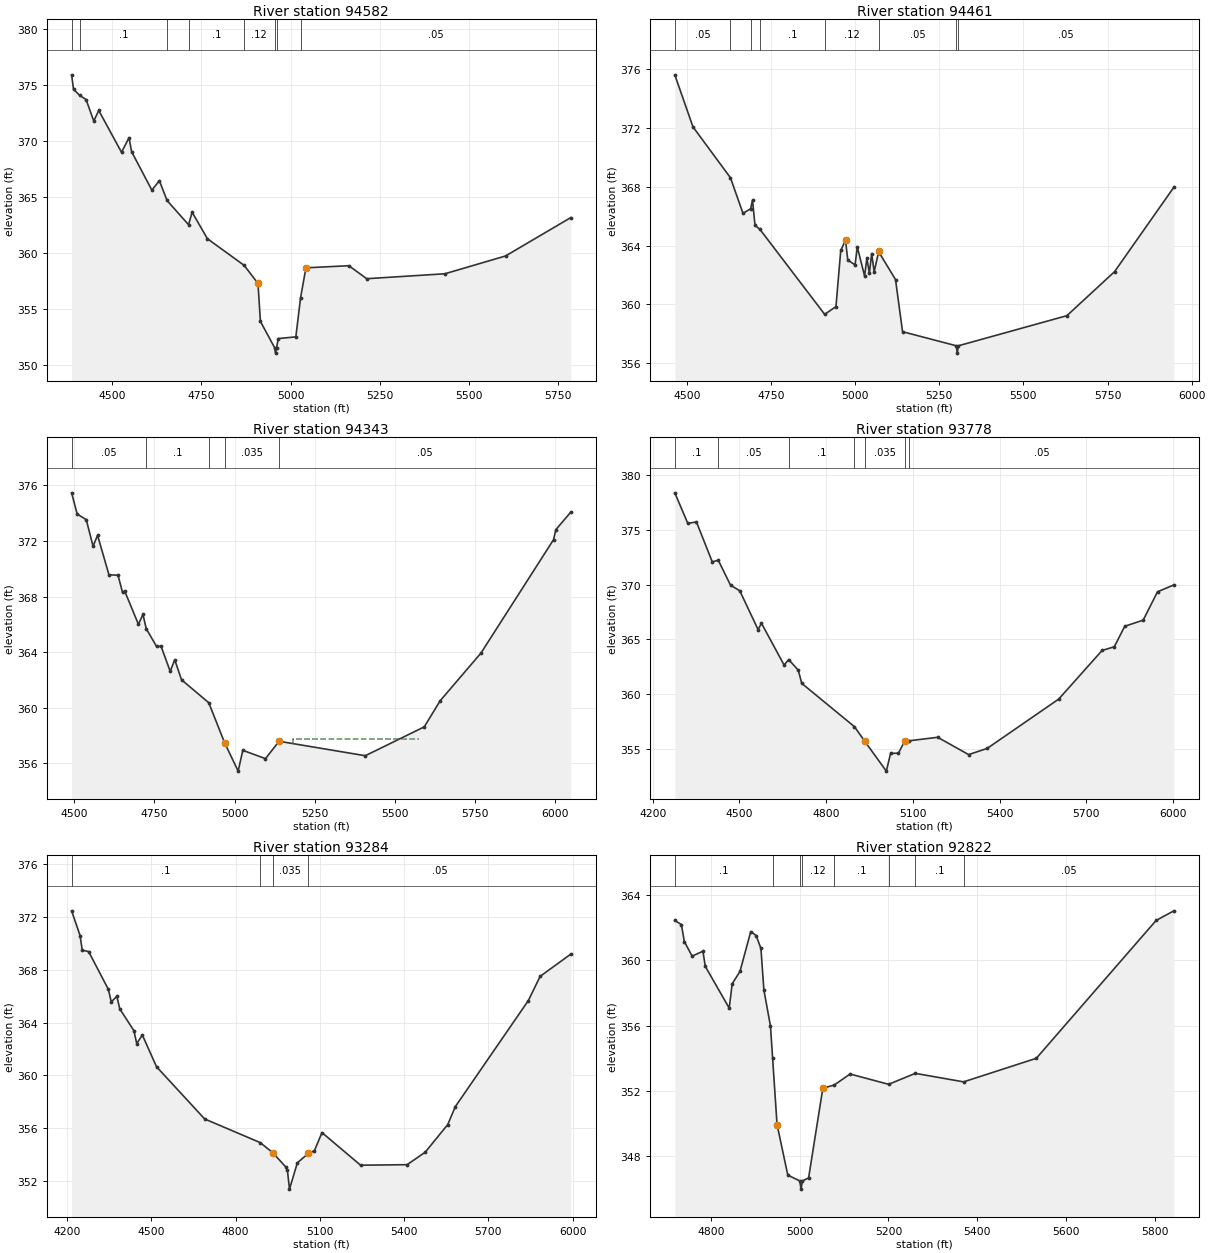
Type RM Length L Ch R = 1 ,94582   ,121,121,121
BEGIN DESCRIPTION:
Mapping XS a90cad22
END DESCRIPTION:
XS GIS Cut Line= 2
      2297539.25     13370521.13      2296588.72     13371545.44
#Sta/Elev= 30
    4387  375.87  4392.3  374.58  4409.1  374.05  4427.5  373.66    4449  371.75
    4463  372.69  4526.7  368.96  4547.7  370.26    4555  369.01  4611.7  365.58
  4632.7  366.43  4654.1  364.66  4714.3   362.5  4724.5  363.61  4767.1  361.25
  4870.1  358.87  4908.8  357.26  4915.6  353.87  4955.1  351.54  4957.9  351.04
  4961.1  351.54  4965.5  352.34  5014.8  352.49  5028.1     356  5043.1  358.65
  5163.3  358.84  5213.2  357.68  5432.1  358.12  5602.1  359.71  5784.4  363.13
#Mann= 8 ,-1 , 0
    4387     .05       0  4409.1      .1       0  4654.1     .05       0
  4714.3      .1       0  4870.1     .12       0  4955.1     .07       0
  4961.1     .12       0  5028.1     .05       0
#XS Ineff= 1 ,-1
 5163.75    5540  358.82
Permanent Ineff=
       F
Bank Sta=4908.8,5043.1
XS Rating Curve= 0 ,0
Exp/Cntr=0.3,0.1

Type RM Length L Ch R = 1 ,94461   ,118,118,118
BEGIN DESCRIPTION:
VATOSS GULLY 145.0
END DESCRIPTION:
XS GIS Cut Line= 3
      2297426.38     13370469.07      2297022.76     13370911.75
      2296424.21     13371562.34
#Sta/Elev= 30
  4464.1  375.63    4518  372.09  4629.5  368.62  4666.7   366.2  4689.4  366.51
    4695   367.1  4702.5  365.38    4717  365.11  4909.5  359.32    4943  359.85
  4957.2  363.67  4971.4  364.37  4978.1  363.02  4999.7  362.69  5006.5   363.9
  5028.1  361.93  5034.9  363.16  5042.3  362.11  5049.1  363.46  5056.5  362.21
  5070.1  363.62  5071.3  363.53    5120  361.69  5140.9  358.14  5300.7  357.18
  5303.5  356.68  5306.7  357.18  5629.2  359.23    5771  362.23  5947.2  367.98
#Mann= 8 ,-1 , 0
  4464.1     .05       0  4629.5      .1       0  4689.4     .05       0
    4717      .1       0  4909.5     .12       0  5071.3     .05       0
  5300.7     .07       0  5306.7     .05       0
#XS Ineff= 1 ,-1
  5132.5 5588.75  358.47
Permanent Ineff=
       F
Bank Sta=4971.4,5070.1
XS Rating Curve= 0 ,0
Exp/Cntr=0.3,0.1

Type RM Length L Ch R = 1 ,94343   ,565,565,565
BEGIN DESCRIPTION:
VATOSS GULLY 144.0
END DESCRIPTION:
XS GIS Cut Line= 3
      2297346.19     13370420.85      2297046.23     13370720.81
      2296246.22     13371520.82
#Sta/Elev= 30
  4492.1  375.47  4509.4  373.94  4537.7  373.54  4558.9  371.62    4573  372.41
  4608.4  369.57  4636.7  369.53  4650.8   368.3  4657.9  368.37  4700.3     366
  4714.5  366.71  4724.7  365.68  4756.9   364.4    4771  364.41  4799.3  362.61
  4813.5  363.44  4834.7     362  4919.5  360.35    4969  357.46  5011.2  355.42
  5025.6  356.92  5096.3  356.32  5138.7  357.57  5407.4  356.53  5591.3  358.61
  5640.8  360.49  5768.1  363.93  5994.3   372.1  6001.4  372.82  6047.7  374.07
#Mann= 5 ,-1 , 0
  4492.1     .05       0  4724.7      .1       0  4919.5     .07       0
    4969    .035       0  5138.7     .05       0
#XS Ineff= 1 ,-1
 5183.28 5574.22  357.71
Permanent Ineff=
       F
Bank Sta=4969,5138.7
XS Rating Curve= 0 ,0
Exp/Cntr=0.3,0.1

Type RM Length L Ch R = 1 ,93778   ,494,494,494
BEGIN DESCRIPTION:
VATOSS GULLY 143.0
END DESCRIPTION:
XS GIS Cut Line= 3
      2297237.67     13370146.87      2296587.72     13370396.85
      2295937.75     13371196.82
#Sta/Elev= 30
  4276.2  378.39  4321.2   375.6  4351.1  375.73  4405.8  372.09  4426.7  372.23
    4469  369.96  4501.1  369.44  4564.4   365.9  4576.1  366.48  4654.4  362.66
  4670.2  363.16  4703.6  362.19  4715.4  360.99  4897.9  357.03  4932.9  355.72
  5008.2  352.97  5022.9  354.59  5050.1  354.61  5072.4  355.74  5086.6  355.74
  5185.9  356.06    5293  354.48  5356.9  355.04  5604.7  359.55  5754.8  363.99
  5797.2  364.33  5833.1   366.2    5897  366.76  5946.6  369.35  6003.3  369.98
#Mann= 7 ,-1 , 0
  4276.2      .1       0  4426.7     .05       0  4670.2      .1       0
  4897.9     .07       0  4932.9    .035       0  5072.4     .07       0
  5086.6     .05       0
#XS Ineff= 1 ,-1
 5180.41 5427.28355.8421
Permanent Ineff=
       F
Bank Sta=4932.9,5072.4
XS Rating Curve= 0 ,0
Exp/Cntr=0.3,0.1

Type RM Length L Ch R = 1 ,93284   ,462,462,462
BEGIN DESCRIPTION:
VATOSS GULLY 142.0
END DESCRIPTION:
XS GIS Cut Line= 3
      2297037.71     13369946.86      2296237.72     13370046.85
      2295687.74     13370846.82
#Sta/Elev= 30
  4216.5  372.46  4246.7  370.58  4254.3  369.48    4277  369.38  4347.5  366.51
  4357.6  365.57  4377.7  365.99  4387.8  365.05  4438.2  363.39  4448.3  362.42
  4468.4  363.06  4518.8  360.66  4690.2  356.71    4888  354.92    4932  354.17
  4979.9  353.06  4984.9  352.82  4992.2   351.4  5020.2  353.39  5059.1   354.1
  5080.9   354.3  5107.9  355.68  5245.3  353.21    5411  353.25  5475.3  354.19
  5555.8  356.29  5582.9  357.65  5842.7  365.67  5884.6   367.5  5993.5  369.18
#Mann= 4 ,-1 , 0
  4216.5      .1       0    4888     .07       0    4932    .035       0
  5059.1     .05       0
#XS Ineff= 1 ,-1
 5102.21  5553.7354.9804
Permanent Ineff=
       F
Bank Sta=4932,5059.1
XS Rating Curve= 0 ,0
Exp/Cntr=0.3,0.1

Type RM Length L Ch R = 1 ,92822   ,453,453,453
BEGIN DESCRIPTION:
VATOSS GULLY 141.0
END DESCRIPTION:
XS GIS Cut Line= 3
      2296037.72     13369496.86      2295937.72     13369746.85
       2295637.7      13370546.9
#Sta/Elev= 30
    4719  362.43  4733.8  362.18  4740.5  361.14    4758  360.25  4782.3  360.55
  4787.7  359.62  4841.5  357.07  4848.2  358.56  4865.7  359.31    4890  361.75
  4902.1  361.51  4912.9  360.72  4919.6  358.18  4934.4  355.97  4939.2  354.02
  4949.2  349.95  4973.4  346.86  5000.4   346.5  5003.1     346  5006.4   346.5
  5020.3  346.69  5052.3  352.17  5078.1  352.37  5113.7  353.04  5200.4  352.41
  5260.6  353.08  5369.2  352.56  5532.9     354  5802.6  362.43  5842.7  363.02
#Mann= 8 ,-1 , 0
    4719      .1       0  4939.2     .12       0  5000.4     .07       0
  5006.4     .12       0  5078.1      .1       0  5200.4     .12       0
  5260.6      .1       0  5369.2     .05       0
#XS Ineff= 1 ,-1
 5114.61 5484.43352.9075
Permanent Ineff=
       F
Bank Sta=4949.2,5052.3
XS Rating Curve= 0 ,0
Exp/Cntr=0.3,0.1

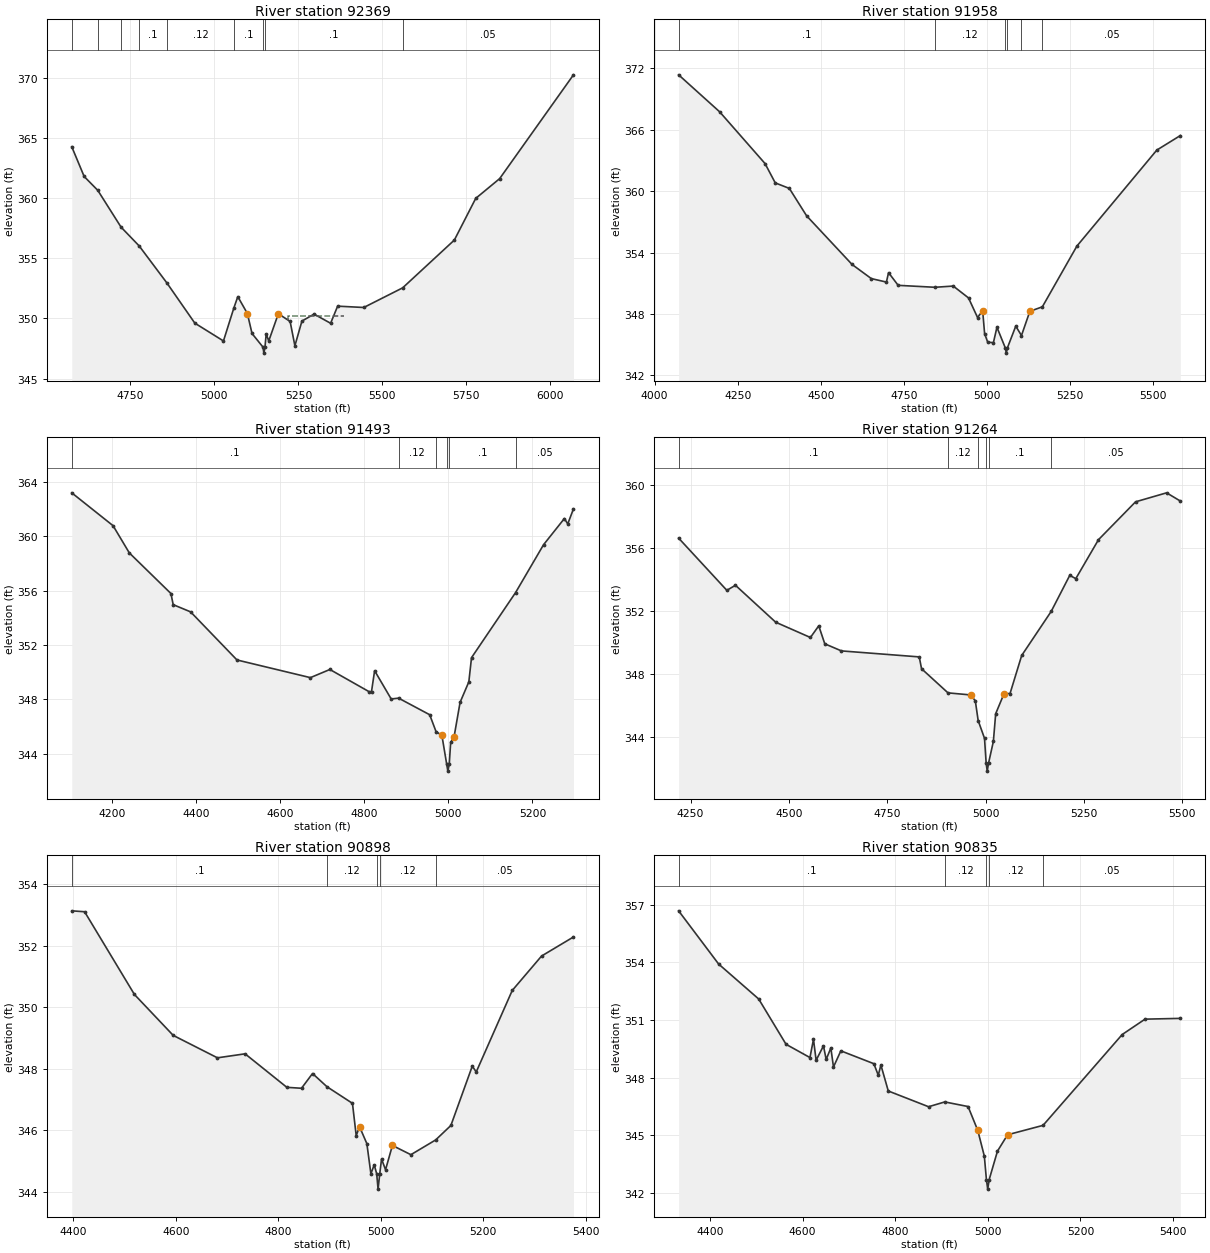
Type RM Length L Ch R = 1 ,92369   ,411,411,411
BEGIN DESCRIPTION:
VATOSS GULLY 140.0
END DESCRIPTION:
XS GIS Cut Line= 3
      2295887.76     13369346.83      2295537.72     13369596.85
       2294737.7     13370296.87
#Sta/Elev= 30
  4575.5  364.26  4612.4  361.79  4652.9  360.64  4722.3  357.58  4776.2  356.02
  4858.6  352.95  4941.8  349.61    5027  348.13  5058.2  350.89  5069.7  351.81
  5098.2  350.41    5112  348.75  5144.6  347.62  5147.3  347.12  5150.6  347.62
  5154.2  348.72  5161.8  348.13  5190.3  350.39  5225.4  349.75  5239.6  347.73
  5260.5  349.78  5296.6  350.36  5345.9   349.6  5366.8  351.02  5444.6  350.91
  5560.3  352.54  5714.2  356.51  5777.8  359.97    5849  361.61  6068.7  370.23
#Mann= 9 ,-1 , 0
  4575.5     .05       0  4652.9      .1       0  4722.3     .05       0
  4776.2      .1       0  4858.6     .12       0  5058.2      .1       0
  5144.6     .07       0  5150.6      .1       0  5560.3     .05       0
#XS Ineff= 1 ,-1
 5218.44 5385.78  350.23
Permanent Ineff=
       F
Bank Sta=5098.2,5190.3
XS Rating Curve= 0 ,0
Exp/Cntr=0.3,0.1

Type RM Length L Ch R = 1 ,91958   ,465,465,465
BEGIN DESCRIPTION:
VATOSS GULLY 139.0
END DESCRIPTION:
XS GIS Cut Line= 3
      2295937.72     13369046.86      2295137.72     13369546.85
      2294737.71     13369946.87
#Sta/Elev= 30
    4072  371.38  4195.2  367.77    4332   362.7  4362.7  360.81  4405.1  360.27
    4457  357.59  4593.8  352.83  4651.6  351.45    4697  351.11  4703.5  352.03
  4732.4  350.79  4843.2   350.6  4898.1  350.72    4944  349.56  4971.2  347.64
  4986.5  348.32  4992.4  346.07  5001.8  345.22  5018.9  345.19  5029.5  346.69
  5054.8  344.66  5057.6  344.16  5060.8  344.66  5086.1   346.8  5103.3  345.88
  5128.5  348.25  5166.1  348.69    5270  354.63  5510.4  364.02  5581.1  365.44
#Mann= 6 ,-1 , 0
    4072      .1       0  4843.2     .12       0  5054.8     .07       0
  5060.8     .12       0  5103.3      .1       0  5166.1     .05       0
Bank Sta=4986.5,5128.5
XS Rating Curve= 0 ,0
Exp/Cntr=0.3,0.1

Type RM Length L Ch R = 1 ,91493   ,229,229,229
BEGIN DESCRIPTION:
VATOSS GULLY 138.0
END DESCRIPTION:
XS GIS Cut Line= 3
      2295637.75     13368996.84      2294837.72     13369346.85
      2294637.72     13369596.85
#Sta/Elev= 30
  4104.2   363.2  4202.5  360.78  4241.1  358.78  4340.1  355.79  4345.5  354.97
  4386.9  354.44  4497.2   350.9  4671.8   349.6  4718.2   350.2  4811.8  348.56
  4817.2  348.57  4824.6  350.11    4864  348.03  4881.7  348.09  4955.6  346.87
  4970.8  345.62  4984.6  345.36  4996.1  343.22  4998.8  342.72  5002.1  343.22
  5005.5  344.83  5013.5  345.23  5027.9  347.78  5048.7  349.29  5055.1  351.07
  5159.9  355.86  5226.4  359.38    5276  361.31    5284  360.91  5297.6  362.02
#Mann= 6 ,-1 , 0
  4104.2      .1       0  4881.7     .12       0  4970.8      .1       0
  4996.1     .07       0  5002.1      .1       0  5159.9     .05       0
Bank Sta=4984.6,5013.5
XS Rating Curve= 0 ,0
Exp/Cntr=0.3,0.1

Type RM Length L Ch R = 1 ,91264   ,366,366,366
BEGIN DESCRIPTION:
Mapping XS b83a0242
END DESCRIPTION:
XS GIS Cut Line= 3
      2295410.65     13368771.79      2295222.77     13368851.74
      2294316.57      13369422.6
#Sta/Elev= 30
  4219.5  356.62  4342.1  353.31    4364  353.63  4466.2  351.29  4554.5  350.32
  4575.7  351.06    4591  349.92  4633.4  349.47  4831.1  349.09    4837  348.34
  4904.2  346.81  4961.5  346.68  4973.6  346.31  4980.9  345.05    4997  343.93
  5001.2  342.35  5003.9  341.85  5007.2  342.35  5019.5  343.73  5025.4  345.49
  5046.6  346.76  5061.9  346.77  5091.5  349.18  5166.4  351.97  5213.7  354.26
    5229  354.05  5286.7  356.52  5380.9  358.92  5459.8  359.49  5494.7  358.97
#Mann= 6 ,-1 , 0
  4219.5      .1       0  4904.2     .12       0  4980.9      .1       0
  5001.2     .07       0  5007.2      .1       0  5166.4     .05       0
Bank Sta=4961.5,5046.6
XS Rating Curve= 0 ,0
Exp/Cntr=0.3,0.1

Type RM Length L Ch R = 1 ,90898   ,63,63,63
BEGIN DESCRIPTION:
Mapping XS fe43f68f
END DESCRIPTION:
XS GIS Cut Line= 3
      2295070.96     13368588.82      2294706.35     13368738.14
      2294255.76     13369112.48
#Sta/Elev= 30
  4396.6  353.13  4421.7   353.1    4519  350.41  4594.7  349.08  4681.1  348.35
  4735.1  348.48  4816.7  347.39  4845.3  347.36  4866.8  347.84    4895  347.41
  4944.8  346.87  4952.1  345.82  4958.6  346.11  4972.9  345.56  4980.8  344.58
  4987.3  344.87  4992.1  344.58  4994.8  344.08  4998.1  344.58  5001.6  345.06
  5009.4  344.71  5022.8   345.5  5058.9   345.2  5107.3  345.68    5137  346.15
  5178.8  348.08  5186.5  347.89  5256.8  350.54  5314.1  351.66  5376.4  352.28
#Mann= 5 ,-1 , 0
  4396.6      .1       0    4895     .12       0  4992.1     .07       0
  4998.1     .12       0  5107.3     .05       0
Bank Sta=4958.6,5022.8
XS Rating Curve= 0 ,0
Exp/Cntr=0.3,0.1

Type RM Length L Ch R = 1 ,90835   ,287,287,287
BEGIN DESCRIPTION:
Mapping XS a0674459
END DESCRIPTION:
XS GIS Cut Line= 3
       2295074.4     13368467.31      2294609.13     13368731.19
      2294199.44     13369095.75
#Sta/Elev= 30
  4332.4  356.68  4418.8  353.91  4505.3  352.09  4564.4  349.73    4616  349.04
  4623.6  349.99  4629.3   348.9  4645.2  349.65    4651  348.94  4661.1  349.54
  4666.8  348.55  4682.7  349.39    4754  348.72  4763.5  348.12  4769.2  348.65
  4785.1   347.3  4872.1  346.48  4907.1  346.73  4957.4  346.49  4978.3  345.25
  4992.5  343.91    4997  342.69  4999.8  342.19    5003  342.69  5020.9  344.17
  5042.7  345.02  5119.3  345.51  5290.2  350.24  5339.5  351.04  5415.7  351.08
#Mann= 5 ,-1 , 0
  4332.4      .1       0  4907.1     .12       0    4997     .07       0
    5003     .12       0  5119.3     .05       0
Bank Sta=4978.3,5042.7
XS Rating Curve= 0 ,0
Exp/Cntr=0.3,0.1

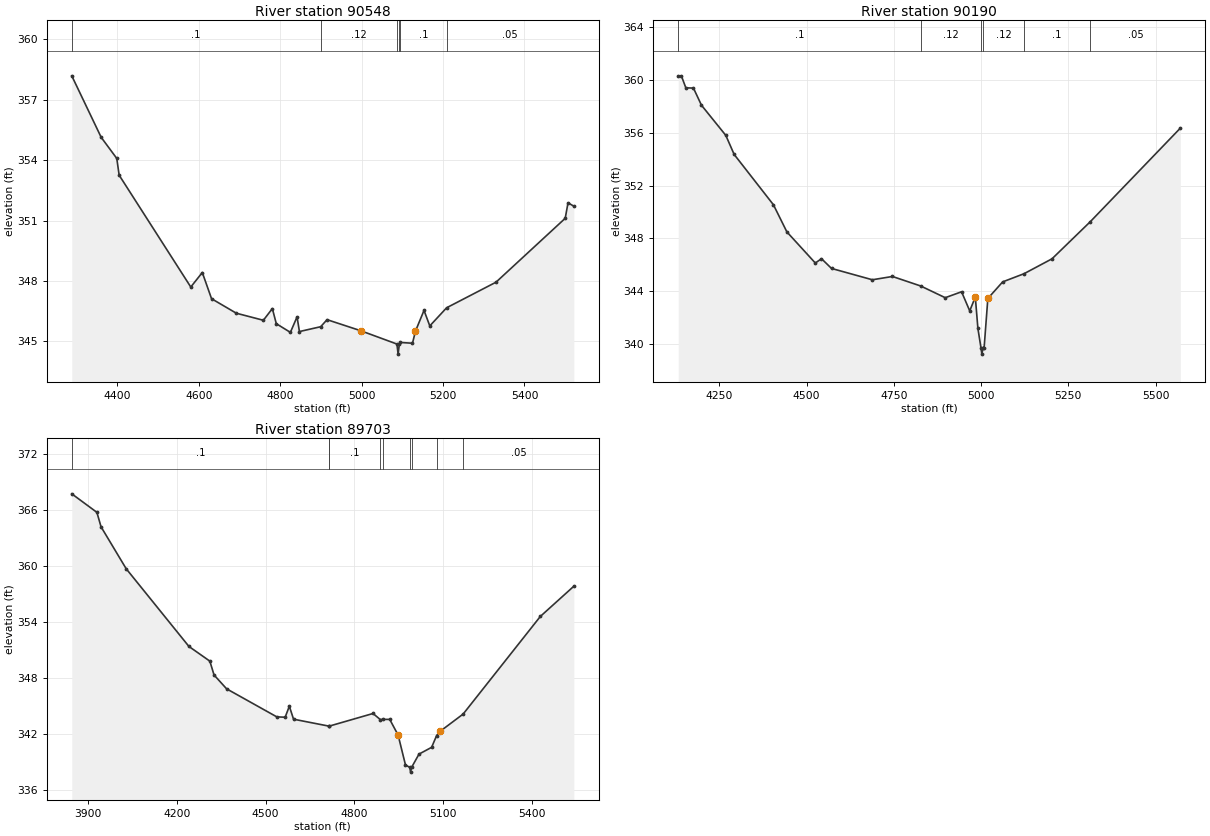
Type RM Length L Ch R = 1 ,90548   ,358,358,358
BEGIN DESCRIPTION:
Mapping XS 10592d67
END DESCRIPTION:
XS GIS Cut Line= 3
      2294952.91     13368314.52      2294331.35     13368609.67
      2293959.82     13369008.98
#Sta/Elev= 30
  4287.8  358.18    4360  355.13  4398.4  354.08  4404.2  353.25  4580.2   347.7
  4608.5  348.42  4631.2  347.12  4692.1   346.4  4758.5  346.05  4780.6  346.63
  4790.3  345.88  4824.9  345.45  4841.3  346.22  4847.1  345.49  4899.3  345.73
    4915  346.08  4997.9  345.53  5086.7  344.87  5089.5  344.37  5092.7  344.87
  5094.2  344.95  5124.9  344.91  5132.2  345.51  5153.2  346.54  5167.4  345.77
  5208.7  346.67  5330.1  347.94  5500.1  351.11    5507  351.88  5521.3  351.71
#Mann= 6 ,-1 , 0
  4287.8      .1       0  4899.3     .12       0  5086.7     .07       0
  5092.7     .12       0  5094.2      .1       0  5208.7     .05       0
Bank Sta=4997.9,5132.2
XS Rating Curve= 0 ,0
Exp/Cntr=0.3,0.1

Type RM Length L Ch R = 1 ,90190   ,487,487,487
BEGIN DESCRIPTION:
VATOSS GULLY 135.0
END DESCRIPTION:
XS GIS Cut Line= 3
      2294837.69     13368096.87      2294037.72     13368446.85
       2293637.7     13368846.88
#Sta/Elev= 30
  4132.2  360.29  4141.1  360.33    4154  359.42  4175.8   359.4  4198.8   358.1
  4268.6  355.81  4292.4  354.37    4405  350.55  4443.6  348.49  4525.1  346.13
  4542.7  346.46  4571.5  345.72  4688.5  344.86  4746.1  345.11  4826.9  344.39
  4897.4   343.5  4944.2  343.95  4967.6   342.5  4983.6  343.55    4991  341.17
  4999.7  339.72  5002.4  339.22  5005.7  339.72  5008.9  339.72  5019.5  343.44
    5062   344.7  5123.2  345.32  5203.4  346.45  5313.3  349.27  5571.1  356.36
#Mann= 6 ,-1 , 0
  4132.2      .1       0  4826.9     .12       0  4999.7     .07       0
  5005.7     .12       0  5123.2      .1       0  5313.3     .05       0
Bank Sta=4983.6,5019.5
XS Rating Curve= 0 ,0
Exp/Cntr=0.3,0.1

Type RM Length L Ch R = 1 ,89703   ,327,327,327
BEGIN DESCRIPTION:
VATOSS GULLY 134.0
END DESCRIPTION:
XS GIS Cut Line= 3
      2294537.74     13367346.83      2293737.72     13368146.85
      2293337.71     13368546.86
#Sta/Elev= 30
  3845.1  367.69    3930  365.71  3944.1  364.16    4029  359.68  4241.1  351.37
  4311.8   349.8    4326  348.32  4368.4  346.84  4538.1  343.84  4566.4   343.8
  4580.5  344.98  4594.7  343.59  4714.2  342.85  4715.5  342.85  4863.4   344.2
    4888  343.55  4896.9  343.57  4919.9  343.57  4948.2  341.89    4973  338.71
  4987.6  338.43  4990.4  337.93  4993.6  338.43  5018.9  339.86  5061.4  340.58
  5078.4  341.84  5089.6  342.28    5168  344.14    5429  354.58  5542.2  357.81
#Mann= 9 ,-1 , 0
  3845.1      .1       0  4714.2     .05       0  4715.5      .1       0
    4888     .05       0  4896.9     .12       0  4987.6     .07       0
  4993.6     .12       0  5078.4      .1       0    5168     .05       0
Bank Sta=4948.2,5089.6
XS Rating Curve= 0 ,0
Exp/Cntr=0.3,0.1