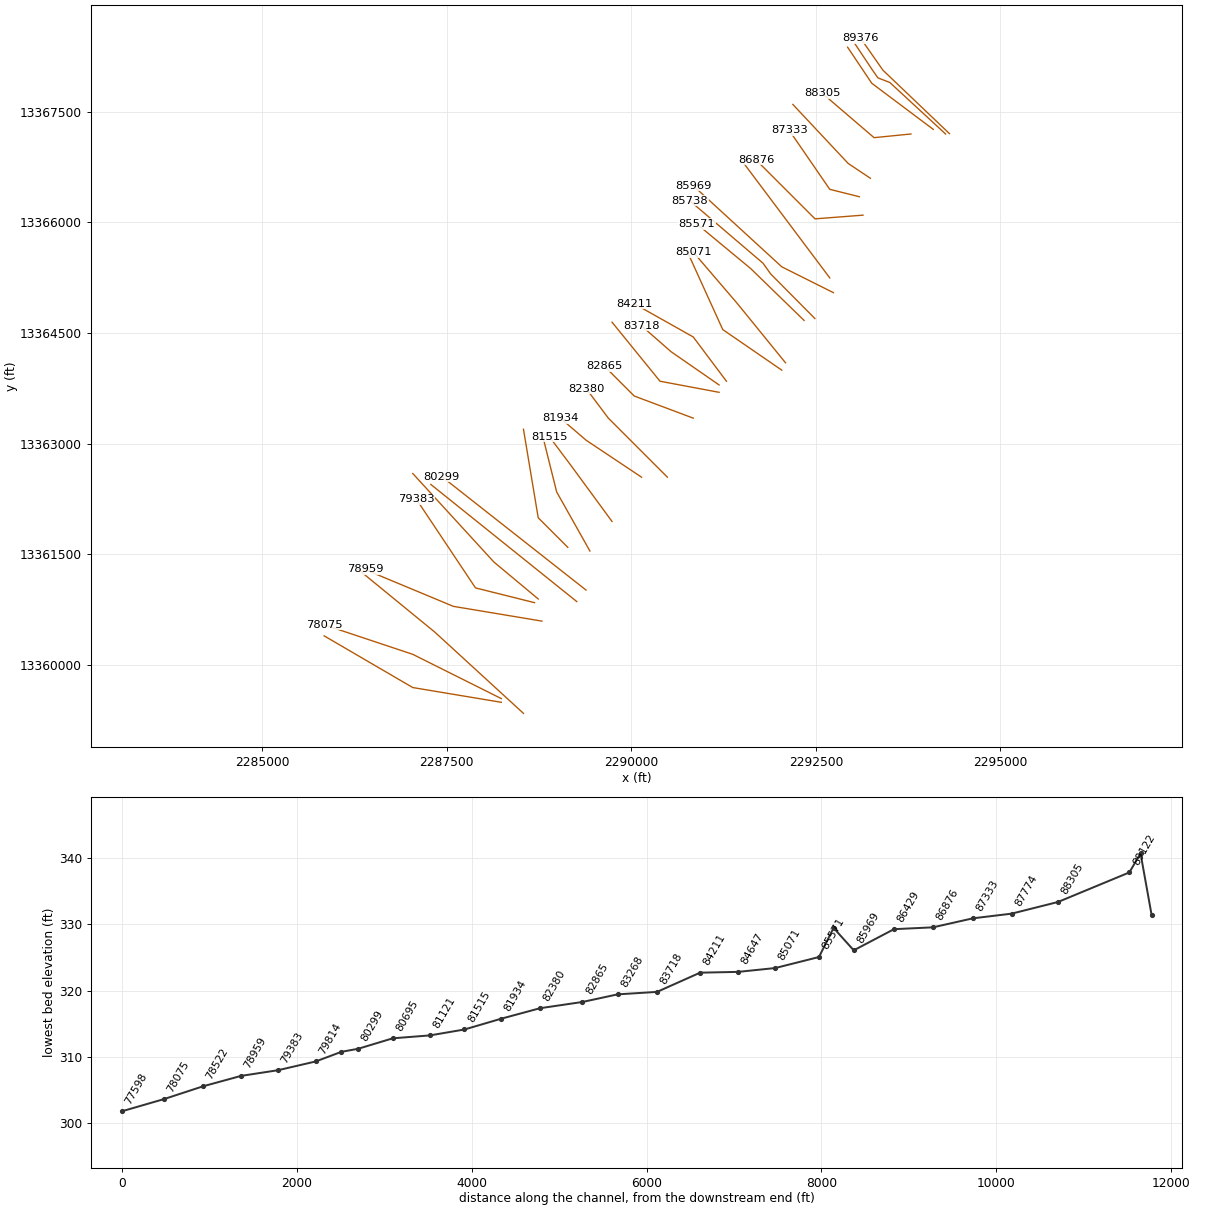
HEC-RAS study VATOSS GULLY.prj: VATOSS GULLY Base Level Engineering

--- VATOSS GULLY.g01 (geometry) --- (continued)

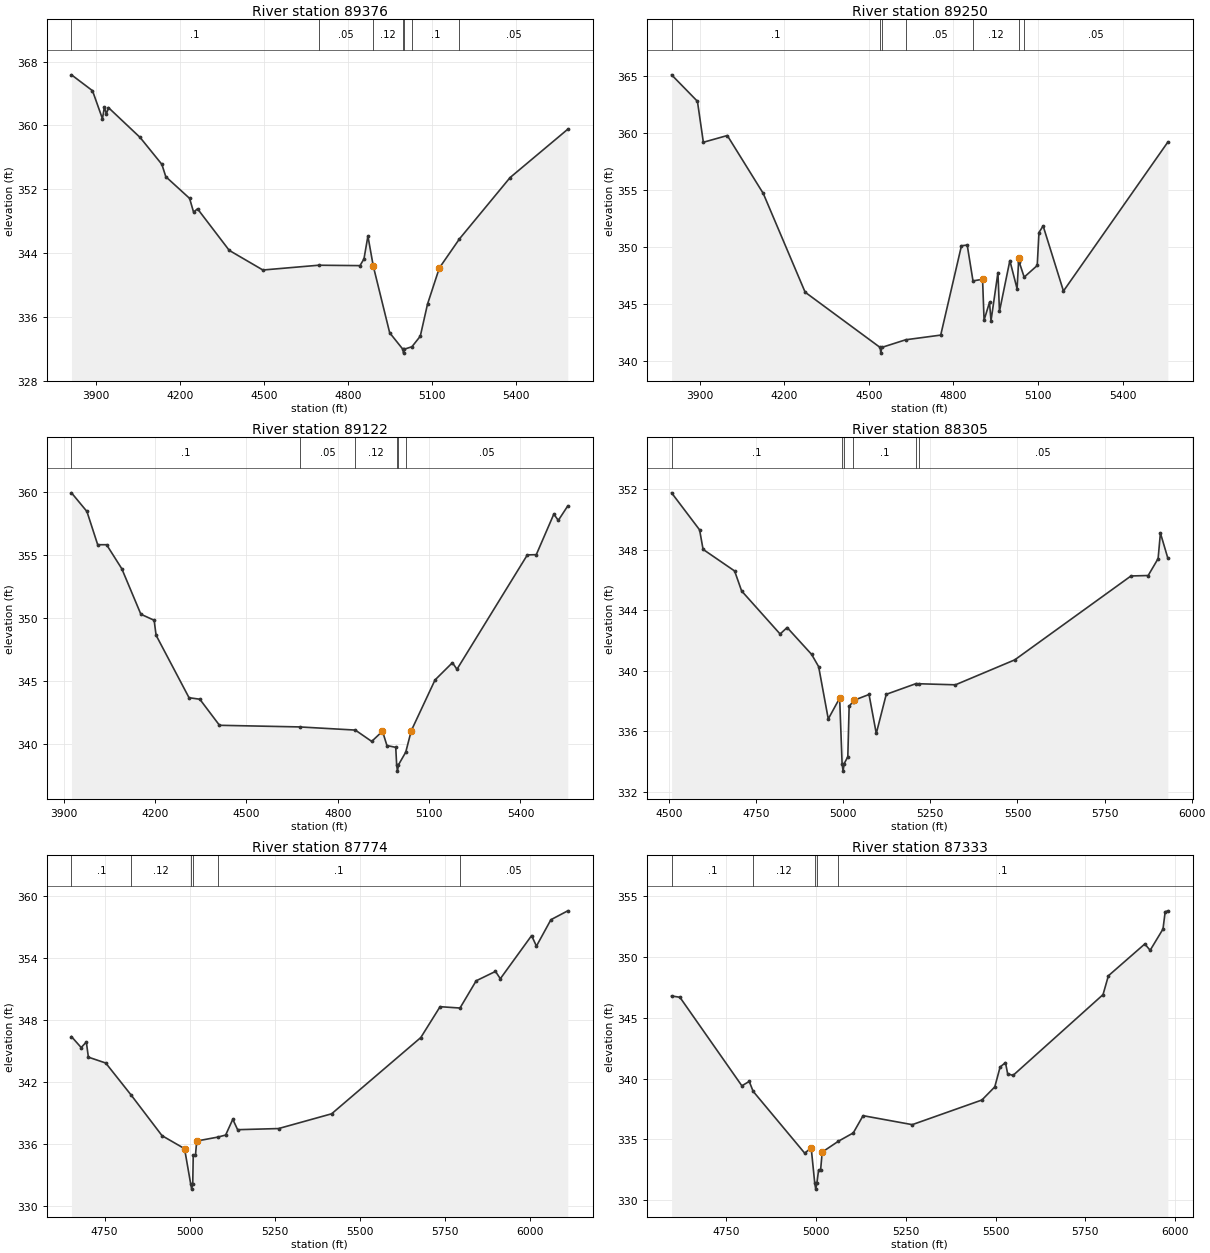
Type RM Length L Ch R = 1 ,89376   ,126,126,126
BEGIN DESCRIPTION:
VATOSS GULLY 133.0
END DESCRIPTION:
XS GIS Cut Line= 3
      2294308.75     13367201.71      2293407.74     13368061.06
      2293106.17     13368492.62
#Sta/Elev= 30
  3812.8  366.34  3887.8  364.35  3923.4  360.83  3930.3  362.31  3937.5   361.4
  3944.5  362.24  4057.7  358.49  4135.4  355.12  4149.5  353.57  4234.4  350.85
  4248.6  349.13  4262.8  349.54    4376  344.33  4496.1  341.87    4695  342.47
  4842.7  342.42  4856.9  343.26    4871  346.13    4890  342.38  4948.7     334
  4995.4  331.95  4998.2  331.45  5001.4  331.95  5028.1  332.25  5057.9  333.57
  5083.7  337.59    5126  342.13  5197.5  345.76  5378.5  353.46  5584.4  359.52
#Mann= 7 ,-1 , 0
  3812.8      .1       0    4695     .05       0    4890     .12       0
  4995.4     .07       0  5001.4     .12       0  5028.1      .1       0
  5197.5     .05       0
Bank Sta=4890,5126
XS Rating Curve= 0 ,0
Exp/Cntr=0.3,0.1

Type RM Length L Ch R = 1 ,89250   ,128,128,128
BEGIN DESCRIPTION:
Mapping XS 83b7e9b4
END DESCRIPTION:
XS GIS Cut Line= 5
      2294256.67      13367196.5      2293501.49     13367894.39
      2293340.03     13367956.89      2293267.12     13368061.06
      2293027.51     13368420.46
#Sta/Elev= 30
  3800.3  365.07    3892  362.75    3913  359.16    3998  359.75  4125.6  354.67
  4274.1  346.02  4539.9  341.18  4542.7  340.68  4545.9  341.18  4630.7  341.85
    4755  342.26  4828.6  350.09    4849  350.15  4869.5  347.01  4903.5  347.15
  4908.8  343.57  4928.1  345.13  4933.4  343.51    4958  347.74  4963.4  344.34
  5000.3  348.79  5025.9  346.32    5032  349.04  5033.3  348.67  5051.1  347.34
  5097.4  348.36  5103.5  351.25  5118.3  351.83  5190.4  346.12  5560.8  359.18
#Mann= 7 ,-1 , 0
  3800.3      .1       0  4539.9     .07       0  4545.9      .1       0
  4630.7     .05       0  4869.5     .12       0  5033.3      .1       0
  5051.1     .05       0
Bank Sta=4903.5,5032
XS Rating Curve= 0 ,0
Exp/Cntr=0.3,0.1

Type RM Length L Ch R = 1 ,89122   ,817,817,817
BEGIN DESCRIPTION:
Mapping XS 6adfabc8
END DESCRIPTION:
XS GIS Cut Line= 3
      2294090.01     13367258.99       2293256.7     13367883.97
      2292929.14     13368372.72
#Sta/Elev= 30
  3925.3  359.91    3976  358.43  4011.4  355.79  4040.6  355.79  4090.6  353.88
  4153.2  350.27  4196.8  349.79  4203.2   348.6  4311.4  343.64  4346.8  343.52
  4411.4  341.45  4674.4  341.32  4857.5  341.07  4911.4  340.17  4946.8  340.98
  4961.4  339.84  4990.3   339.7  4993.3  338.31    4996  337.81  4999.3  338.31
  5023.2  339.32  5041.3  341.02  5119.3  345.05  5176.4  346.42  5191.4   345.9
  5422.5  354.98  5451.9     355  5509.5  358.22  5524.2  357.72  5555.3  358.87
#Mann= 6 ,-1 , 0
  3925.3      .1       0  4674.4     .05       0  4857.5     .12       0
  4993.3     .07       0  4999.3     .12       0  5023.2     .05       0
Bank Sta=4946.8,5041.3
XS Rating Curve= 0 ,0
Exp/Cntr=0.3,0.1

Type RM Length L Ch R = 1 ,88305   ,531,531,531
BEGIN DESCRIPTION:
VATOSS GULLY 131.0
END DESCRIPTION:
XS GIS Cut Line= 3
       2293787.7     13367196.85      2293287.72     13367146.85
      2292587.75     13367746.83
#Sta/Elev= 30
  4507.3  351.76  4587.7  349.31  4597.7  348.02  4688.2  346.59  4708.3  345.27
  4818.8  342.42  4838.9  342.85  4909.3  341.07  4929.4  340.26    4957   336.8
  4989.7  338.18  4996.7  333.85  4999.5  333.35  5002.7  333.85  5013.1   334.3
  5016.9  337.63  5027.7  337.95  5031.2  338.04    5074  338.42  5094.8  335.84
  5123.4  338.43    5209  339.14  5216.5  339.13    5322  339.06  5492.2  340.71
  5825.8  346.26  5875.2  346.29  5903.7  347.41  5910.3   349.1  5931.7  347.43
#Mann= 6 ,-1 , 0
  4507.3      .1       0  4996.7     .07       0  5002.7      .1       0
  5027.7      .1       0    5209     .12       0  5216.5     .05       0
Bank Sta=4989.7,5031.2
XS Rating Curve= 0 ,0
Exp/Cntr=0.3,0.1

Type RM Length L Ch R = 1 ,87774   ,441,441,441
BEGIN DESCRIPTION:
VATOSS GULLY 130.0
END DESCRIPTION:
XS GIS Cut Line= 3
      2293237.71     13366596.86      2292937.72     13366796.85
      2292187.74     13367596.83
#Sta/Elev= 30
    4653  346.37  4681.5  345.31  4696.6  345.85  4702.6  344.38  4753.6  343.81
  4828.3   340.7  4918.9  336.77    4985  335.51    5003  332.09  5005.8  331.59
    5009  332.09  5010.5  334.85    5017  334.85  5020.6  336.25  5082.2  336.63
  5105.6  336.83  5126.6  338.36  5140.8  337.35    5261  337.46  5416.8  338.89
  5678.6  346.28  5735.2  349.27  5793.7  349.14  5841.2  351.78  5897.9  352.69
  5912.1  351.98  6003.9  356.16  6018.1  355.14  6060.6   357.7  6110.1  358.56
#Mann= 6 ,-1 , 0
    4653      .1       0  4828.3     .12       0    5003     .07       0
    5009     .12       0  5082.2      .1       0  5793.7     .05       0
Bank Sta=4985,5020.6
XS Rating Curve= 0 ,0
Exp/Cntr=0.3,0.1

Type RM Length L Ch R = 1 ,87333   ,457,457,457
BEGIN DESCRIPTION:
VATOSS GULLY 129.0
END DESCRIPTION:
XS GIS Cut Line= 3
      2293087.75     13366346.85      2292687.72     13366446.85
       2292137.7     13367246.89
#Sta/Elev= 30
  4597.2   346.8  4620.4  346.69  4793.1   339.4  4813.7  339.76  4824.4  338.95
  4968.3  333.85  4986.3  334.29  4996.2  331.39    4999  330.89  5002.2  331.39
    5007  332.48  5012.6  332.48    5017  333.94  5062.4  334.84  5103.6  335.52
  5130.9  336.94    5268   336.2  5462.1  338.23    5498  339.31  5512.9  340.95
  5527.8  341.31  5533.8   340.4  5548.7  340.25  5799.7  346.91  5814.6  348.46
  5916.1  351.08    5931  350.56  5966.8  352.31  5972.9  353.73  5980.4  353.81
#Mann= 5 ,-1 , 0
  4597.2      .1       0  4824.4     .12       0  4996.2     .07       0
  5002.2     .12       0  5062.4      .1       0
Bank Sta=4986.3,5017
XS Rating Curve= 0 ,0
Exp/Cntr=0.3,0.1

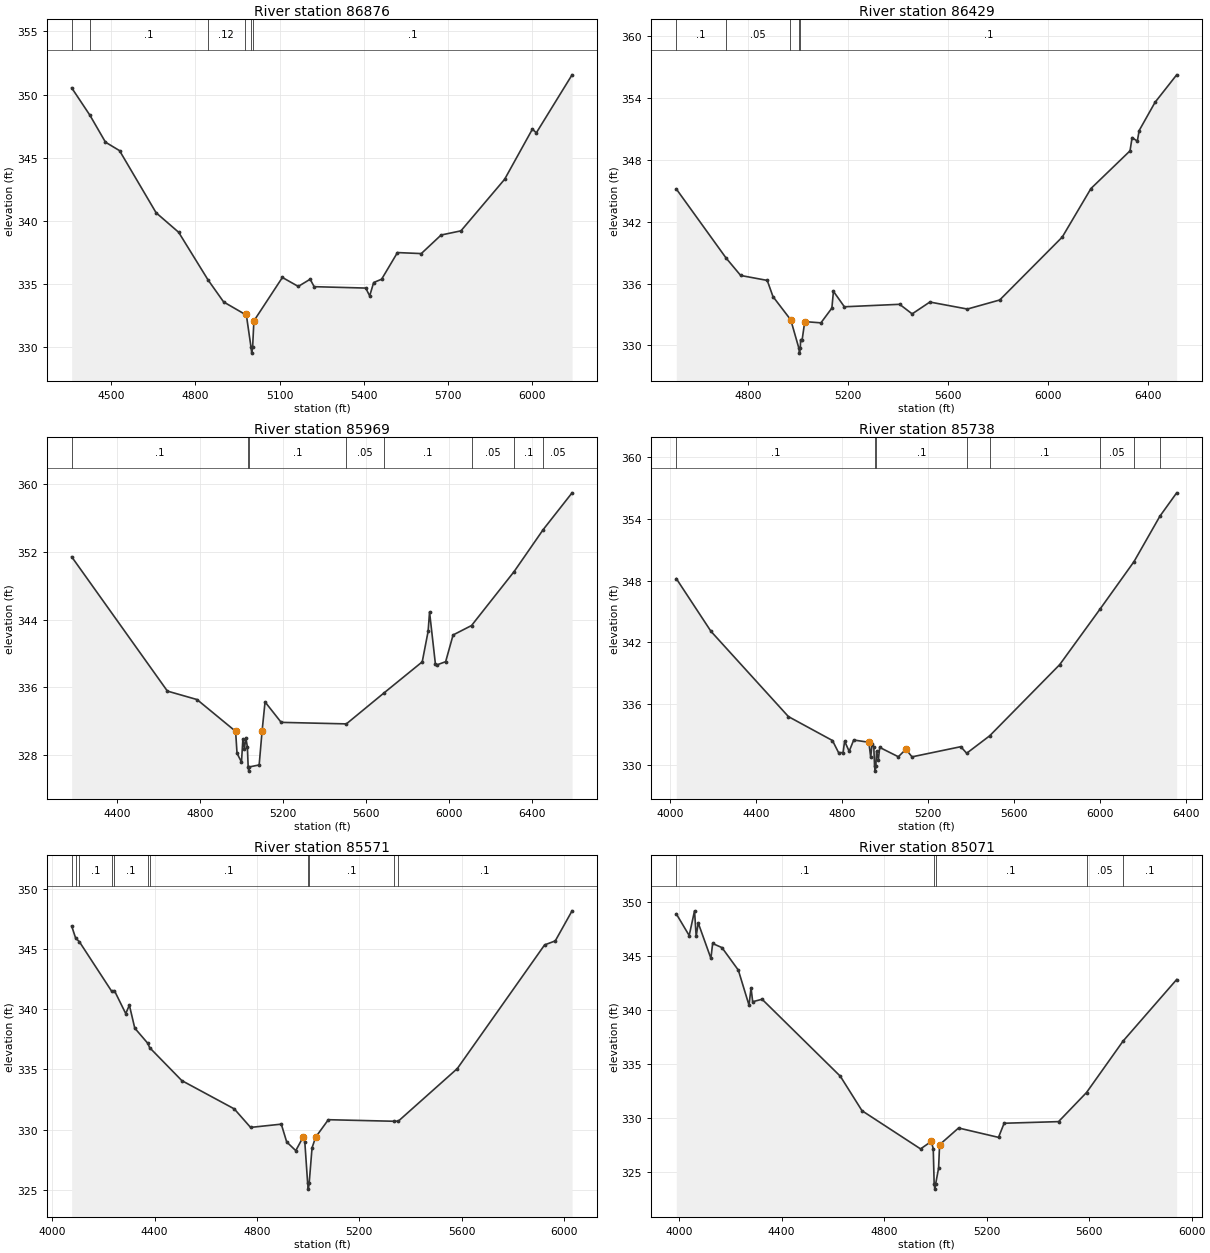
Type RM Length L Ch R = 1 ,86876   ,447,447,447
BEGIN DESCRIPTION:
VATOSS GULLY 128.0
END DESCRIPTION:
XS GIS Cut Line= 3
      2293137.72     13366096.85      2292487.72     13366046.85
      2291687.71     13366846.86
#Sta/Elev= 30
  4359.1  350.53  4423.8  348.37  4479.5  346.23  4529.6  345.56    4660  340.64
  4740.2   339.1  4845.2  335.32  4900.7  333.58  4975.4  332.62  4980.9  332.66
    4998  330.03  5000.7  329.53    5004  330.03  5008.5  332.08    5110  335.52
  5166.6  334.81    5209  335.38  5223.2  334.79    5407  334.68  5421.1  334.06
  5435.3  335.12  5463.6  335.38  5520.1  337.49    5605  337.41  5675.7  338.88
  5746.4  339.21    5902  343.29    6001  347.26  6015.1  346.97  6142.4  351.56
#Mann= 6 ,-1 , 0
  4359.1     .05       0  4423.8      .1       0  4845.2     .12       0
  4975.4      .1       0    4998     .07       0    5004      .1       0
Bank Sta=4980.9,5008.5
XS Rating Curve= 0 ,0
Exp/Cntr=0.3,0.1

Type RM Length L Ch R = 1 ,86429   ,460,460,460
BEGIN DESCRIPTION:
VATOSS GULLY 127.0
END DESCRIPTION:
XS GIS Cut Line= 3
       2292687.7     13365246.88      2292387.72     13365646.85
       2291487.7     13366846.88
#Sta/Elev= 30
  4513.4  345.19  4712.5  338.48  4770.7  336.79  4876.9  336.31  4899.8  334.74
    4969  332.54  4970.7   332.5  5003.1  329.75  5005.8  329.25  5009.1  329.75
  5010.2  330.56  5016.5  330.56  5026.9  332.31  5091.5  332.19  5135.2  333.62
  5141.5  335.25  5185.2  333.75  5406.1  333.99  5456.1  333.06  5526.9  334.21
  5676.9  333.53  5806.1  334.41  6056.1  340.52  6170.7  345.23  6326.9  348.89
  6335.2  350.18  6356.1  349.83  6363.4  350.86  6426.9   353.6  6513.4  356.27
#Mann= 5 ,-1 , 0
  4513.4      .1       0  4712.5     .05       0    4969      .1       0
  5003.1     .07       0  5009.1      .1       0
Bank Sta=4970.7,5026.9
XS Rating Curve= 0 ,0
Exp/Cntr=0.3,0.1

Type RM Length L Ch R = 1 ,85969   ,231,231,231
BEGIN DESCRIPTION:
VATOSS GULLY 126.0
END DESCRIPTION:
XS GIS Cut Line= 3
      2292737.68     13365046.87      2292037.72     13365396.85
      2290837.69     13366496.88
#Sta/Elev= 30
  4182.5  351.42  4643.6  335.53  4786.2  334.53  4972.2  330.77    4979  328.16
  5000.5  327.14  5007.3  329.88  5014.7  328.73  5021.5  330.02  5028.9  328.91
  5032.7  326.56  5035.4  326.06  5038.7  326.56  5085.6  326.79  5099.8  330.83
    5114  334.25  5191.7  331.83  5505.8  331.65  5687.9  335.33  5871.2  338.99
  5899.6  342.61  5906.4  344.89  5934.7  338.72  5941.8  338.63    5984  339.01
  6019.8  342.17  6108.8  343.29    6314  349.68  6454.2  354.65    6593  358.99
#Mann= 8 ,-1 , 0
  4182.5      .1       0  5032.7     .07       0  5038.7      .1       0
  5505.8     .05       0  5687.9      .1       0  6108.8     .05       0
    6314      .1       0  6454.2     .05       0
Bank Sta=4972.2,5099.8
XS Rating Curve= 0 ,0
Exp/Cntr=0.3,0.1

Type RM Length L Ch R = 1 ,85738   ,167,167,167
BEGIN DESCRIPTION:
VATOSS GULLY 125.0
END DESCRIPTION:
XS GIS Cut Line= 4
       2292485.9     13364696.44      2291886.91     13365300.64
      2291782.74     13365446.47      2290793.13     13366290.25
#Sta/Elev= 30
    4027  348.19  4188.6  343.05  4549.2  334.75  4754.3  332.42  4782.6  331.25
  4803.8  331.24  4810.9  332.36  4832.1  331.37  4853.3  332.47  4923.9  332.25
  4932.5  330.78  4938.7   332.1  4946.9  331.78  4950.4  329.94  4953.2  329.44
  4956.4  329.94  4959.6  331.38  4968.2  330.55  4974.3  331.75  5061.2  330.84
  5096.3  331.57  5124.8  330.83  5352.1  331.82  5379.4  331.18  5486.6  332.88
  5812.7  339.81  6001.3  345.24    6159  349.85  6279.5  354.27  6357.5  356.54
#Mann= 8 ,-1 , 0
    4027      .1       0  4950.4     .07       0  4956.4      .1       0
  5379.4     .05       0  5486.6      .1       0  6001.3     .05       0
    6159      .1       0  6279.5     .05       0
Bank Sta=4923.9,5096.3
XS Rating Curve= 0 ,0
Exp/Cntr=0.3,0.1

Type RM Length L Ch R = 1 ,85571   ,500,500,500
BEGIN DESCRIPTION:
Mapping XS ae2c04f6
END DESCRIPTION:
XS GIS Cut Line= 3
      2292340.01     13364670.45      2291616.08     13365373.56
      2290886.93     13365977.71
#Sta/Elev= 30
  4075.8  346.91  4091.3  345.91  4105.6  345.62  4232.3  341.49    4243  341.54
  4287.1  339.64  4301.3  340.34  4322.4  338.43  4373.3  337.17  4380.5  336.81
  4506.3  334.07  4711.3  331.72  4775.1  330.18  4895.2  330.45  4916.3  328.97
  4951.8  328.25  4980.1  329.36  4987.1  328.98  4998.2  325.55    5001  325.05
  5004.2  325.55  5015.4  328.48  5029.5  329.37  5079.1  330.82  5337.1  330.69
  5352.7   330.7  5583.3  335.07  5924.6  345.35  5966.2  345.68  6031.9  348.18
#Mann= 11 ,-1 , 0
  4075.8      .1       0  4091.3     .08       0  4105.6      .1       0
  4232.3     .05       0    4243      .1       0  4373.3     .05       0
  4380.5      .1       0  4998.2     .07       0  5004.2      .1       0
  5337.1     .05       0  5352.7      .1       0
Bank Sta=4980.1,5029.5
XS Rating Curve= 0 ,0
Exp/Cntr=0.3,0.1

Type RM Length L Ch R = 1 ,85071   ,424,424,424
BEGIN DESCRIPTION:
VATOSS GULLY 124.0
END DESCRIPTION:
XS GIS Cut Line= 3
      2292087.75     13364096.82      2291437.72     13364896.85
      2290837.71     13365596.87
#Sta/Elev= 30
  3988.8  348.92  4039.1  346.91    4060   349.2  4066.4  346.82  4074.3  348.08
  4123.9  344.79  4130.6  346.17    4167  345.79  4230.9   343.7  4272.6  340.45
  4280.5  342.06  4286.9  340.77  4323.6     341  4628.9  333.86  4713.6  330.66
  4942.1  327.12  4983.7  327.81  4991.6  327.14  4995.1  323.89  4997.8  323.39
  5001.1  323.89  5012.4  325.34  5016.4  327.51  5090.4  329.06  5246.3  328.19
  5268.2   329.5  5480.6  329.65  5589.8  332.35    5732  337.11  5941.6  342.83
#Mann= 5 ,-1 , 0
  3988.8      .1       0  4995.1     .07       0  5001.1      .1       0
  5589.8     .05       0    5732      .1       0
Bank Sta=4983.7,5016.4
XS Rating Curve= 0 ,0
Exp/Cntr=0.3,0.1

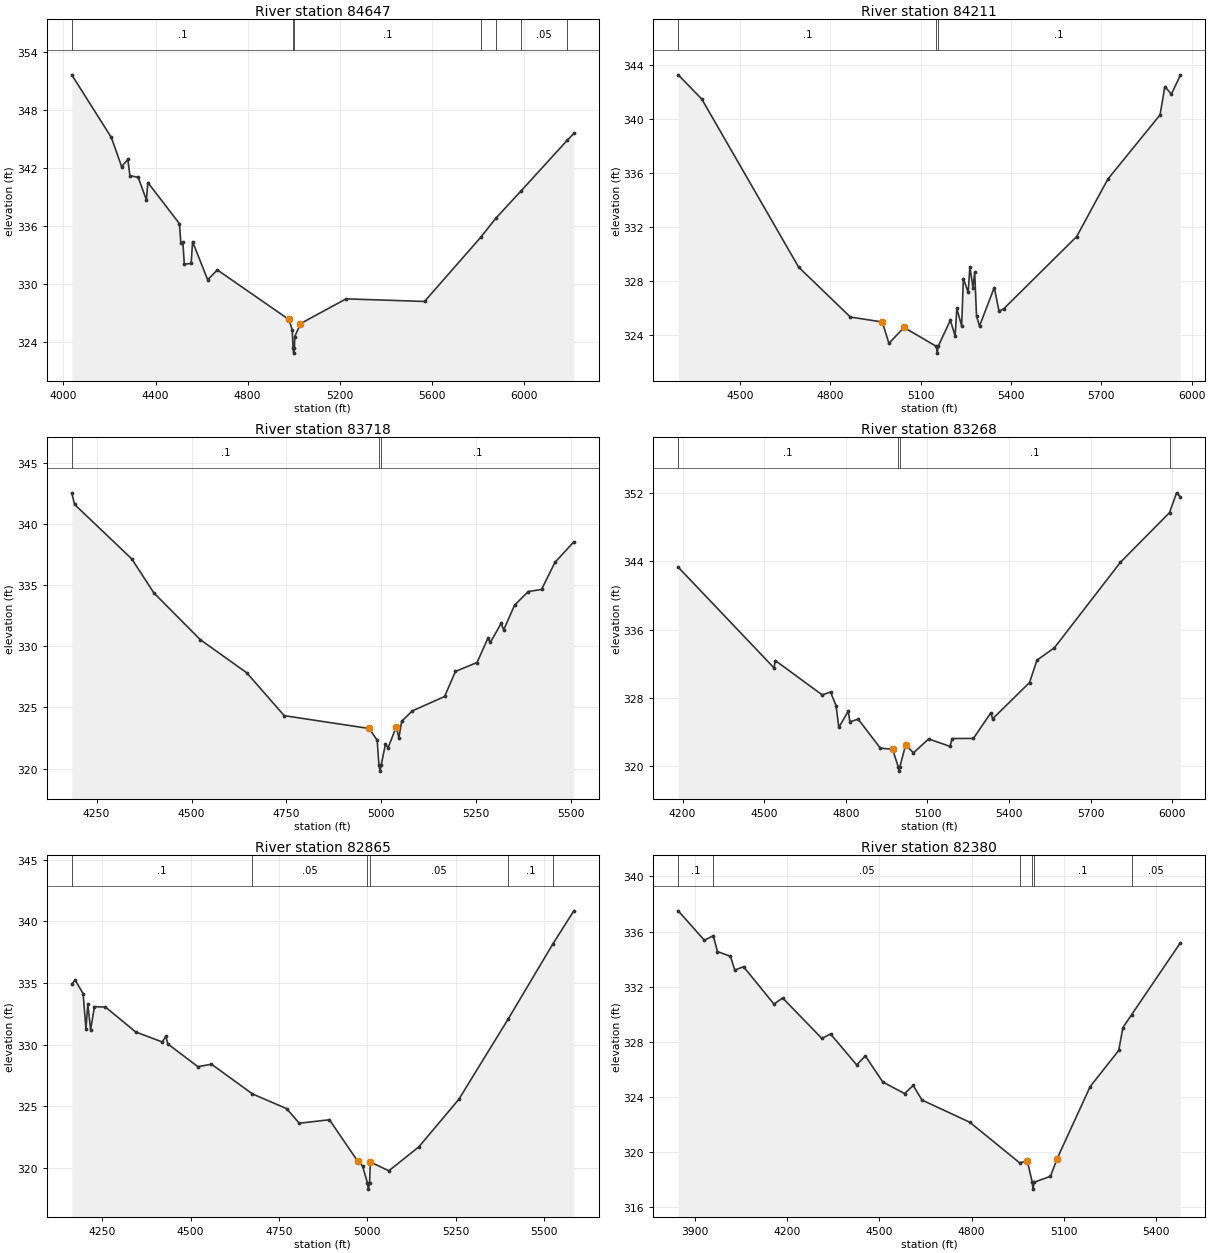
Type RM Length L Ch R = 1 ,84647   ,436,436,436
BEGIN DESCRIPTION:
VATOSS GULLY 123.0
END DESCRIPTION:
XS GIS Cut Line= 3
      2292037.68     13363996.88      2291237.72     13364546.85
      2290737.71     13365646.87
#Sta/Elev= 30
  4036.5  351.68  4208.3  345.18    4253  342.15    4280  342.91  4288.8  341.22
  4324.7  341.05  4360.5   338.7  4366.6  340.51  4503.9  336.24    4510  334.19
  4518.8  334.31  4524.9  332.03  4554.7  332.12  4560.8  334.38  4626.4  330.42
  4668.3  331.44  4978.9   326.3  4993.8  325.19  4996.8  323.31  4999.6  322.81
  5002.8  323.31  5004.2  324.52  5029.2  325.87    5227  328.44  5567.5  328.17
  5810.9  334.81  5877.7  336.82  5984.7  339.59  6187.7  344.91  6215.6   345.6
#Mann= 7 ,-1 , 0
  4036.5      .1       0  4996.8     .07       0  5002.8      .1       0
  5810.9     .05       0  5877.7      .1       0  5984.7     .05       0
  6187.7      .1       0
Bank Sta=4978.9,5029.2
XS Rating Curve= 0 ,0
Exp/Cntr=0.3,0.1

Type RM Length L Ch R = 1 ,84211   ,493,493,493
BEGIN DESCRIPTION:
VATOSS GULLY 122.0
END DESCRIPTION:
XS GIS Cut Line= 3
      2291287.74     13363846.82      2290837.72     13364446.85
      2290037.74     13364896.85
#Sta/Elev= 30
  4294.4  343.27  4372.6  341.48  4694.4  329.05  4866.3  325.36  4972.6  324.99
  4994.4  323.41  5044.4  324.59    5152  323.19  5154.8  322.69    5158  323.19
  5198.4  325.12  5214.3  323.96    5220     326    5236   324.7  5241.7   328.2
  5257.7  327.19  5263.4  329.09  5273.6  327.53  5279.3  328.67  5285.4  325.44
  5295.3  324.69  5344.3  327.54  5360.3  325.79  5376.2  325.98  5618.1  331.31
  5721.4  335.55  5895.1  340.31    5911   342.4  5932.7  341.84  5962.3  343.23
#Mann= 3 ,-1 , 0
  4294.4      .1       0    5152     .07       0    5158      .1       0
Bank Sta=4972.6,5044.4
XS Rating Curve= 0 ,0
Exp/Cntr=0.3,0.1

Type RM Length L Ch R = 1 ,83718   ,450,450,450
BEGIN DESCRIPTION:
VATOSS GULLY 121.0
END DESCRIPTION:
XS GIS Cut Line= 3
       2291187.7     13363796.87      2290537.72     13364246.85
      2290137.69     13364596.89
#Sta/Elev= 30
  4184.7  342.57  4192.1  341.62  4342.8  337.16  4400.9  334.38  4523.2  330.55
  4645.5  327.84  4744.2  324.33  4967.8  323.28    4989  322.32  4993.6  320.29
  4996.4  319.79  4999.6  320.29  5010.8  322.02  5017.5  321.69  5039.3  323.42
    5046  322.51  5053.5  323.87  5081.5  324.72  5166.5   325.9    5195  327.95
  5251.9  328.68  5280.4  330.66    5287  330.33  5315.5  331.89  5322.1  331.35
  5350.6  333.37  5386.7  334.49  5421.8  334.66  5456.9  336.87  5506.8  338.56
#Mann= 3 ,-1 , 0
  4184.7      .1       0  4993.6     .07       0  4999.6      .1       0
Bank Sta=4967.8,5039.3
XS Rating Curve= 0 ,0
Exp/Cntr=0.3,0.1

Type RM Length L Ch R = 1 ,83268   ,403,403,403
BEGIN DESCRIPTION:
VATOSS GULLY 120.0
END DESCRIPTION:
XS GIS Cut Line= 3
       2291187.7     13363696.86      2290387.72     13363846.85
      2289737.72     13364646.86
#Sta/Elev= 30
  4184.1  343.31  4535.9  331.52    4541  332.37  4713.1  328.35  4743.7  328.69
    4764   327.1  4774.2  324.55  4808.9  326.44  4814.9   325.2  4845.4  325.51
  4926.8  322.11  4971.7  321.99  4992.5  319.92  4995.2  319.42  4998.5  319.92
  5019.6   322.5  5048.3  321.56  5104.3  323.19  5182.6  322.32  5190.5  323.24
  5268.6  323.25  5332.8  326.25  5339.2  325.55  5474.8  329.79  5502.3  332.42
  5566.2  333.87    5809  343.89  5989.3   349.7  6015.2  352.02  6028.8  351.58
#Mann= 4 ,-1 , 0
  4184.1      .1       0  4992.5     .07       0  4998.5      .1       0
  5989.3     .05       0
Bank Sta=4971.7,5019.6
XS Rating Curve= 0 ,0
Exp/Cntr=0.3,0.1

Type RM Length L Ch R = 1 ,82865   ,485,485,485
BEGIN DESCRIPTION:
VATOSS GULLY 119.0
END DESCRIPTION:
XS GIS Cut Line= 3
      2290837.75     13363346.85      2290037.72     13363646.85
      2289637.73     13364046.85
#Sta/Elev= 30
    4164  334.93  4173.8  335.23  4196.1  334.14  4204.1  331.28  4209.4   333.3
  4217.4   331.2  4228.1  333.08  4259.3  333.05  4344.7  331.03  4420.3  330.21
  4430.1   330.7  4435.5  330.06  4520.9  328.21  4559.2  328.41  4675.1     326
  4771.9   324.8  4807.5  323.62  4892.9   323.9    4973  320.53  4986.4  320.16
  5000.3  318.77    5003  318.27  5006.3  318.77  5008.6  320.47  5060.9  319.76
  5145.7   321.7  5258.8  325.56  5398.8   332.1  5524.5  338.16  5584.1  340.86
#Mann= 6 ,-1 , 0
    4164      .1       0  4675.1     .05       0  5000.3     .03       0
  5006.3     .05       0  5398.8      .1       0  5524.5     .05       0
Bank Sta=4973,5008.6
XS Rating Curve= 0 ,0
Exp/Cntr=0.3,0.1

Type RM Length L Ch R = 1 ,82380   ,446,446,446
BEGIN DESCRIPTION:
VATOSS GULLY 118.0
END DESCRIPTION:
XS GIS Cut Line= 3
      2290487.73     13362546.84      2289687.72     13363346.85
      2289387.71     13363746.86
#Sta/Elev= 30
    3847  337.51  3931.9  335.38    3961   335.7  3974.3  334.56  4016.7  334.21
  4030.9  333.21  4059.2  333.46  4158.1  330.75  4186.4  331.19  4313.7  328.26
    4342  328.58  4426.8  326.34  4455.1  326.99  4511.7   325.1  4582.4  324.26
  4610.7  324.85    4639  323.79  4794.5  322.18  4956.3  319.24  4981.5  319.37
  4997.3  317.83    5000  317.33  5003.3  317.83  5056.5  318.26  5078.4  319.55
  5185.7  324.77  5278.4  327.39  5291.9  329.04  5319.9  329.97  5478.4  335.18
#Mann= 6 ,-1 , 0
    3847      .1       0    3961     .05       0  4956.3      .1       0
  4997.3     .07       0  5003.3      .1       0  5319.9     .05       0
Bank Sta=4981.5,5078.4
XS Rating Curve= 0 ,0
Exp/Cntr=0.3,0.1

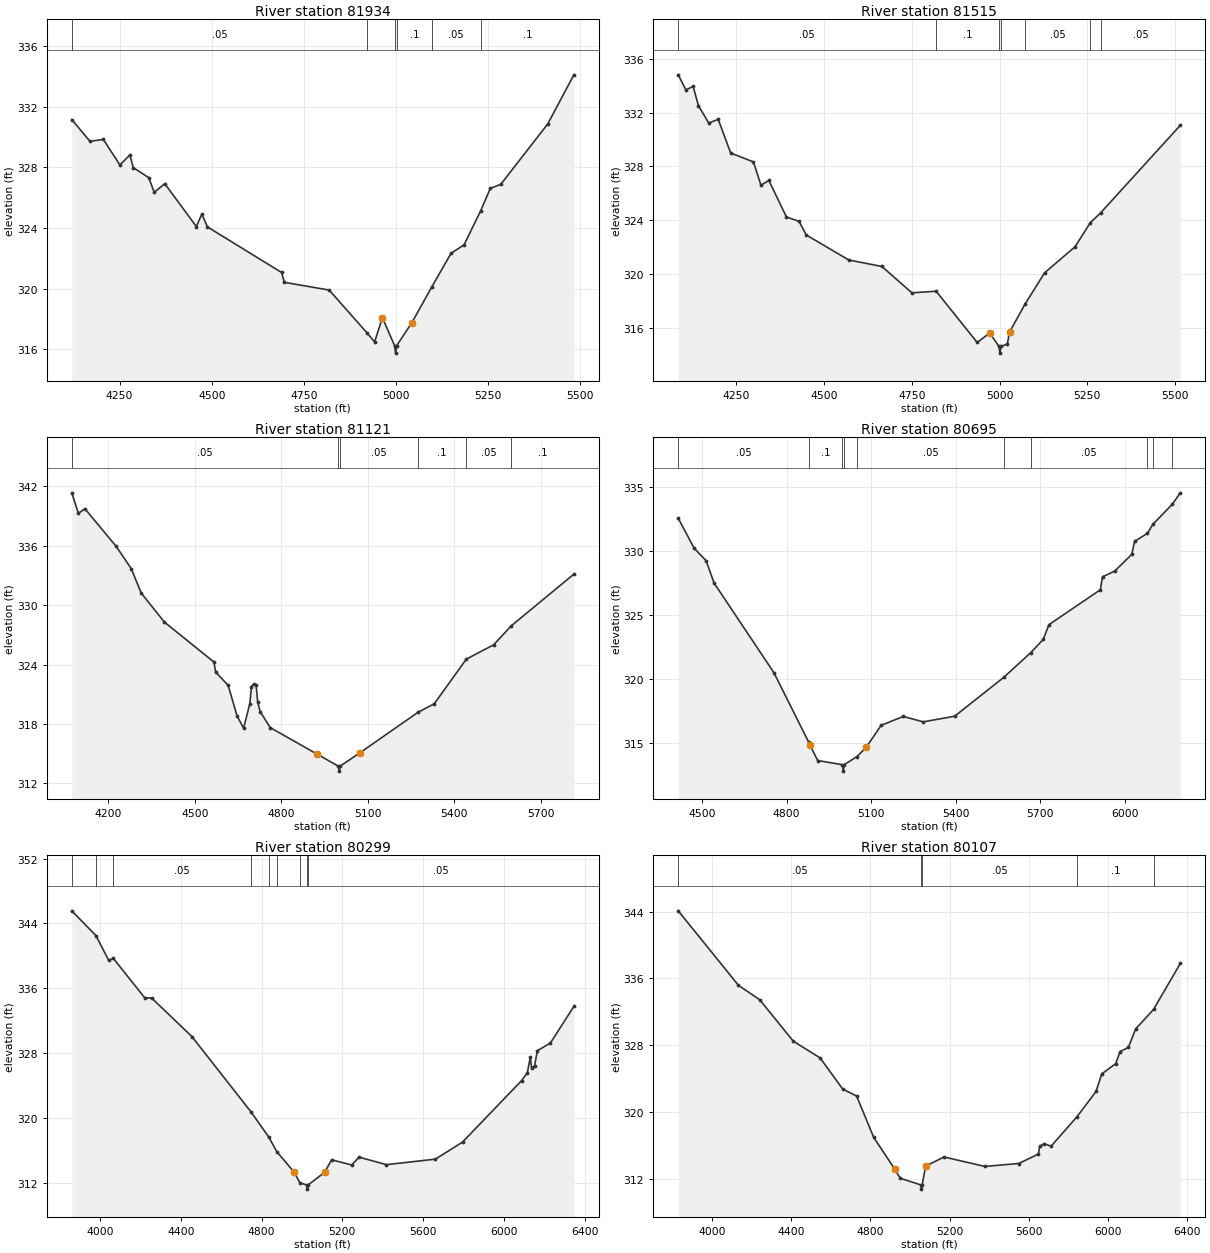
Type RM Length L Ch R = 1 ,81934   ,419,419,419
BEGIN DESCRIPTION:
VATOSS GULLY 117.0
END DESCRIPTION:
XS GIS Cut Line= 3
       2290137.7     13362546.87      2289387.72     13363046.85
      2289037.75     13363346.83
#Sta/Elev= 30
  4120.3  331.15  4169.8  329.71  4205.9  329.84    4251  328.15    4278  328.82
    4287  327.98  4329.1  327.32  4344.1  326.35  4372.7  326.92  4458.3  324.09
  4473.3  324.91  4488.3  324.07  4689.6  321.06  4697.2  320.41  4818.8   319.9
  4922.3  317.05    4942  316.48  4963.1  318.08  4996.1  316.24  4998.9  315.74
  5002.1  316.24  5043.1  317.75  5097.2  320.11  5149.5  322.33  5184.6  322.88
    5230  325.14    5256  326.61  5284.5  326.88  5411.8  330.86  5482.6   334.1
#Mann= 6 ,-1 , 0
  4120.3     .05       0  4922.3      .1       0  4996.1     .07       0
  5002.1      .1       0  5097.2     .05       0    5230      .1       0
Bank Sta=4963.1,5043.1
XS Rating Curve= 0 ,0
Exp/Cntr=0.3,0.1

Type RM Length L Ch R = 1 ,81515   ,394,394,394
BEGIN DESCRIPTION:
VATOSS GULLY 116.0
END DESCRIPTION:
XS GIS Cut Line= 3
      2289737.73     13361946.84      2289187.72     13362696.85
      2288887.71     13363096.87
#Sta/Elev= 30
  4084.9   334.8  4106.9  333.67  4127.2  333.95  4142.4  332.51  4171.7  331.22
  4198.8  331.49  4234.3  328.99  4299.1  328.33  4320.5   326.6  4343.1  326.95
  4393.2  324.23  4428.8  323.92  4449.6   322.9  4570.8  321.04  4664.9  320.56
  4750.6   318.6  4819.4  318.72  4936.6  314.91  4972.1  315.62  4998.4  314.62
  5001.2  314.12  5004.4  314.62  5022.3   314.8  5028.5  315.68  5072.7  317.76
  5128.5  320.09    5215  322.02  5258.4   323.8  5288.3  324.55    5515  331.05
#Mann= 7 ,-1 , 0
  4084.9     .05       0  4819.4      .1       0  4998.4     .07       0
  5004.4      .1       0  5072.7     .05       0  5258.4      .1       0
  5288.3     .05       0
Bank Sta=4972.1,5028.5
XS Rating Curve= 0 ,0
Exp/Cntr=0.3,0.1

Type RM Length L Ch R = 1 ,81121   ,426,426,426
BEGIN DESCRIPTION:
VATOSS GULLY 115.0
END DESCRIPTION:
XS GIS Cut Line= 3
      2289437.73     13361546.83      2288987.72     13362346.85
      2288787.73     13363146.83
#Sta/Elev= 30
  4072.6  341.36  4095.6  339.29  4118.2  339.75  4226.6  335.95  4279.1   333.7
  4313.6  331.23  4394.2  328.29    4566  324.26    4572  323.24  4615.4   321.9
  4646.3   318.8  4668.9  317.57  4690.6  320.05  4696.3  321.78  4703.7  322.02
  4712.3  321.93    4718  320.18  4726.6  319.24  4761.4  317.63  4923.3  314.96
  4997.8  313.73  5000.6  313.23  5003.8  313.73    5073  315.09    5274  319.17
  5330.7  320.04    5442  324.55  5536.8     326  5598.1  327.92  5815.1  333.14
#Mann= 6 ,-1 , 0
  4072.6     .05       0  4997.8     .03       0  5003.8     .05       0
    5274      .1       0    5442     .05       0  5598.1      .1       0
Bank Sta=4923.3,5073
XS Rating Curve= 0 ,0
Exp/Cntr=0.3,0.1

Type RM Length L Ch R = 1 ,80695   ,396,396,396
BEGIN DESCRIPTION:
VATOSS GULLY 114.0
END DESCRIPTION:
XS GIS Cut Line= 3
      2289137.71     13361596.87      2288737.72     13361996.85
      2288537.72     13363196.84
#Sta/Elev= 30
  4415.4  332.54    4472   330.2  4514.4  329.23  4542.7  327.48  4754.8  320.49
    4879  315.03  4882.1  314.87  4910.4  313.62  4998.3  313.29  5001.1  312.79
  5004.3  313.29  5049.3  313.92  5082.4  314.64  5135.7  316.37  5214.2  317.06
  5285.2  316.64  5396.7  317.08  5571.1  320.12    5667  322.05    5711  323.08
  5731.3  324.23  5913.8  326.96  5921.4  327.97  5964.4  328.41  6025.3  329.72
  6035.4  330.74  6080.7  331.36  6100.3  332.07  6169.7  333.65  6197.6  334.53
#Mann= 10 ,-1 , 0
  4415.4     .05       0    4879      .1       0  4998.3     .07       0
  5004.3      .1       0  5049.3     .05       0  5571.1      .1       0
    5667     .05       0  6080.7      .1       0  6100.3     .05       0
  6169.7      .1       0
Bank Sta=4882.1,5082.4
XS Rating Curve= 0 ,0
Exp/Cntr=0.3,0.1

Type RM Length L Ch R = 1 ,80299   ,192,192,192
BEGIN DESCRIPTION:
Mapping XS 8912f16c
END DESCRIPTION:
XS GIS Cut Line= 2
      2289385.14     13361017.68      2287432.05     13362554.11
#Sta/Elev= 30
  3860.7  345.56  3980.1  342.51  4043.6  339.45  4066.5  339.69  4221.7  334.83
  4256.9  334.78  4455.7  330.03  4747.9  320.74  4835.6  317.64  4875.8  315.82
  4962.6  313.27  4989.4     312  5023.8  311.71  5026.5  311.21  5029.8  311.71
  5111.8  313.27    5147  314.83  5246.4  314.19  5282.4  315.16  5418.1  314.23
  5660.3  314.91  5794.9  317.02  6086.8   324.6  6115.7  325.59  6130.2   327.5
  6136.5  326.16    6151  326.43  6165.4   328.3  6229.6  329.24  6345.7  333.76
#Mann= 9 ,-1 , 0
  3860.7     .05       0  3980.1     .08       0  4066.5     .05       0
  4747.9      .1       0  4835.6     .05       0  4875.8      .1       0
  4989.4     .05       0  5023.8     .03       0  5029.8     .05       0
Bank Sta=4962.6,5111.8
XS Rating Curve= 0 ,0
Exp/Cntr=0.3,0.1

Type RM Length L Ch R = 1 ,80107   ,293,293,293
BEGIN DESCRIPTION:
VATOSS GULLY 113.0
END DESCRIPTION:
XS GIS Cut Line= 2
      2289260.18      13360861.4      2287281.89     13362449.24
#Sta/Elev= 30
  3829.4  344.09  4133.8  335.16    4241  333.44  4410.6  328.48  4546.6  326.46
  4660.2  322.74  4730.7   321.9  4817.1  316.94  4922.7  313.17  4951.5  312.05
  5055.7  311.25  5058.4  310.75  5061.7  311.25  5079.5  313.51  5172.3   314.6
  5378.7  313.47  5549.9  313.82  5649.2  314.95  5655.6  315.89    5678   316.2
  5713.2  315.89  5843.9  319.42  5940.4  322.45  5969.2  324.55  6039.6  325.78
    6062  327.23  6103.6  327.72  6140.4  329.94    6231  332.28  6366.1  337.79
#Mann= 5 ,-1 , 0
  3829.4     .05       0  5055.7     .03       0  5061.7     .05       0
  5843.9      .1       0    6231     .05       0
Bank Sta=4922.7,5079.5
XS Rating Curve= 0 ,0
Exp/Cntr=0.3,0.1

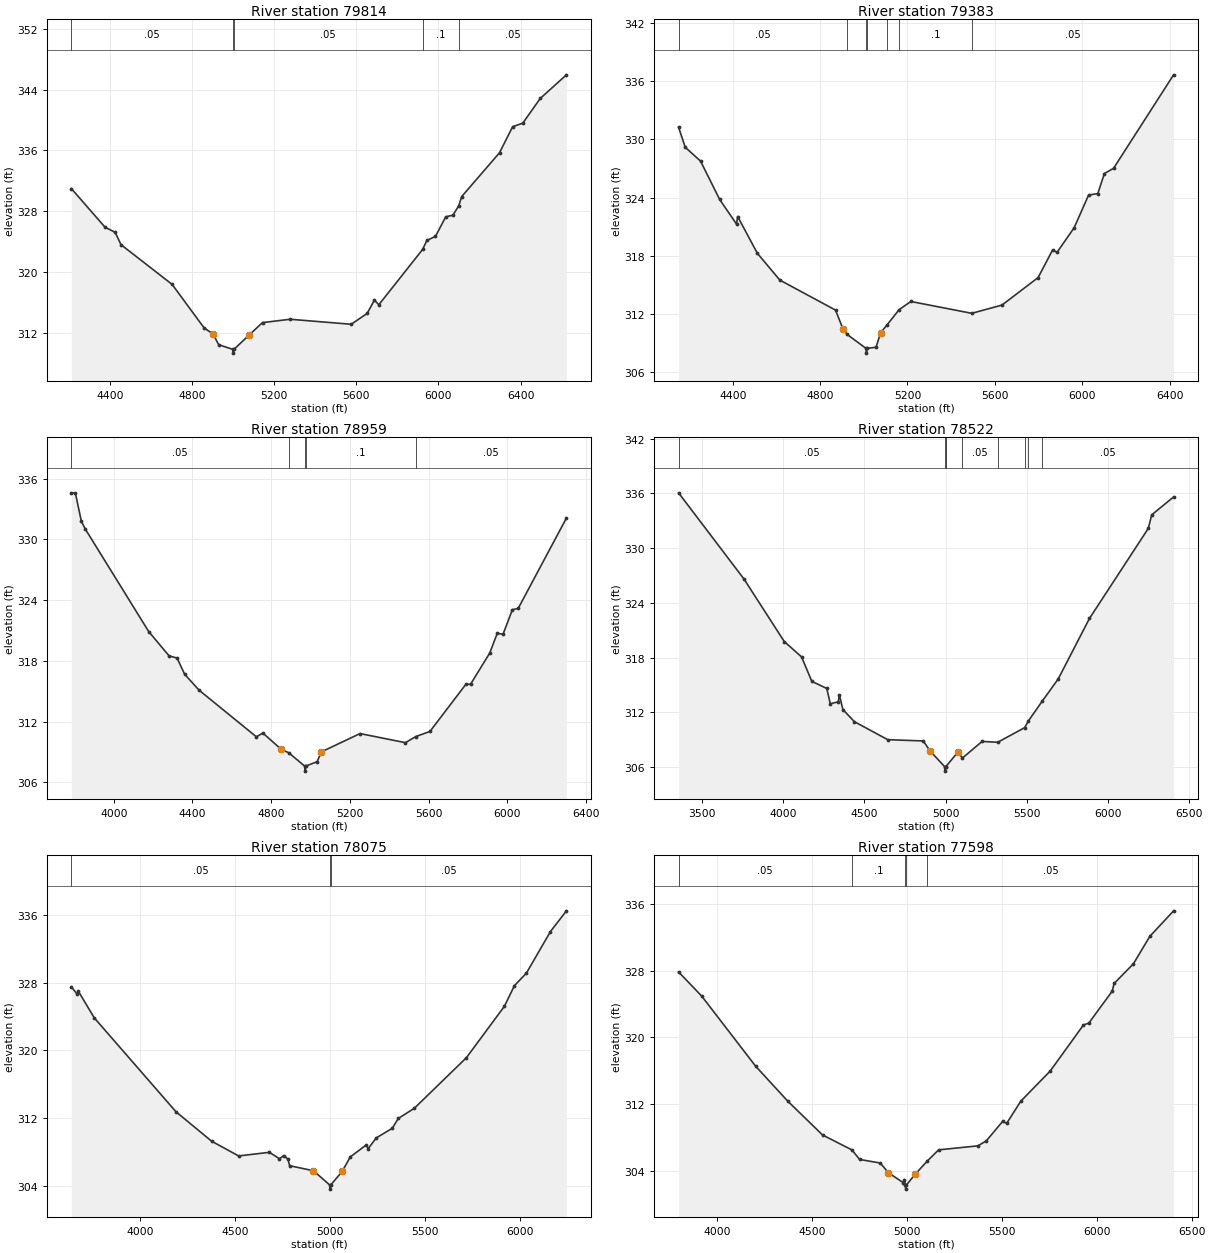
Type RM Length L Ch R = 1 ,79814   ,431,431,431
BEGIN DESCRIPTION:
VATOSS GULLY 112.0
END DESCRIPTION:
XS GIS Cut Line= 3
       2288737.7     13360896.88      2288137.72     13361396.85
       2287037.7     13362596.87
#Sta/Elev= 30
  4213.7  330.96    4377  325.89  4426.5  325.21  4455.1  323.58  4703.8  318.35
    4860   312.6  4902.9  311.83  4930.3  310.41  4998.8   309.8  5001.5   309.3
  5004.8   309.8  5079.5  311.71  5143.6  313.32    5278  313.76  5575.2   313.1
  5652.9  314.53  5688.1  316.28  5709.7  315.67  5922.8  322.96  5943.4  324.14
  5985.3  324.68  6035.2  327.25  6070.4  327.47  6098.6  328.71  6112.9  329.92
    6297  335.69  6360.8  339.12  6410.1  339.58  6495.2  342.84  6622.6  345.95
#Mann= 5 ,-1 , 0
  4213.7     .05       0  4998.8     .03       0  5004.8     .05       0
  5922.8      .1       0  6098.6     .05       0
Bank Sta=4902.9,5079.5
XS Rating Curve= 0 ,0
Exp/Cntr=0.3,0.1

Type RM Length L Ch R = 1 ,79383   ,424,424,424
BEGIN DESCRIPTION:
VATOSS GULLY 111.0
END DESCRIPTION:
XS GIS Cut Line= 3
       2288687.7     13360846.86      2287887.72     13361046.85
      2287087.73     13362246.84
#Sta/Elev= 30
  4151.8  331.24  4182.7  329.17  4252.3  327.76  4339.9  323.81  4417.2  321.27
  4422.4  322.05  4512.6  318.26  4615.6   315.5  4870.7  312.41  4904.2  310.49
    4924   309.9  5009.5  308.48  5012.2  307.98  5015.5  308.48    5056  308.58
  5077.1  310.09  5105.9  310.87  5161.5  312.45  5215.3   313.3  5494.3  312.08
  5632.9  312.93  5798.2  315.76  5864.3  318.59  5885.3  318.37  5963.4   320.9
  6029.5  324.26  6071.6  324.41  6101.6  326.47  6143.7  327.01  6418.6  336.64
#Mann= 7 ,-1 , 0
  4151.8     .05       0    4924      .1       0  5009.5     .07       0
  5015.5      .1       0  5105.9     .05       0  5161.5      .1       0
  5494.3     .05       0
Bank Sta=4904.2,5077.1
XS Rating Curve= 0 ,0
Exp/Cntr=0.3,0.1

Type RM Length L Ch R = 1 ,78959   ,437,437,437
BEGIN DESCRIPTION:
VATOSS GULLY 110.0
END DESCRIPTION:
XS GIS Cut Line= 3
       2288787.7     13360596.86      2287587.72     13360796.85
      2286387.75     13361296.84
#Sta/Elev= 30
  3784.7  334.61    3805  334.57  3835.4  331.79  3855.6  331.02  4177.5  320.91
  4281.4   318.5    4322  318.29    4360   316.7  4433.5  315.12    4725  310.51
  4757.9  310.88  4851.7  309.27  4889.7  308.93  4970.3  307.62  4973.1  307.12
  4976.3  307.62  5033.7  308.05  5055.4  309.02    5252  310.83  5482.8  309.93
  5534.9  310.53  5607.4  311.04  5790.4  315.71  5813.7   315.7  5911.2  318.78
  5949.7  320.74  5978.9  320.64  6026.6  323.07  6055.9  323.19  6301.2  332.12
#Mann= 5 ,-1 , 0
  3784.7     .05       0  4889.7      .1       0  4970.3     .07       0
  4976.3      .1       0  5534.9     .05       0
Bank Sta=4851.7,5055.4
XS Rating Curve= 0 ,0
Exp/Cntr=0.3,0.1

Type RM Length L Ch R = 1 ,78522   ,447,447,447
BEGIN DESCRIPTION:
VATOSS GULLY 109.0
END DESCRIPTION:
XS GIS Cut Line= 3
       2288537.7     13359346.87      2287337.72     13360446.85
      2286237.74     13361346.84
#Sta/Elev= 30
  3355.7  336.06  3759.3  326.59  4006.8  319.75  4113.2  318.07  4176.7  315.38
  4268.6  314.61  4290.2  312.93  4339.5  313.14  4346.3  313.91  4367.9  312.29
  4438.8  310.96  4644.1  308.99    4863  308.85  4905.6  307.74  4994.2  306.04
  4996.9  305.54  5000.2  306.04  5002.4  306.04  5075.4  307.61  5104.6  306.98
  5225.5   308.8  5321.2   308.7  5487.6  310.31  5510.7  311.05    5595  313.19
  5694.2  315.65  5886.6  322.28  6249.1  332.16  6269.9  333.64  6404.8  335.61
#Mann= 9 ,-1 , 0
  3355.7     .05       0  4994.2     .03       0  5000.2     .05       0
  5002.4      .1       0  5104.6     .05       0  5321.2      .1       0
  5487.6     .05       0  5510.7      .1       0    5595     .05       0
Bank Sta=4905.6,5075.4
XS Rating Curve= 0 ,0
Exp/Cntr=0.3,0.1

Type RM Length L Ch R = 1 ,78075   ,477,477,477
BEGIN DESCRIPTION:
VATOSS GULLY 108.0
END DESCRIPTION:
XS GIS Cut Line= 3
       2288237.7     13359546.87      2287037.72     13360146.85
      2285837.75     13360546.85
#Sta/Elev= 30
  3637.7   327.5  3668.4  326.63    3674     327  3757.9  323.85  4188.3  312.75
  4375.6  309.28  4518.1  307.53  4680.2  307.96  4733.3   307.2  4755.7  307.57
  4778.1  307.15  4786.5  306.38  4912.2  305.78  4997.4  304.11  5000.1  303.61
  5003.4  304.11  5063.6  305.71  5105.8  307.41  5190.1  308.83  5200.7   308.4
  5242.8  309.66  5327.2   310.8  5358.8  311.96  5443.1  313.16  5717.2  319.13
  5917.5  325.21  5970.2  327.64  6033.4  329.13  6159.9  334.04  6244.2  336.49
#Mann= 3 ,-1 , 0
  3637.7     .05       0  4997.4     .03       0  5003.4     .05       0
Bank Sta=4912.2,5063.6
XS Rating Curve= 0 ,0
Exp/Cntr=0.3,0.1

Type RM Length L Ch R = 1 ,77598   ,455,455,455
BEGIN DESCRIPTION:
VATOSS GULLY 107.0
END DESCRIPTION:
XS GIS Cut Line= 3
      2288237.71     13359496.86      2287037.72     13359696.85
      2285837.71     13360396.86
#Sta/Elev= 30
  3799.1  327.84  3920.7  324.95  4204.6  316.54  4374.4  312.33  4556.9  308.29
  4711.8  306.49  4752.1  305.35    4861  304.92  4904.1  303.75  4982.7  302.55
  4987.8  302.94  4992.4  302.29  4995.1  301.79  4998.4  302.29    5045  303.58
  5108.2  305.16  5168.2   306.5  5374.5  306.98  5418.8  307.57  5504.8  309.91
  5526.3  309.68  5600.7  312.34  5755.3  315.95  5930.2  321.47  5958.8  321.71
    6082  325.54  6091.9  326.46  6193.6  328.82  6279.6   332.1  6404.9  335.17
#Mann= 5 ,-1 , 0
  3799.1     .05       0  4711.8      .1       0  4992.4     .07       0
  4998.4      .1       0  5108.2     .05       0
Bank Sta=4904.1,5045
XS Rating Curve= 0 ,0
Exp/Cntr=0.3,0.1