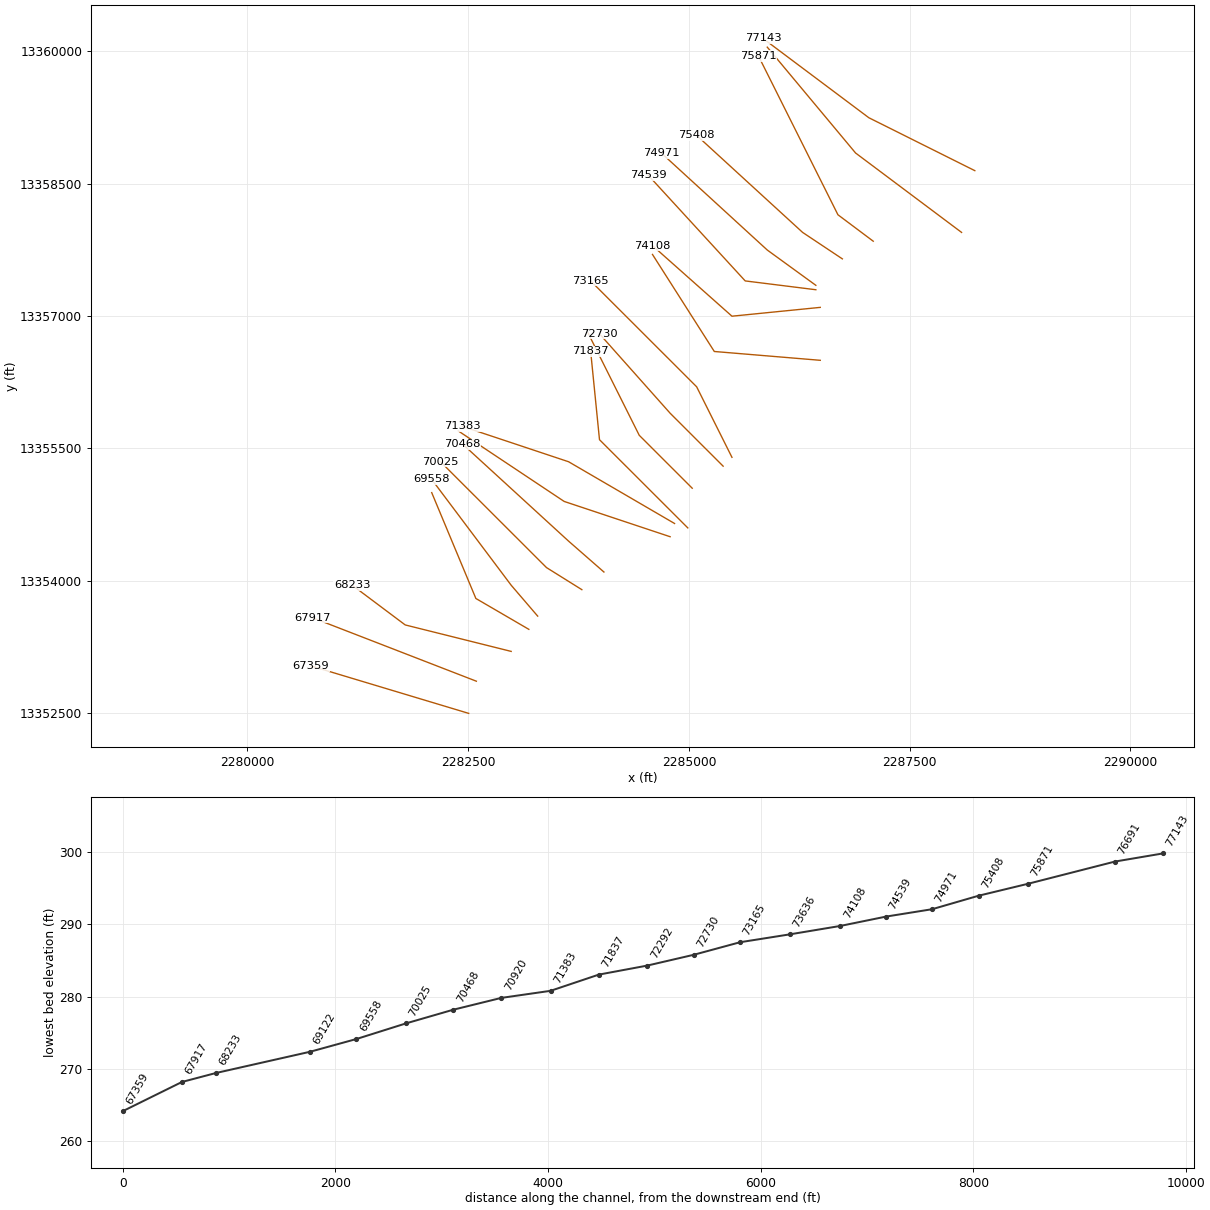
HEC-RAS study VATOSS GULLY.prj: VATOSS GULLY Base Level Engineering

--- VATOSS GULLY.g01 (geometry) --- (continued)

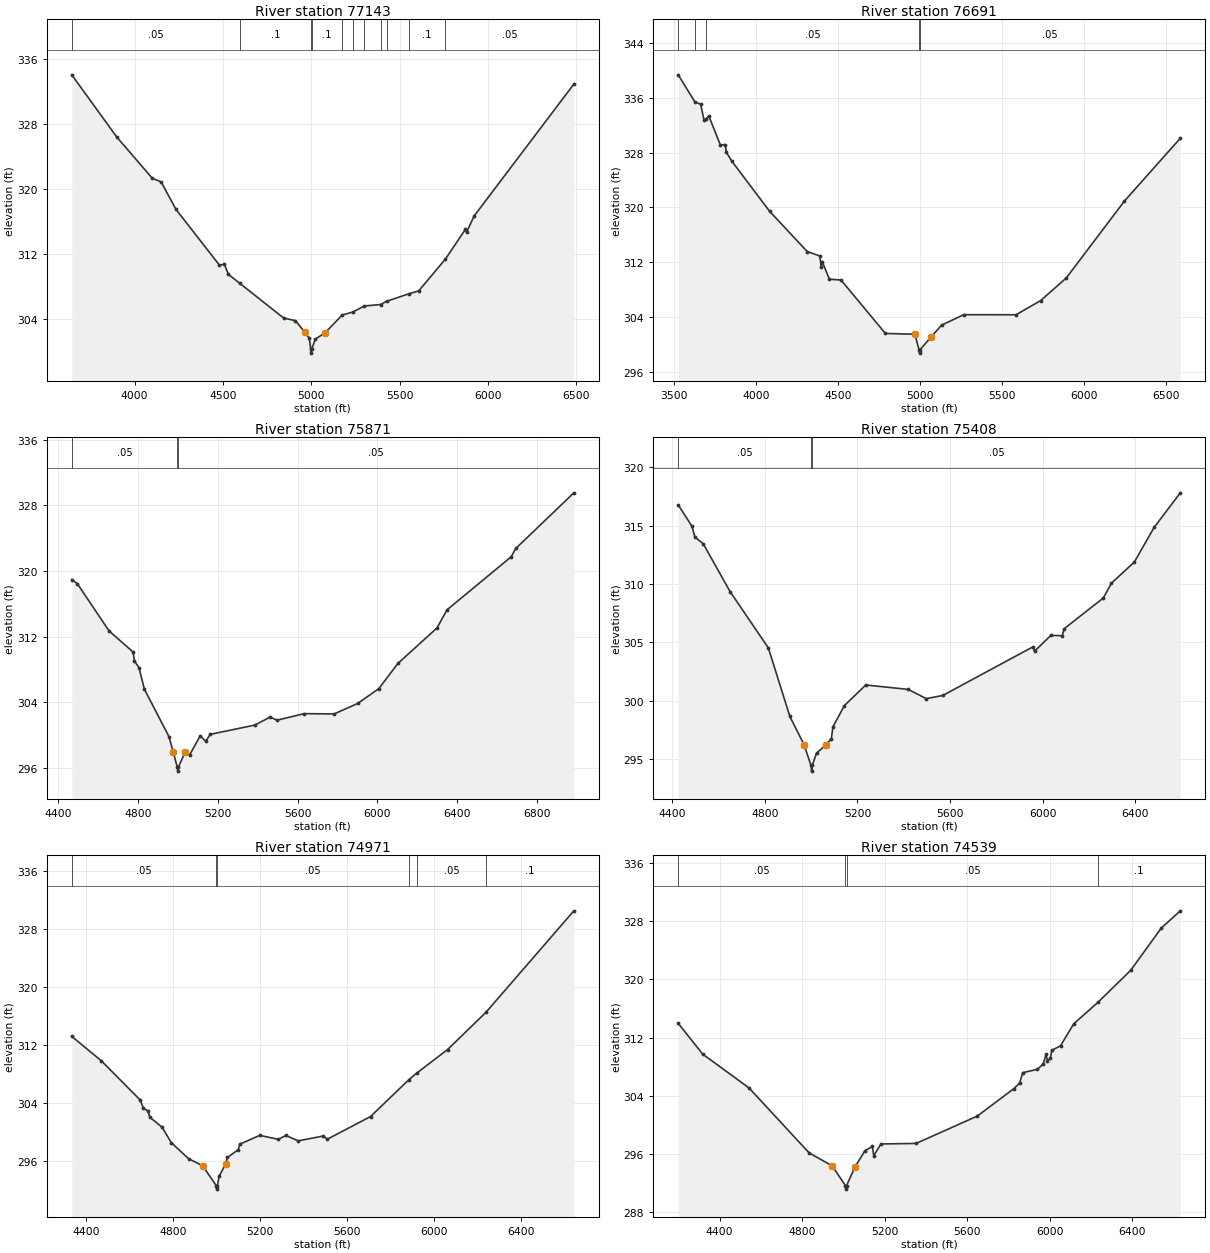
Type RM Length L Ch R = 1 ,77143   ,452,452,452
BEGIN DESCRIPTION:
VATOSS GULLY 106.0
END DESCRIPTION:
XS GIS Cut Line= 3
      2288237.74     13358646.85      2287037.72     13359246.85
      2285837.69     13360146.88
#Sta/Elev= 30
  3644.4  334.02  3898.8  326.39    4100  321.32  4150.3  320.87  4234.2   317.5
  4480.2  310.65  4508.1  310.77  4530.5  309.53  4596.5   308.4  4843.5  304.16
  4910.6  303.83  4963.7  302.41  4989.2  301.66  4996.6  300.35  4999.4  299.85
  5002.6  300.35  5022.5  301.56  5078.8  302.36    5175  304.53  5234.9  304.89
  5300.6  305.64  5393.1  305.82  5426.2  306.21  5551.4  307.13  5607.9  307.49
  5759.4   311.4  5872.5  315.06  5878.8   314.7  5922.5  316.71  6486.1  332.88
#Mann= 11 ,-1 , 0
  3644.4     .05       0  4596.5      .1       0  4996.6     .07       0
  5002.6      .1       0    5175     .05       0  5234.9      .1       0
  5300.6     .05       0  5393.1      .1       0  5426.2     .05       0
  5551.4      .1       0  5759.4     .05       0
Bank Sta=4963.7,5078.8
XS Rating Curve= 0 ,0
Exp/Cntr=0.3,0.1

Type RM Length L Ch R = 1 ,76691   ,820,820,820
BEGIN DESCRIPTION:
VATOSS GULLY 105.0
END DESCRIPTION:
XS GIS Cut Line= 3
      2288087.72     13357946.86      2286887.72     13358846.85
      2285887.75     13360046.82
#Sta/Elev= 30
  3524.4  339.34  3625.3  335.41  3660.9  335.04  3681.7  332.74  3692.1  332.83
  3710.9  333.34  3781.7  329.08  3810.9  329.17  3817.1  328.07  3852.5   326.7
  4081.7  319.42  4310.9  313.55  4387.9   312.9  4396.3  311.34  4402.5  312.08
  4446.3  309.51  4517.1  309.39  4787.9  301.59  4967.1  301.48  4993.3  299.22
    4996  298.72  4999.3  299.22  5066.7  301.09  5130.5  302.81  5265.9  304.33
  5584.8  304.32  5734.5  306.39  5890.7  309.68    6246  320.93  6586.4  330.08
#Mann= 5 ,-1 , 0
  3524.4     .05       0  3625.3      .1       0  3692.1     .05       0
  4993.3     .03       0  4999.3     .05       0
Bank Sta=4967.1,5066.7
XS Rating Curve= 0 ,0
Exp/Cntr=0.3,0.1

Type RM Length L Ch R = 1 ,75871   ,463,463,463
BEGIN DESCRIPTION:
VATOSS GULLY 104.0
END DESCRIPTION:
XS GIS Cut Line= 3
      2287087.72     13357846.85      2286687.72     13358146.85
      2285787.71     13359946.89
#Sta/Elev= 30
  4470.1  318.95  4498.2  318.46  4656.6  312.71  4777.4  310.13  4783.6  309.06
  4806.6  308.21  4833.6   305.6  4956.6  299.83  4978.5   297.9  4997.9  296.13
  5000.6  295.63  5003.9  296.13  5037.2  297.94  5059.5  297.59  5112.7  299.92
  5140.6  299.27    5163  300.11  5386.6  301.24    5462  302.21  5498.4  301.84
  5632.5  302.63  5783.5   302.6  5900.9  303.87  6007.1  305.69  6102.1  308.75
  6297.8  313.07  6348.1  315.28  6669.5  321.75  6691.9  322.75  6982.6  329.53
#Mann= 3 ,-1 , 0
  4470.1     .05       0  4997.9    .035       0  5003.9     .05       0
Bank Sta=4978.5,5037.2
XS Rating Curve= 0 ,0
Exp/Cntr=0.3,0.1

Type RM Length L Ch R = 1 ,75408   ,437,437,437
BEGIN DESCRIPTION:
VATOSS GULLY 103.0
END DESCRIPTION:
XS GIS Cut Line= 3
      2286737.74     13357646.84      2286287.72     13357946.85
      2285087.75     13359046.83
#Sta/Elev= 30
  4425.7  316.78  4484.3  314.98  4497.8  314.03  4533.9  313.45  4649.6  309.36
  4814.8  304.54    4908  298.66  4969.9  296.21    4999  294.48  5001.8  293.98
    5005  294.48    5023  295.52  5065.5  296.26  5087.1  296.76  5093.9  297.77
  5143.2  299.59  5235.7  301.36  5419.5  300.98  5497.2  300.19  5568.1  300.46
  5957.2  304.62  5964.6  304.25  6035.5  305.61  6084.8  305.58  6092.2  306.17
  6261.8  308.81  6296.9  310.08  6396.2   311.9  6481.3  314.86  6594.4  317.82
#Mann= 3 ,-1 , 0
  4425.7     .05       0    4999     .03       0    5005     .05       0
Bank Sta=4969.9,5065.5
XS Rating Curve= 0 ,0
Exp/Cntr=0.3,0.1

Type RM Length L Ch R = 1 ,74971   ,432,432,432
BEGIN DESCRIPTION:
VATOSS GULLY 102.0
END DESCRIPTION:
XS GIS Cut Line= 3
      2286437.74     13357346.84      2285887.72     13357746.85
       2284687.7     13358846.87
#Sta/Elev= 30
  4335.6  313.21  4471.6  309.84  4650.5  304.41  4665.2  303.26  4686.1  302.93
  4694.2  302.05    4751  300.66  4793.1  298.53  4872.3  296.32  4937.3  295.34
  4999.2  292.61  5001.9  292.11  5005.2  292.61  5012.6  293.87  5043.7  295.63
  5051.1  296.49  5100.5  297.54  5107.9  298.32  5199.8  299.54  5284.8  298.99
    5320  299.52  5376.7  298.78  5490.2  299.44  5511.1  299.02  5709.1  302.14
    5885  307.22  5924.5  308.21    6063  311.39  6239.6  316.54  6643.6  330.56
#Mann= 6 ,-1 , 0
  4335.6     .05       0  4999.2    .035       0  5005.2     .05       0
    5885      .1       0  5924.5     .05       0  6239.6      .1       0
Bank Sta=4937.3,5043.7
XS Rating Curve= 0 ,0
Exp/Cntr=0.3,0.1

Type RM Length L Ch R = 1 ,74539   ,431,431,431
BEGIN DESCRIPTION:
VATOSS GULLY 101.0
END DESCRIPTION:
XS GIS Cut Line= 3
      2286437.76     13357296.85      2285637.72     13357396.85
      2284537.75     13358596.82
#Sta/Elev= 30
  4199.3  313.95  4317.8  309.71    4542  305.06  4834.2  296.08  4945.1  294.31
  5009.7  291.59  5012.4  291.09  5015.7  291.59  5055.2   294.1  5104.5  296.39
  5140.3  296.97  5147.1  295.71  5182.2  297.32  5352.4  297.39  5649.6  301.17
  5826.6  304.95    5855  305.74  5869.1  307.15  5940.1  307.61  5968.4  308.34
  5982.3  309.68  5989.4  308.78  6003.6  309.13  6010.3  310.22  6052.9  310.87
    6117   313.9  6235.2  316.88  6392.7  321.26  6541.3   327.1  6633.4  329.47
#Mann= 4 ,-1 , 0
  4199.3     .05       0  5009.7    .035       0  5015.7     .05       0
  6235.2      .1       0
Bank Sta=4945.1,5055.2
XS Rating Curve= 0 ,0
Exp/Cntr=0.3,0.1

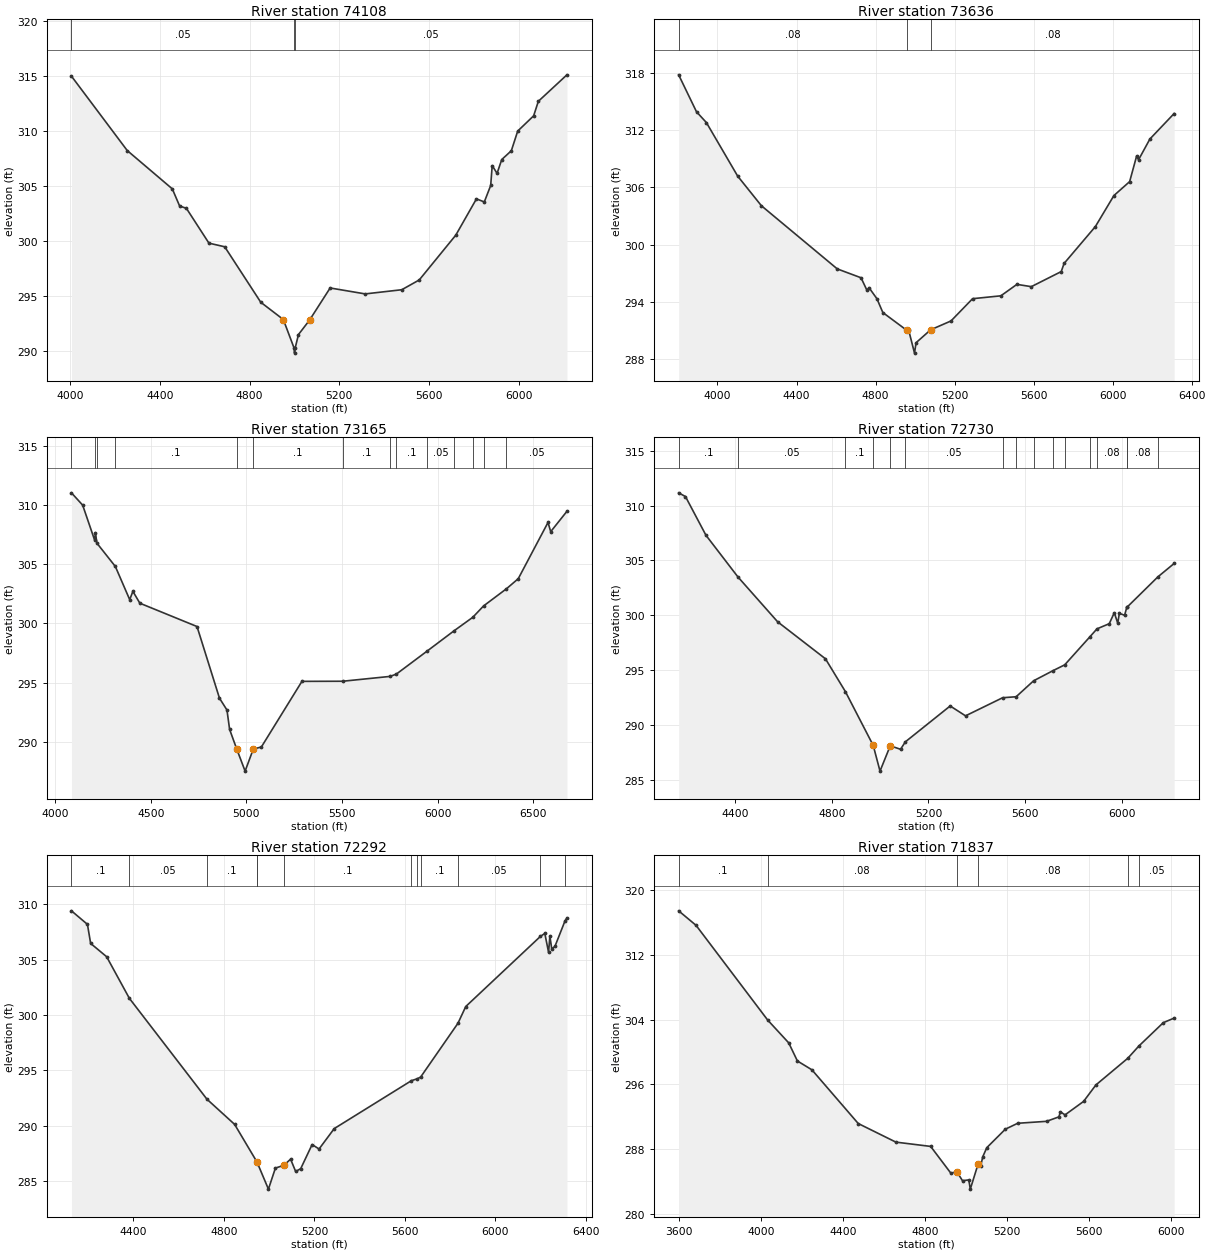
Type RM Length L Ch R = 1 ,74108   ,472,472,472
BEGIN DESCRIPTION:
VATOSS GULLY 100.0
END DESCRIPTION:
XS GIS Cut Line= 3
      2286487.68     13357096.85      2285487.72     13356996.85
      2284587.72     13357796.85
#Sta/Elev= 30
  4005.6     315  4254.3  308.23  4455.3  304.74  4487.9  303.18  4518.1  302.97
  4618.6   299.8  4688.9  299.47  4849.7  294.42  4950.2  292.85  4997.5  290.29
  5000.2  289.79  5003.5  290.29  5017.7  291.48    5067  292.79    5159  295.72
  5315.3  295.18  5478.4  295.56  5556.2  296.45  5719.2  300.53  5811.2  303.83
  5846.3  303.55  5874.8  305.05  5881.5  306.86  5903.2  306.15  5924.1  307.41
  5966.8  308.21  5995.2     310  6066.3  311.39  6087.2  312.71  6214.7  315.12
#Mann= 3 ,-1 , 0
  4005.6     .05       0  4997.5    .035       0  5003.5     .05       0
Bank Sta=4950.2,5067
XS Rating Curve= 0 ,0
Exp/Cntr=0.3,0.1

Type RM Length L Ch R = 1 ,73636   ,471,471,471
BEGIN DESCRIPTION:
VATOSS GULLY 99.0
END DESCRIPTION:
XS GIS Cut Line= 3
      2286487.76     13356496.85      2285287.72     13356596.85
      2284587.74     13357696.82
#Sta/Elev= 30
  3803.4  317.77  3893.8   313.9  3943.9  312.77    4102  307.17  4222.4  304.06
  4606.2  297.45  4726.6  296.52  4756.7   295.2  4766.8  295.49  4806.9  294.33
    4837  292.88  4957.4  291.03  4967.5  291.05  4997.3  288.63  5005.1  289.72
  5078.7  291.07    5182     292  5291.2  294.33  5434.3  294.63  5515.6  295.83
  5588.4  295.59    5740  297.17  5754.3  298.02  5912.7  301.88  6006.6  305.13
  6086.2  306.59  6121.8  309.29  6131.1  308.87  6188.7  311.05  6311.4  313.72
#Mann= 3 , 0 , 0
  3803.4     .08       0  4957.4     .05       0  5078.7     .08       0
Bank Sta=4957.4,5078.7
XS Rating Curve= 0 ,0
Exp/Cntr=0.3,0.1

Type RM Length L Ch R = 1 ,73165   ,435,435,435
BEGIN DESCRIPTION:
VATOSS GULLY 98.0
END DESCRIPTION:
XS GIS Cut Line= 3
      2285487.72     13355396.86      2285087.72     13356196.85
       2283887.7     13357396.87
#Sta/Elev= 30
  4084.8  311.03  4143.5  309.99  4205.8  307.05  4210.6  307.67  4217.5  306.79
  4314.5  304.81  4389.5  302.01  4406.2  302.71  4442.6  301.71  4741.6  299.74
    4859  293.69  4898.2  292.69  4912.1  291.05  4948.5  289.43  4993.1  287.53
  5035.8  289.39  5078.2  289.57  5290.3  295.11  5503.4  295.12  5752.1  295.53
  5784.7  295.73  5943.6  297.65  6086.8  299.39  6183.9  300.52  6240.4  301.48
  6360.1  302.93  6421.7  303.78  6577.3  308.53  6591.4  307.75  6676.3  309.47
#Mann= 14 ,-1 , 0
  4084.8      .1       0  4205.8     .05       0  4217.5      .1       0
  4314.5      .1       0  4948.5     .07       0  5035.8      .1       0
  5503.4      .1       0  5752.1     .05       0  5784.7      .1       0
  5943.6     .05       0  6086.8      .1       0  6183.9     .05       0
  6240.4      .1       0  6360.1     .05       0
Bank Sta=4948.5,5035.8
XS Rating Curve= 0 ,0
Exp/Cntr=0.3,0.1

Type RM Length L Ch R = 1 ,72730   ,438,438,438
BEGIN DESCRIPTION:
VATOSS GULLY 97.0
END DESCRIPTION:
XS GIS Cut Line= 3
      2285387.75     13355296.82      2284787.72     13355896.85
      2283987.74     13356796.83
#Sta/Elev= 30
    4165  311.16  4193.3  310.82  4278.2  307.29  4410.7  303.49  4575.2   299.4
  4773.2  296.03  4855.8  293.04  4971.1  288.13  4999.2  285.79  5041.6   288.1
  5084.2  287.78  5104.2  288.46  5289.9  291.73  5353.5  290.83  5507.1  292.48
  5563.1  292.57  5635.8  294.03    5716  294.95  5764.4  295.48  5868.9  298.04
    5898  298.76  5948.9  299.23  5969.8  300.23    5984  299.28  5990.7  300.17
  6012.4     300  6021.7  300.73  6021.9  300.72  6150.4   303.5  6217.7  304.72
#Mann= 16 ,-1 , 0
    4165      .1       0  4410.7     .05       0  4855.8      .1       0
  4971.1     .07       0  5041.6      .1       0  5104.2     .05       0
  5507.1     .08       0  5563.1      .1       0  5635.8     .08       0
    5716      .1       0  5764.4     .08       0  5868.9     .05       0
    5898     .08       0  6021.7     .05       0  6021.9     .08       0
  6150.4      .1       0
Bank Sta=4971.1,5041.6
XS Rating Curve= 0 ,0
Exp/Cntr=0.3,0.1

Type RM Length L Ch R = 1 ,72292   ,455,455,455
BEGIN DESCRIPTION:
VATOSS GULLY 96.0
END DESCRIPTION:
XS GIS Cut Line= 3
      2285037.73     13355046.84      2284437.72     13355646.85
      2283837.71     13356846.87
#Sta/Elev= 30
  4125.9  309.39  4196.6  308.17  4210.8  306.45  4281.5  305.25  4381.9   301.5
  4724.9   292.4  4847.2  290.13  4946.2  286.73  4996.6  284.29  5027.5  286.19
  5063.9  286.43  5094.6  286.99    5117  285.88  5139.4  286.14  5189.7  288.31
  5220.4  287.91  5287.5  289.75  5628.6  294.07  5655.5  294.25  5669.5   294.4
  5834.4  299.25  5868.9  300.76  6199.2  307.09  6218.3  307.35    6235  305.64
  6240.6  307.12    6249  305.95    6263  306.18  6307.9   308.5  6316.1  308.75
#Mann= 12 ,-1 , 0
  4125.9      .1       0  4381.9     .05       0  4724.9      .1       0
  4946.2     .05       0  4946.2     .07       0  5063.9      .1       0
  5628.6      .1       0  5655.5     .05       0  5669.5      .1       0
  5834.4     .05       0  6199.2     .08       0  6307.9      .1       0
Bank Sta=4946.2,5063.9
XS Rating Curve= 0 ,0
Exp/Cntr=0.3,0.1

Type RM Length L Ch R = 1 ,71837   ,454,454,454
BEGIN DESCRIPTION:
VATOSS GULLY 95.0
END DESCRIPTION:
XS GIS Cut Line= 3
      2284987.73     13354596.85      2283987.72     13355596.85
      2283887.72     13356596.84
#Sta/Elev= 30
  3597.1  317.44    3682  315.65  4031.8  303.94  4134.5  301.12  4176.9  298.88
  4247.7  297.79  4473.9  291.15  4657.8  288.85  4827.5  288.32  4926.5     285
  4954.8  285.21    4983  284.08  5013.8  284.18  5021.1  283.04  5059.1  286.14
  5071.6  285.84  5081.7  287.03  5101.8  288.17  5192.2  290.45  5252.5  291.18
  5393.2  291.42  5453.5  291.97  5461.1  292.59  5483.7  292.22  5574.1  293.88
  5634.4  295.92  5790.2  299.22  5844.1  300.73  5963.5  303.62  6016.3  304.18
#Mann= 6 ,-1 , 0
  3597.1      .1       0  4031.8     .08       0  4954.8     .05       0
  5059.1     .08       0  5790.2      .1       0  5844.1     .05       0
Bank Sta=4954.8,5059.1
XS Rating Curve= 0 ,0
Exp/Cntr=0.3,0.1

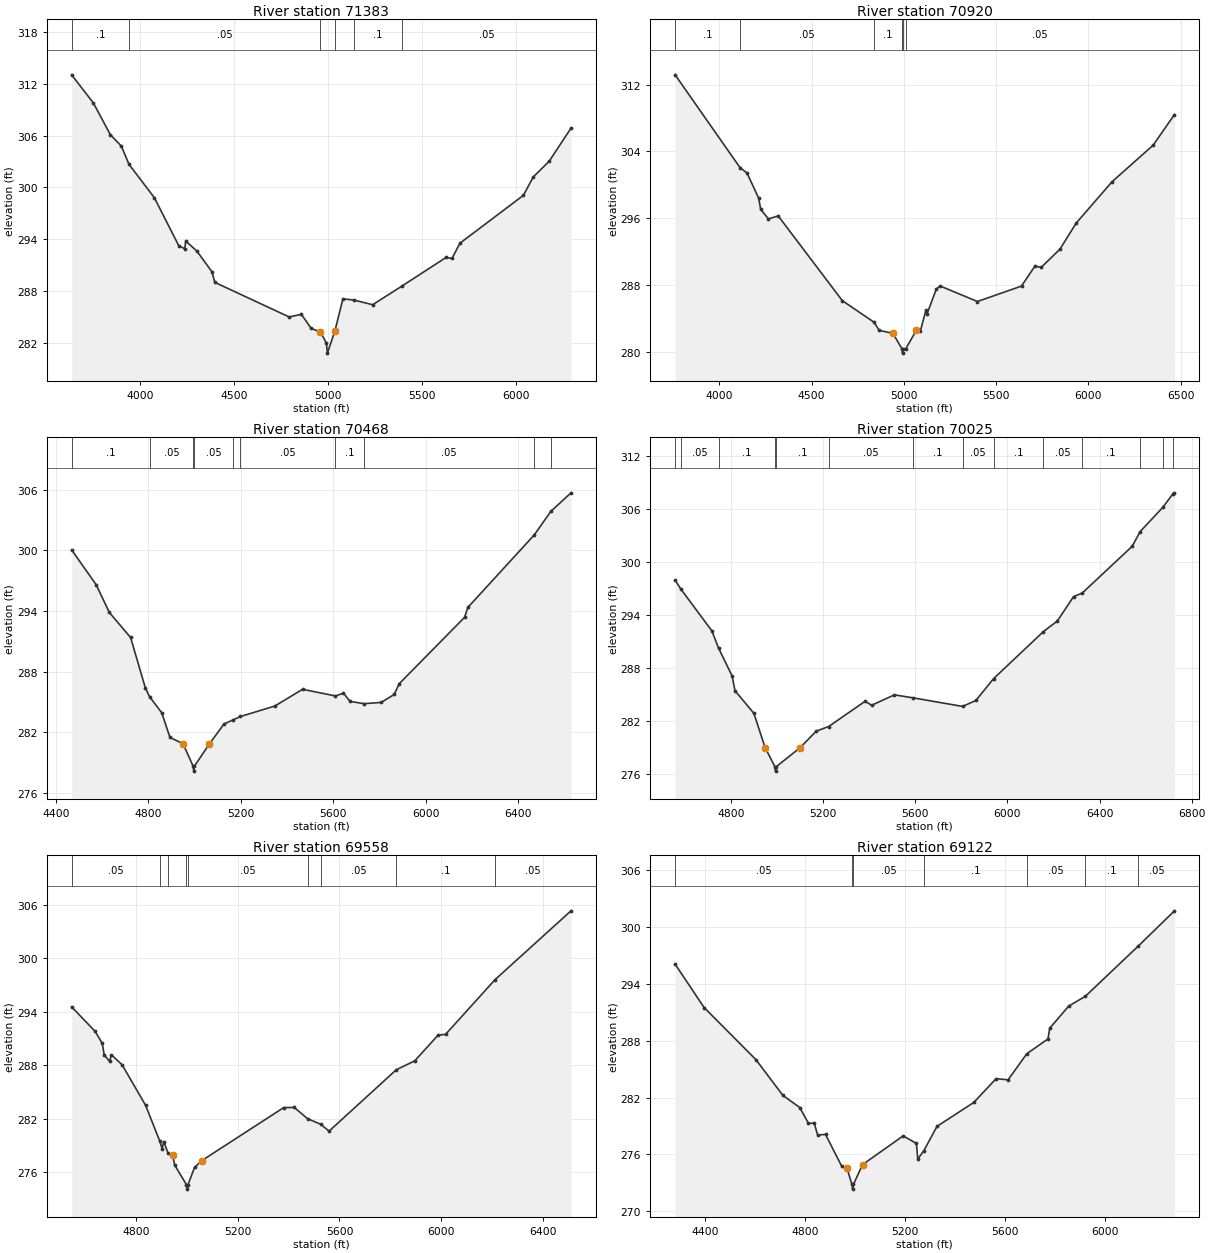
Type RM Length L Ch R = 1 ,71383   ,463,463,463
BEGIN DESCRIPTION:
VATOSS GULLY 94.0
END DESCRIPTION:
XS GIS Cut Line= 3
      2284837.73     13354646.85      2283637.72     13355346.85
      2282437.69     13355746.87
#Sta/Elev= 30
  3636.7  313.05  3752.5  309.78  3842.2  306.12  3900.9  304.79  3941.5  302.68
  4076.6   298.8  4206.1  293.24  4237.5  292.89  4243.3  293.78    4302  292.63
  4382.2  290.23  4397.9  288.99  4793.2  284.98  4857.7  285.29  4910.2  283.65
  4959.4  283.24  4990.8  281.96  4996.3  280.79  5036.5   283.4  5078.7  287.09
    5137  286.94  5236.8   286.4  5391.4  288.55  5626.8  291.88  5658.4  291.76
  5700.6  293.53  6037.9  299.08  6090.6  301.22  6174.9  303.03  6290.9  306.87
#Mann= 6 ,-1 , 0
  3636.7      .1       0  3941.5     .05       0  4959.4    .035       0
  5036.5     .05       0    5137      .1       0  5391.4     .05       0
Bank Sta=4959.4,5036.5
XS Rating Curve= 0 ,0
Exp/Cntr=0.3,0.1

Type RM Length L Ch R = 1 ,70920   ,452,452,452
BEGIN DESCRIPTION:
VATOSS GULLY 93.0
END DESCRIPTION:
XS GIS Cut Line= 3
       2284787.7     13354496.86      2283587.72     13354896.85
      2282387.73     13355696.85
#Sta/Elev= 30
  3759.8  313.18  4111.4  302.06  4149.8   301.4    4213  298.37  4223.6  297.06
  4265.7   295.9  4318.4  296.27  4666.3   286.1  4837.2  283.53  4866.6  282.53
  4940.4  282.19  4990.1  280.31  4992.8  279.81  4996.1  280.31  5010.8  280.36
  5068.3  282.58  5089.3  282.44  5119.3  284.96  5125.3  284.51  5176.4  287.52
  5197.5  287.85  5398.8     286  5637.6  287.85  5709.7  290.22  5745.8  290.12
  5846.5  292.29  5933.6  295.39  6128.9  300.37  6351.2  304.74  6466.9  308.42
#Mann= 6 ,-1 , 0
  3759.8      .1       0  4111.4     .05       0  4837.2      .1       0
  4990.1     .07       0  4996.1      .1       0  5010.8     .05       0
Bank Sta=4940.4,5068.3
XS Rating Curve= 0 ,0
Exp/Cntr=0.3,0.1

Type RM Length L Ch R = 1 ,70468   ,443,443,443
BEGIN DESCRIPTION:
VATOSS GULLY 92.0
END DESCRIPTION:
XS GIS Cut Line= 3
      2284037.74     13354096.84      2283637.72     13354446.85
      2282437.73     13355546.84
#Sta/Elev= 30
  4468.8  300.04  4575.1  296.59  4631.6  293.86  4723.7  291.38  4787.7  286.39
  4805.8  285.53  4858.4  283.94    4894   281.5  4950.5  280.88    4994  278.67
  4996.8  278.17    5000  278.67  5064.2  280.85  5127.7  282.83  5167.3  283.24
  5198.9  283.57  5347.2   284.6  5467.4  286.26  5609.8   285.6  5644.4  285.88
  5672.8  285.06  5733.2  284.84  5807.2  284.96  5863.9  285.75  5884.9   286.8
  6167.9  293.37  6182.1  294.35  6469.4  301.52  6541.2  303.85  6628.2  305.68
#Mann= 10 ,-1 , 0
  4468.8      .1       0  4805.8     .05       0    4994     .03       0
    5000     .05       0  5167.3      .1       0  5198.9     .05       0
  5609.8      .1       0  5733.2     .05       0  6469.4      .1       0
  6541.2     .05       0
Bank Sta=4950.5,5064.2
XS Rating Curve= 0 ,0
Exp/Cntr=0.3,0.1

Type RM Length L Ch R = 1 ,70025   ,467,467,467
BEGIN DESCRIPTION:
VATOSS GULLY 91.0
END DESCRIPTION:
XS GIS Cut Line= 3
      2283787.71     13353896.86      2283387.72     13354146.85
      2282187.75     13355346.82
#Sta/Elev= 30
  4556.7  297.91  4581.6   296.9  4716.5  292.16  4745.5  290.21  4804.3  287.05
  4816.7  285.39  4898.7  282.83  4947.6  278.94    4990  276.78  4992.8  276.28
    4996  276.78  5099.1  278.93  5169.8  280.81  5223.3  281.33  5381.9  284.19
  5410.2  283.74  5509.2  284.92  5590.2  284.58  5805.2  283.61  5862.8  284.28
    5940  286.76  6156.4  292.09  6216.3  293.27    6287  296.04  6324.4  296.44
  6541.6  301.74  6576.4  303.41  6674.6  306.15  6719.6  307.72  6725.4   307.8
#Mann= 14 ,-1 , 0
  4556.7      .1       0  4581.6     .05       0  4745.5      .1       0
    4990     .07       0    4996      .1       0  5223.3     .05       0
  5590.2      .1       0  5805.2     .05       0    5940      .1       0
  6156.4     .05       0  6324.4      .1       0  6576.4     .05       0
  6674.6      .1       0  6719.6     .05       0
Bank Sta=4947.6,5099.1
XS Rating Curve= 0 ,0
Exp/Cntr=0.3,0.1

Type RM Length L Ch R = 1 ,69558   ,436,436,436
BEGIN DESCRIPTION:
VATOSS GULLY 90.0
END DESCRIPTION:
XS GIS Cut Line= 3
      2283287.75     13353596.82      2282987.72     13353946.85
      2282087.73     13355146.84
#Sta/Elev= 30
  4548.2  294.54  4640.4  291.79  4668.4  290.45  4676.1  289.17    4697  288.43
  4704.6  289.15  4746.4  288.05  4838.5  283.51  4894.7  279.47  4903.3  278.66
  4909.9  279.44  4926.2  278.19    4945  277.89  4952.7  276.81  4999.1  274.61
  5001.8  274.11  5005.1  274.61  5031.1  276.55  5059.2   277.3  5381.1  283.25
  5422.8  283.26  5474.8     282  5525.9  281.39  5559.2  280.61  5822.7  287.48
  5895.7  288.49  5987.3  291.37  6016.5  291.45  6210.7  297.58  6509.2   305.3
#Mann= 9 ,-1 , 0
  4548.2     .05       0  4894.7      .1       0  4926.2     .05       0
  4999.1    .035       0  5005.1     .05       0  5474.8      .1       0
  5525.9     .05       0  5822.7      .1       0  6210.7     .05       0
Bank Sta=4945,5059.2
XS Rating Curve= 0 ,0
Exp/Cntr=0.3,0.1

Type RM Length L Ch R = 1 ,69122   ,889,889,889
BEGIN DESCRIPTION:
VATOSS GULLY 89.0
END DESCRIPTION:
XS GIS Cut Line= 3
      2283187.69     13353446.87      2282587.72     13353796.85
      2282087.72     13354996.86
#Sta/Elev= 30
  4281.1   296.1  4396.8  291.52    4604  286.01  4711.5  282.24  4778.9  280.96
  4813.6  279.29  4836.8   279.3  4850.4  278.05  4881.8  278.12  4946.3  274.77
  4967.8  274.54  4987.3  272.84  4990.1  272.34  4993.3  272.84  5029.9  274.93
  5191.8  277.96  5244.9  277.17  5250.3  275.51  5274.8  276.41  5327.2  278.97
    5474  281.49  5563.4  284.01  5611.1  283.88  5685.6  286.63  5770.3   288.2
  5777.4  289.33  5853.2  291.67  5919.6   292.7  6131.5  298.02  6275.7  301.73
#Mann= 7 ,-1 , 0
  4281.1     .05       0  4987.3    .035       0  4993.3     .05       0
  5274.8      .1       0  5685.6     .05       0  5919.6      .1       0
  6131.5     .05       0
Bank Sta=4967.8,5029.9
XS Rating Curve= 0 ,0
Exp/Cntr=0.3,0.1

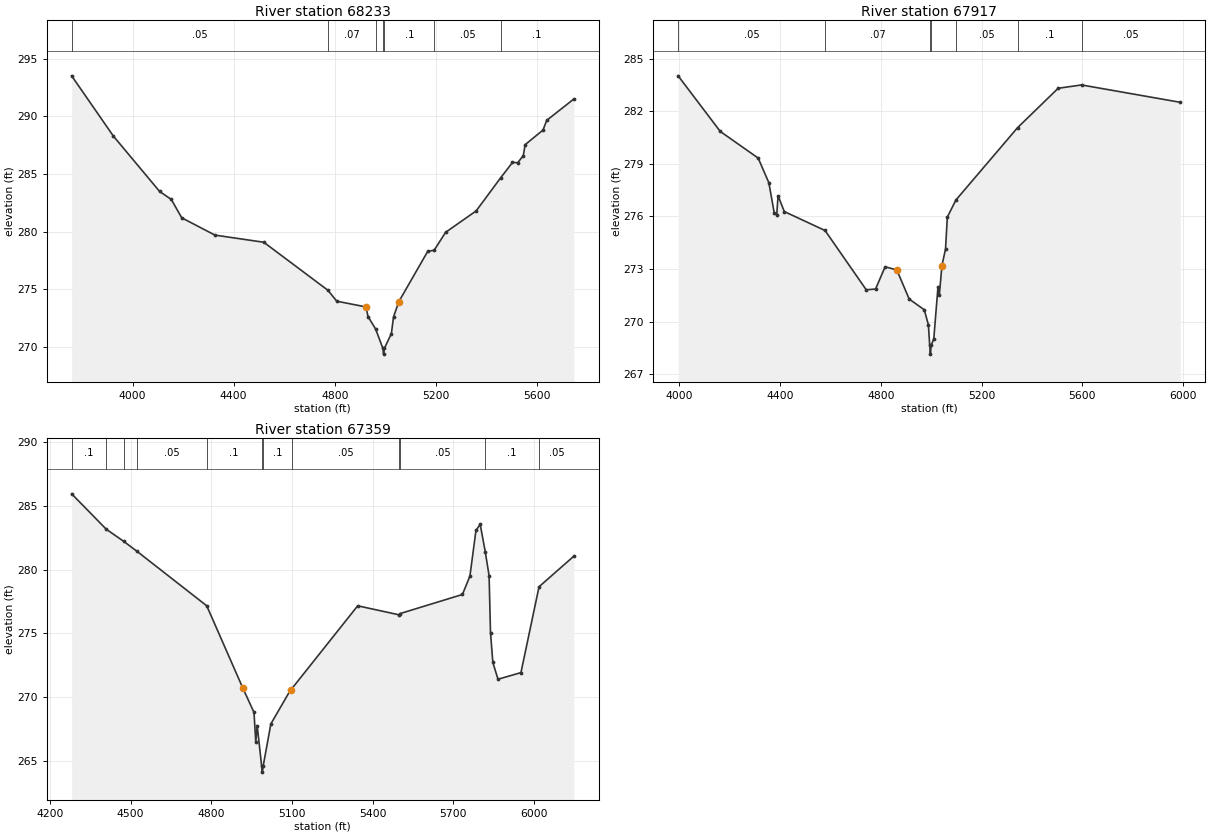
Type RM Length L Ch R = 1 ,68233   ,316,316,316
BEGIN DESCRIPTION:
VATOSS GULLY 88.0
END DESCRIPTION:
XS GIS Cut Line= 3
       2282987.7     13353196.86      2281787.72     13353496.85
      2281187.73     13353946.85
#Sta/Elev= 30
    3759  293.51  3923.9  288.29  4106.9  283.49  4153.3  282.79  4194.5   281.2
  4325.9   279.7  4519.2  279.08  4773.3  274.91  4807.8  273.97  4923.8  273.47
  4931.5  272.64  4961.6  271.56  4990.3  269.88  4993.1  269.38  4996.3  269.88
    5024  271.16  5032.4  272.59  5053.2  273.92  5167.8  278.29  5193.3  278.39
  5238.6  279.94  5359.5   281.8  5456.1  284.66  5503.2     286    5524  285.98
  5545.9  286.59  5553.2  287.54    5624  288.81  5638.6  289.65  5745.9   291.5
#Mann= 7 ,-1 , 0
    3759     .05       0  4773.3     .07       0  4961.6      .1       0
  4990.3     .07       0  4996.3      .1       0  5193.3     .05       0
  5456.1      .1       0
Bank Sta=4923.8,5053.2
XS Rating Curve= 0 ,0
Exp/Cntr=0.3,0.1

Type RM Length L Ch R = 1 ,67917   ,558,558,558
BEGIN DESCRIPTION:
VATOSS GULLY 87.0
END DESCRIPTION:
XS GIS Cut Line= 2
      2282593.48     13352858.81       2280735.9     13353579.27
#Sta/Elev= 30
  3995.9  284.02    4163  280.85  4313.5  279.33    4356  277.92  4377.5  276.18
  4387.2  276.11  4392.5  277.18  4417.1  276.28  4578.8   275.2  4742.2  271.82
  4779.2  271.86  4817.2  273.13  4863.6  272.95  4912.7  271.29  4972.5  270.68
  4988.9  269.82    4994  268.65  4996.8  268.15    5000  268.65  5010.3  269.03
    5027     272  5032.3  271.53  5042.5  273.19  5056.9  274.15  5063.9  275.96
  5098.1  276.94  5342.4  281.06  5503.7  283.31  5596.4   283.5  5988.3  282.51
#Mann= 7 ,-1 , 0
  3995.9     .05       0  4578.8     .07       0    4994     .07       0
    5000     .07       0  5098.1     .05       0  5342.4      .1       0
  5596.4     .05       0
Bank Sta=4863.6,5042.5
XS Rating Curve= 0 ,0
Exp/Cntr=0.3,0.1

Type RM Length L Ch R = 1 ,67359   ,468,468,468
BEGIN DESCRIPTION:
VATOSS GULLY 86.0
END DESCRIPTION:
XS GIS Cut Line= 2
      2282506.67     13352494.22      2280719.46     13353032.12
#Sta/Elev= 30
  4281.2  285.96  4409.7  283.18  4475.1  282.22  4524.2  281.44  4783.3  277.16
  4917.1  270.71  4958.9  268.78  4965.5  266.46  4970.8  267.75  4987.2  264.59
    4990  264.09  4993.2  264.59  5021.6  267.88  5094.7  270.55  5098.4  270.62
  5344.3  277.16  5498.5  276.45  5501.9  276.55  5733.6  278.05  5761.4   279.5
  5783.9  283.09  5799.6  283.56  5818.7  281.37  5832.6  279.53  5837.9  275.05
  5846.6  272.71  5865.7  271.39    5951  271.91  6018.3  278.66  6147.6  281.06
#Mann= 12 ,-1 , 0
  4281.2      .1       0  4409.7     .05       0  4475.1      .1       0
  4524.2     .05       0  4783.3      .1       0  4987.2     .07       0
  4993.2      .1       0  5098.4     .05       0  5498.5      .1       0
  5501.9     .05       0  5818.7      .1       0  6018.3     .05       0
Bank Sta=4917.1,5094.7
XS Rating Curve= 0 ,0
Exp/Cntr=0.3,0.1