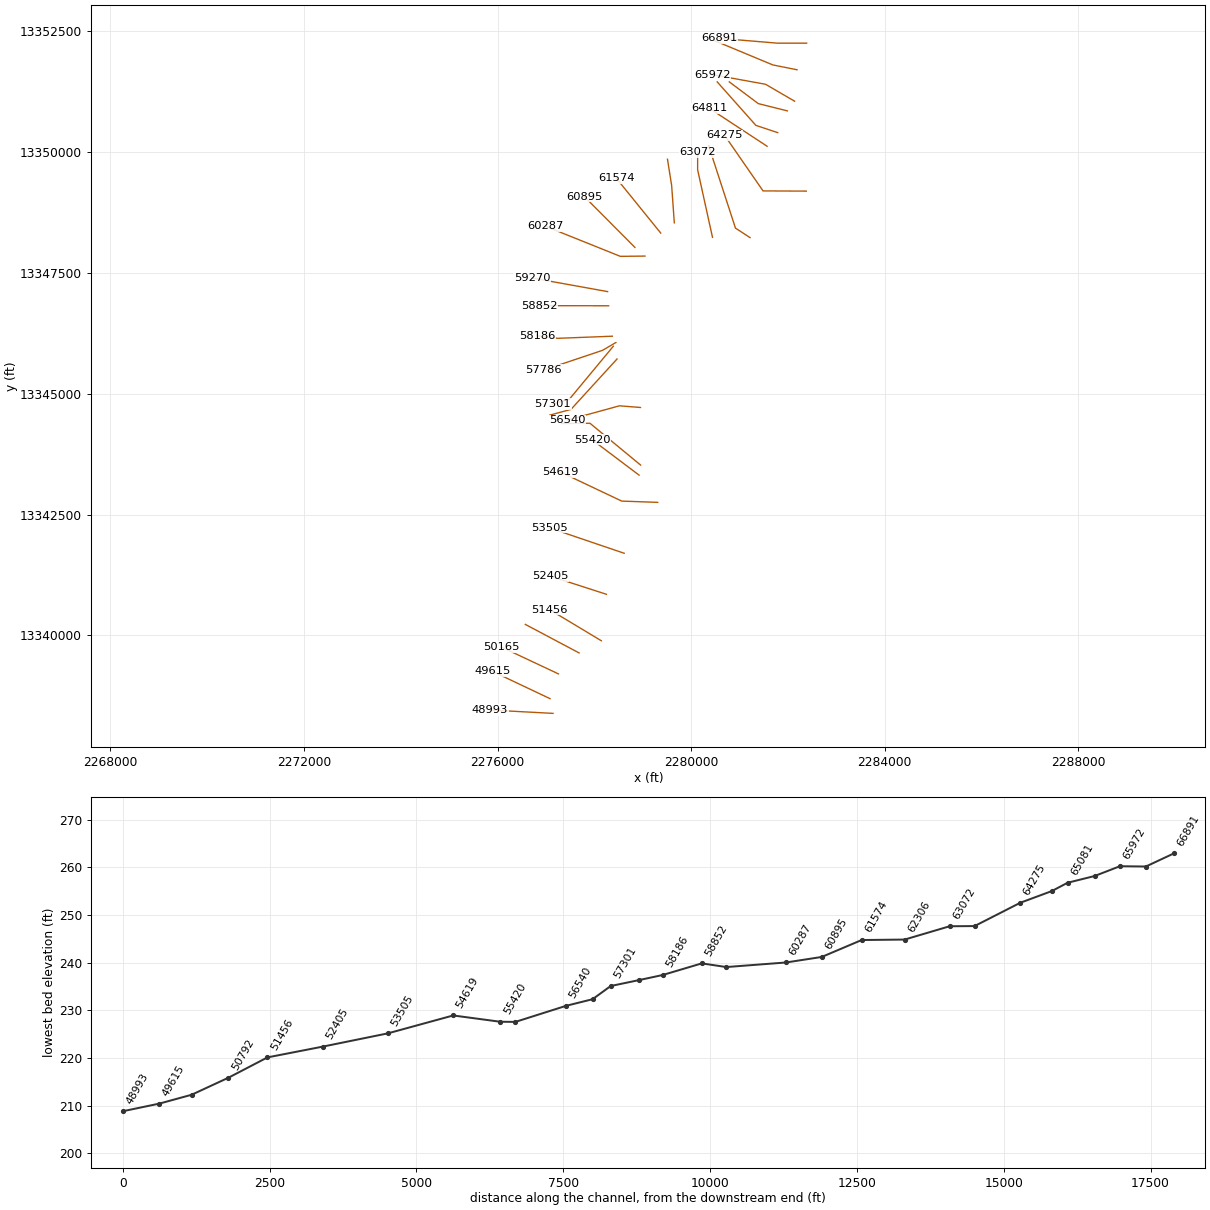
HEC-RAS study VATOSS GULLY.prj: VATOSS GULLY Base Level Engineering

--- VATOSS GULLY.g01 (geometry) --- (continued)

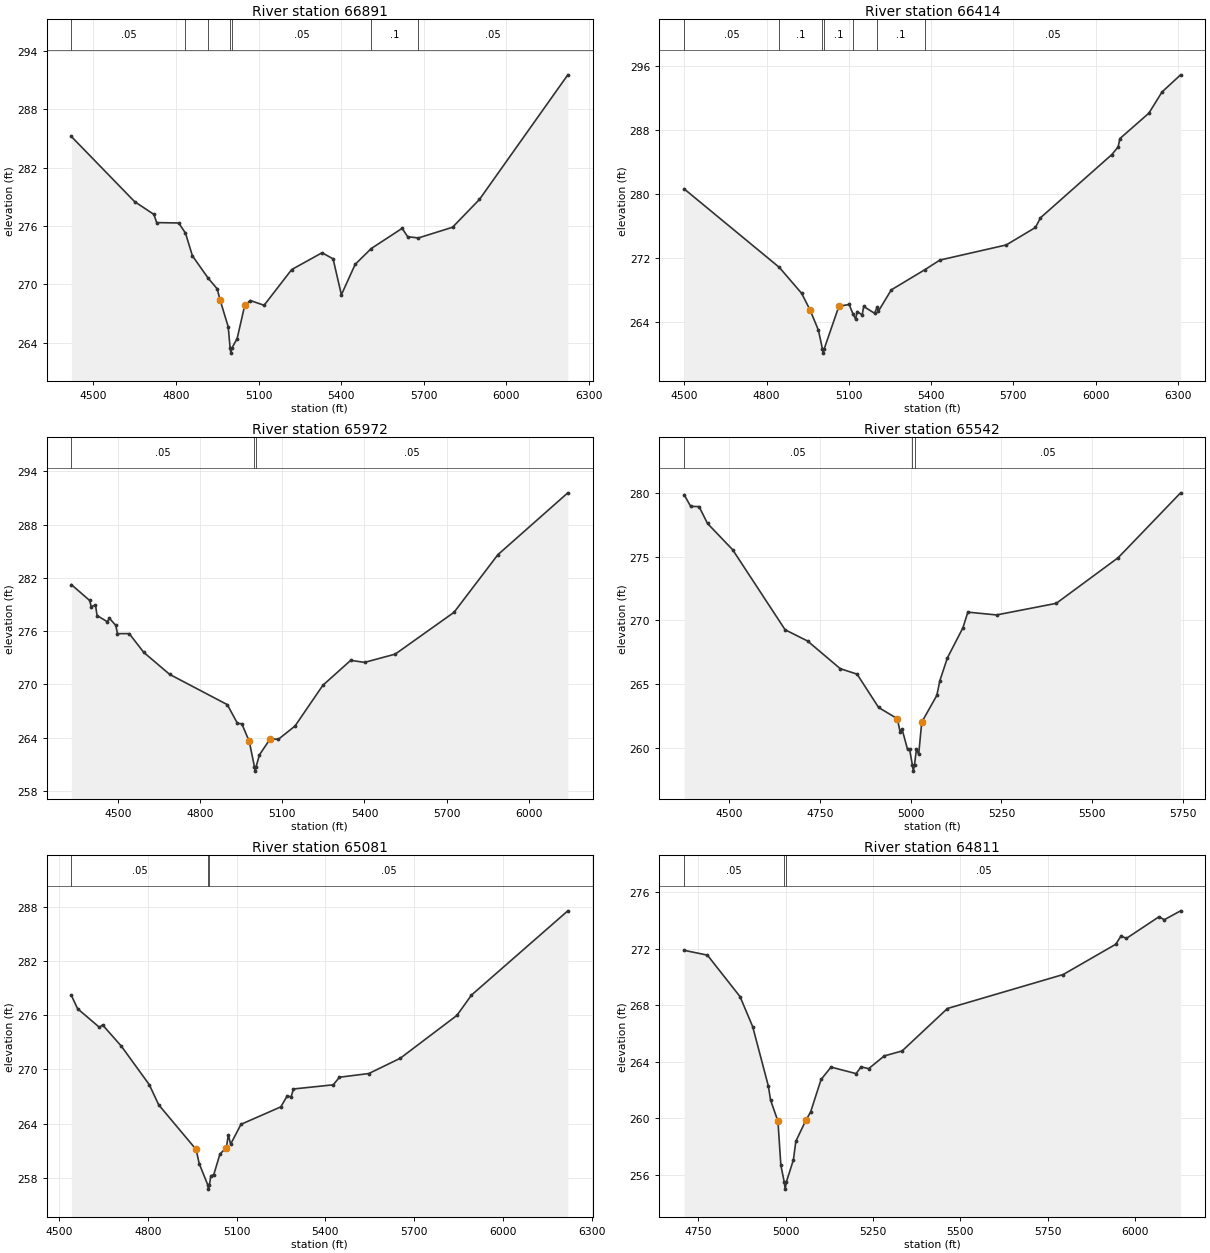
Type RM Length L Ch R = 1 ,66891   ,477,477,477
BEGIN DESCRIPTION:
VATOSS GULLY 85.0
END DESCRIPTION:
XS GIS Cut Line= 3
      2282387.75     13352246.85      2281787.72     13352246.85
      2280587.71     13352346.86
#Sta/Elev= 30
  4419.7  285.19  4649.7  278.49  4719.7  277.18  4729.7  276.34  4809.7   276.3
  4834.4  275.26  4859.7  272.92    4917  270.62  4949.7  269.53  4959.7  268.43
  4989.7  265.63  4996.7  263.42  4999.5  262.92  5002.7  263.42  5022.2  264.42
  5049.8  267.84  5069.9  268.33  5120.1  267.84  5220.4  271.51  5330.8  273.24
  5370.9  272.61    5401  268.92  5451.2  272.05  5509.4  273.67  5621.8  275.75
  5641.9  274.89  5680.7  274.76  5804.9  275.86  5902.8  278.72  6223.9  291.53
#Mann= 7 ,-1 , 0
  4419.7     .05       0  4834.4      .1       0    4917     .05       0
  4996.7    .035       0  5002.7     .05       0  5509.4      .1       0
  5680.7     .05       0
Bank Sta=4959.7,5049.8
XS Rating Curve= 0 ,0
Exp/Cntr=0.3,0.1

Type RM Length L Ch R = 1 ,66414   ,442,442,442
BEGIN DESCRIPTION:
VATOSS GULLY 84.0
END DESCRIPTION:
XS GIS Cut Line= 3
      2282187.69     13351696.86      2281687.72     13351796.85
       2280487.7     13352296.87
#Sta/Elev= 30
  4499.7  280.68  4846.6  270.88    4928  267.64  4958.6  265.57  4989.2  263.04
    5004  260.67  5006.8  260.17    5010  260.67  5063.7  266.01  5101.1  266.25
  5115.1  265.08  5124.9  264.41  5130.4  265.36  5148.8  264.94  5154.2     266
  5193.7  265.15  5203.6  265.91  5207.3  265.37  5254.9  268.07  5378.4  270.61
  5432.1  271.79  5674.2  273.68  5780.4  275.86  5798.8  277.07  6058.8  284.96
  6082.1  285.93    6088  286.95  6194.2  290.14  6241.9  292.78  6309.6  294.92
#Mann= 7 ,-1 , 0
  4499.7     .05       0  4846.6      .1       0    5004     .07       0
    5010      .1       0  5115.1     .05       0  5203.6      .1       0
  5378.4     .05       0
Bank Sta=4958.6,5063.7
XS Rating Curve= 0 ,0
Exp/Cntr=0.3,0.1

Type RM Length L Ch R = 1 ,65972   ,430,430,430
BEGIN DESCRIPTION:
VATOSS GULLY 83.0
END DESCRIPTION:
XS GIS Cut Line= 3
      2282137.75     13351046.84      2281537.72     13351396.85
      2280437.71     13351596.86
#Sta/Elev= 30
  4329.7  281.24  4396.3  279.46  4402.1  278.77  4417.8  278.93  4423.6  277.76
  4460.8  277.06  4468.7  277.45  4491.8  276.65    4498  275.72    4541  275.72
  4593.9  273.61  4688.6  271.13  4899.1  267.72  4936.3   265.6    4952  265.57
  4979.3  263.57  4998.2  260.73  5000.9  260.23  5004.2  260.73  5016.5  262.07
  5056.1  263.88  5085.3  263.81  5146.3  265.31    5248   269.9  5349.6  272.71
  5400.4  272.48  5512.2  273.41  5726.9  278.12    5887  284.61  6142.4  291.58
#Mann= 3 ,-1 , 0
  4329.7     .05       0  4998.2    .035       0  5004.2     .05       0
Bank Sta=4979.3,5056.1
XS Rating Curve= 0 ,0
Exp/Cntr=0.3,0.1

Type RM Length L Ch R = 1 ,65542   ,461,461,461
BEGIN DESCRIPTION:
VATOSS GULLY 82.0
END DESCRIPTION:
XS GIS Cut Line= 3
      2281987.68     13350846.87      2281387.72     13350996.85
      2280787.74     13351446.84
#Sta/Elev= 30
  4375.4  279.84  4393.4  278.93  4416.6  278.91  4439.8  277.59  4509.4  275.52
  4653.7  269.26  4715.5  268.38  4805.7  266.21  4852.1  265.78  4911.4  263.17
  4962.9  262.29  4970.6  261.27  4975.8   261.5  4991.2  259.88  4996.9  259.88
  5004.4  258.68  5007.1  258.18  5010.4  258.68  5015.7  259.91  5021.9   259.5
  5030.3  262.01  5071.9  264.12  5080.3  265.27  5101.1  267.06  5143.8  269.41
  5157.4  270.64  5236.5  270.42  5401.1  271.33  5571.9  274.91  5743.8  279.99
#Mann= 3 ,-1 , 0
  4375.4     .05       0  5004.4    .035       0  5010.4     .05       0
Bank Sta=4962.9,5030.3
XS Rating Curve= 0 ,0
Exp/Cntr=0.3,0.1

Type RM Length L Ch R = 1 ,65081   ,270,270,270
BEGIN DESCRIPTION:
VATOSS GULLY 81.0
END DESCRIPTION:
XS GIS Cut Line= 3
      2281787.76     13350396.84      2281337.72     13350546.85
      2280537.75     13351446.82
#Sta/Elev= 30
  4541.4   278.2  4562.5  276.72  4636.3  274.66  4646.9  274.93  4710.1  272.59
    4805  268.31  4836.6  266.09  4963.1  261.15  4973.6  259.59  5002.2  257.26
    5005  256.76  5008.2  257.26  5013.1  258.23  5022.9  258.37  5043.8  260.64
  5065.5  261.36  5072.2  262.77  5079.8  261.73  5114.9  263.93  5249.5  265.86
  5270.4  267.03  5284.6  266.99  5292.2  267.84  5426.8   268.3  5447.7  269.14
  5547.2  269.55  5653.4  271.24  5844.9  275.98  5894.2  278.23  6219.9  287.55
#Mann= 3 ,-1 , 0
  4541.4     .05       0  5002.2    .035       0  5008.2     .05       0
Bank Sta=4963.1,5065.5
XS Rating Curve= 0 ,0
Exp/Cntr=0.3,0.1

Type RM Length L Ch R = 1 ,64811   ,536,536,536
BEGIN DESCRIPTION:
VATOSS GULLY 80.0
END DESCRIPTION:
XS GIS Cut Line= 2
      2281569.18     13350115.76      2280381.36     13350896.08
#Sta/Elev= 30
  4709.7  271.88  4776.3  271.54  4869.7  268.61  4905.9  266.49  4950.7   262.3
  4957.1   261.3  4978.2  259.81  4986.6  256.69  4996.3  255.51    4999  255.01
  5002.3  255.51  5022.5  257.08  5029.5  258.39  5058.4  259.89  5071.6  260.45
  5101.8  262.76  5130.2  263.63    5202  263.17  5216.3  263.65  5237.9  263.52
  5282.6  264.42  5333.6  264.77  5463.4  267.77  5794.8  270.17  5945.4  272.31
  5960.5   272.9  5975.6  272.72    6069  274.25  6084.1  274.04  6130.9  274.67
#Mann= 3 ,-1 , 0
  4709.7     .05       0  4996.3     .03       0  5002.3     .05       0
Bank Sta=4978.2,5058.4
XS Rating Curve= 0 ,0
Exp/Cntr=0.3,0.1

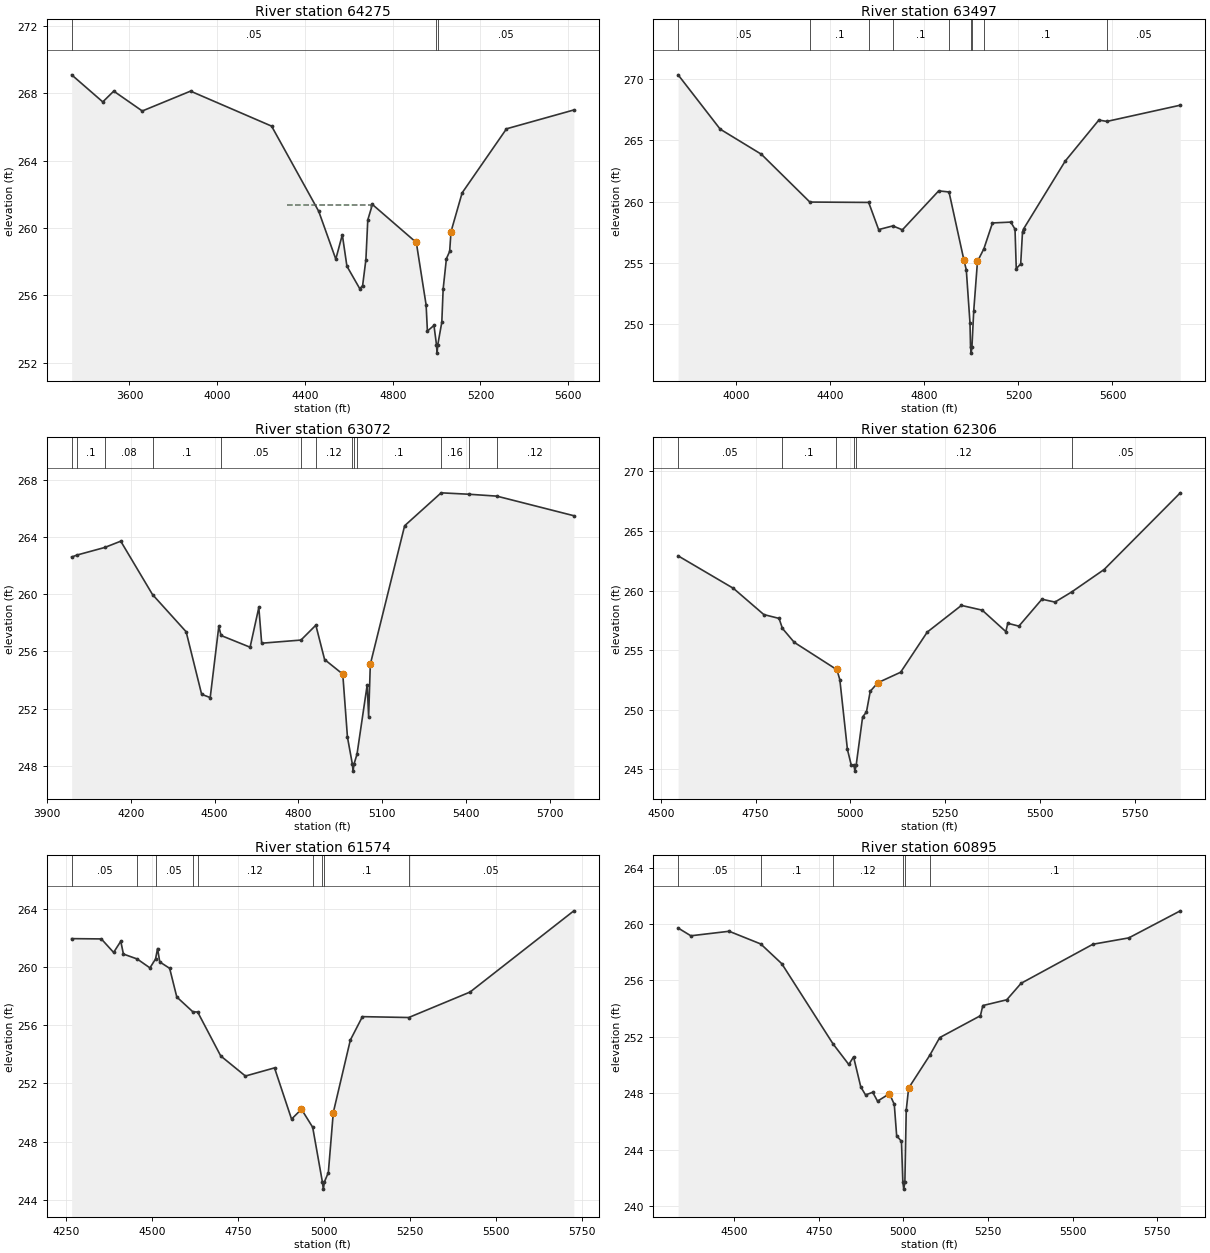
Type RM Length L Ch R = 1 ,64275   ,778,778,778
BEGIN DESCRIPTION:
VATOSS GULLY 79.0
END DESCRIPTION:
XS GIS Cut Line= 3
      2282379.66     13349187.74      2281485.55     13349192.08
       2280692.2     13350339.38
#Sta/Elev= 30
  3336.5  269.11  3478.4   267.5  3528.4  268.14  3658.4  266.96  3878.4  268.14
  4247.8  266.06  4462.8  260.99  4540.5  258.15  4570.2   259.6  4591.2  257.73
  4649.8  256.39  4662.8  256.58  4677.7  258.12  4686.3  260.48  4707.4   261.4
  4907.5  259.14  4952.1  255.43  4958.1  253.87  4987.9  254.21  4999.4  253.06
  5002.1  252.56  5005.4  253.06  5023.7   254.4  5029.8  256.37  5044.7  258.18
  5059.5  258.61  5065.6  259.78  5116.3  262.09  5318.5   265.9  5625.5  267.02
#Mann= 3 ,-1 , 0
  3336.5     .05       0  4999.4     .03       0  5005.4     .05       0
#XS Ineff= 1 ,-1
 4319.53 4701.56  261.36
Permanent Ineff=
       F
Bank Sta=4907.5,5065.6
XS Rating Curve= 0 ,0
Exp/Cntr=0.3,0.1

Type RM Length L Ch R = 1 ,63497   ,425,425,425
BEGIN DESCRIPTION:
Mapping XS 6e612731
END DESCRIPTION:
XS GIS Cut Line= 3
      2281216.37     13348226.44      2280915.47     13348423.18
      2280365.89     13350112.41
#Sta/Elev= 30
  3752.7  270.31  3931.7  265.89  4106.7  263.85    4313  259.96  4563.2  259.93
  4605.5  257.72    4666  258.02  4706.6   257.7    4861  260.87  4904.9  260.78
  4967.9  255.27  4978.4  254.44    4994  250.15  4996.4  248.17  4999.2  247.67
  5002.4  248.17  5009.9  251.08  5025.9  255.13  5053.2  256.16  5089.8  258.26
  5167.7  258.33  5185.6  257.75  5190.9  254.55  5209.7  254.92  5217.5  257.55
  5222.8   257.8    5399  263.29  5542.1  266.63  5576.4  266.52  5888.6  267.84
#Mann= 9 ,-1 , 0
  3752.7     .05       0    4313      .1       0  4563.2     .05       0
    4666      .1       0  4904.9     .12       0  4996.4     .07       0
  5002.4     .12       0  5053.2      .1       0  5576.4     .05       0
Bank Sta=4967.9,5025.9
XS Rating Curve= 0 ,0
Exp/Cntr=0.3,0.1

Type RM Length L Ch R = 1 ,63072   ,766,766,766
BEGIN DESCRIPTION:
Mapping XS ab5e4bff
END DESCRIPTION:
XS GIS Cut Line= 3
      2280440.94     13348232.19      2280134.22     13349626.89
      2280134.22     13349997.27
#Sta/Elev= 30
    3988  262.59  4006.8  262.73  4106.3  263.26  4163.8   263.7  4277.6  259.97
    4398  257.37  4453.5     253  4484.2  252.77    4515  257.75    4523  257.11
    4627  256.29  4658.3  259.07  4668.5  256.57  4809.2  256.79  4862.5  257.83
  4893.8  255.43  4958.9  254.41  4975.7     250  4993.2  248.13  4995.9  247.63
  4999.2  248.13  5009.9  248.81  5046.4  253.66  5051.5  251.44  5057.6   255.1
  5180.5  264.78  5311.2  267.08  5411.6  266.98  5510.4  266.85  5786.4  265.48
#Mann= 13 ,-1 , 0
    3988     .05       0  4006.8      .1       0  4106.3     .08       0
  4277.6      .1       0    4523     .05       0  4809.2      .1       0
  4862.5     .12       0  4993.2     .07       0  4999.2     .12       0
  5009.9      .1       0  5311.2     .16       0  5411.6      .1       0
  5510.4     .12       0
Bank Sta=4958.9,5057.6
XS Rating Curve= 0 ,0
Exp/Cntr=0.3,0.1

Type RM Length L Ch R = 1 ,62306   ,732,732,732
BEGIN DESCRIPTION:
Mapping XS c949294a
END DESCRIPTION:
XS GIS Cut Line= 3
      2279652.13     13348531.24      2279597.53     13349300.58
      2279510.72     13349847.46
#Sta/Elev= 30
  4545.8  262.91  4691.8  260.18    4772  257.98  4812.1  257.66    4821  256.82
  4852.2  255.65    4962  253.41  4964.4  253.39  4972.5  252.51  4992.5  246.66
  5002.6  245.35  5009.6  245.34  5012.3  244.84  5015.6  245.34  5032.6  249.39
  5042.7   249.8  5052.7  251.54  5072.7  252.26  5132.9  253.14  5203.1  256.51
  5293.3  258.75  5348.2  258.35  5410.5  256.55  5415.6  257.25  5444.9  257.01
  5505.7  259.27  5540.1  259.03  5583.8  259.87  5669.7  261.76  5870.8   268.2
#Mann= 6 ,-1 , 0
  4545.8     .05       0    4821      .1       0    4962     .12       0
  5009.6     .07       0  5015.6     .12       0  5583.8     .05       0
Bank Sta=4964.4,5072.7
XS Rating Curve= 0 ,0
Exp/Cntr=0.3,0.1

Type RM Length L Ch R = 1 ,61574   ,679,679,679
BEGIN DESCRIPTION:
Mapping XS 629f08e1
END DESCRIPTION:
XS GIS Cut Line= 2
      2279371.82     13348319.69      2278452.19     13349456.23
#Sta/Elev= 30
  4265.5  261.95  4351.9  261.93  4387.7     261  4408.5  261.77  4416.2  260.89
  4456.4  260.55  4493.4  259.94  4509.7  260.55  4515.6  261.27    4522  260.35
  4550.8  259.91  4571.6  257.94  4618.5  256.92  4632.3  256.91  4699.5  253.89
  4771.4  252.51  4856.1  253.07  4905.7  249.55  4934.5  250.23  4967.2  248.99
  4995.4  245.24  4998.2  244.74  5001.4  245.24  5012.8  245.88  5027.2     250
  5076.8  254.98    5112  256.59  5246.8  256.53  5425.3  258.28  5727.5  263.86
#Mann= 9 ,-1 , 0
  4265.5     .05       0  4456.4      .1       0  4509.7     .05       0
  4618.5      .1       0  4632.3     .12       0  4967.2      .1       0
  4995.4     .07       0  5001.4      .1       0  5246.8     .05       0
Bank Sta=4934.5,5027.2
XS Rating Curve= 0 ,0
Exp/Cntr=0.3,0.1

Type RM Length L Ch R = 1 ,60895   ,608,608,608
BEGIN DESCRIPTION:
Mapping XS 4af8c31c
END DESCRIPTION:
XS GIS Cut Line= 2
      2278837.93     13348023.87      2277791.62     13349075.97
#Sta/Elev= 30
  4334.3  259.71  4371.9  259.16    4485  259.48  4578.4  258.58  4640.6  257.18
  4792.1  251.49  4838.6  250.03  4852.7  250.57    4874  248.44  4888.1  247.87
  4909.3  248.06  4923.5  247.43  4958.8  247.96    4973   247.2    4980  244.98
  4994.2  244.58  4998.3  241.69    5001  241.19  5004.3  241.69  5008.3  246.78
  5015.4  248.36  5077.8  250.68  5107.3  251.94  5227.5  253.49  5234.6  254.21
  5305.3  254.62  5347.7  255.79  5559.9  258.56  5665.9  259.01  5818.1  260.93
#Mann= 6 ,-1 , 0
  4334.3     .05       0  4578.4      .1       0  4792.1     .12       0
  4998.3     .07       0  5004.3     .12       0  5077.8      .1       0
Bank Sta=4958.8,5015.4
XS Rating Curve= 0 ,0
Exp/Cntr=0.3,0.1

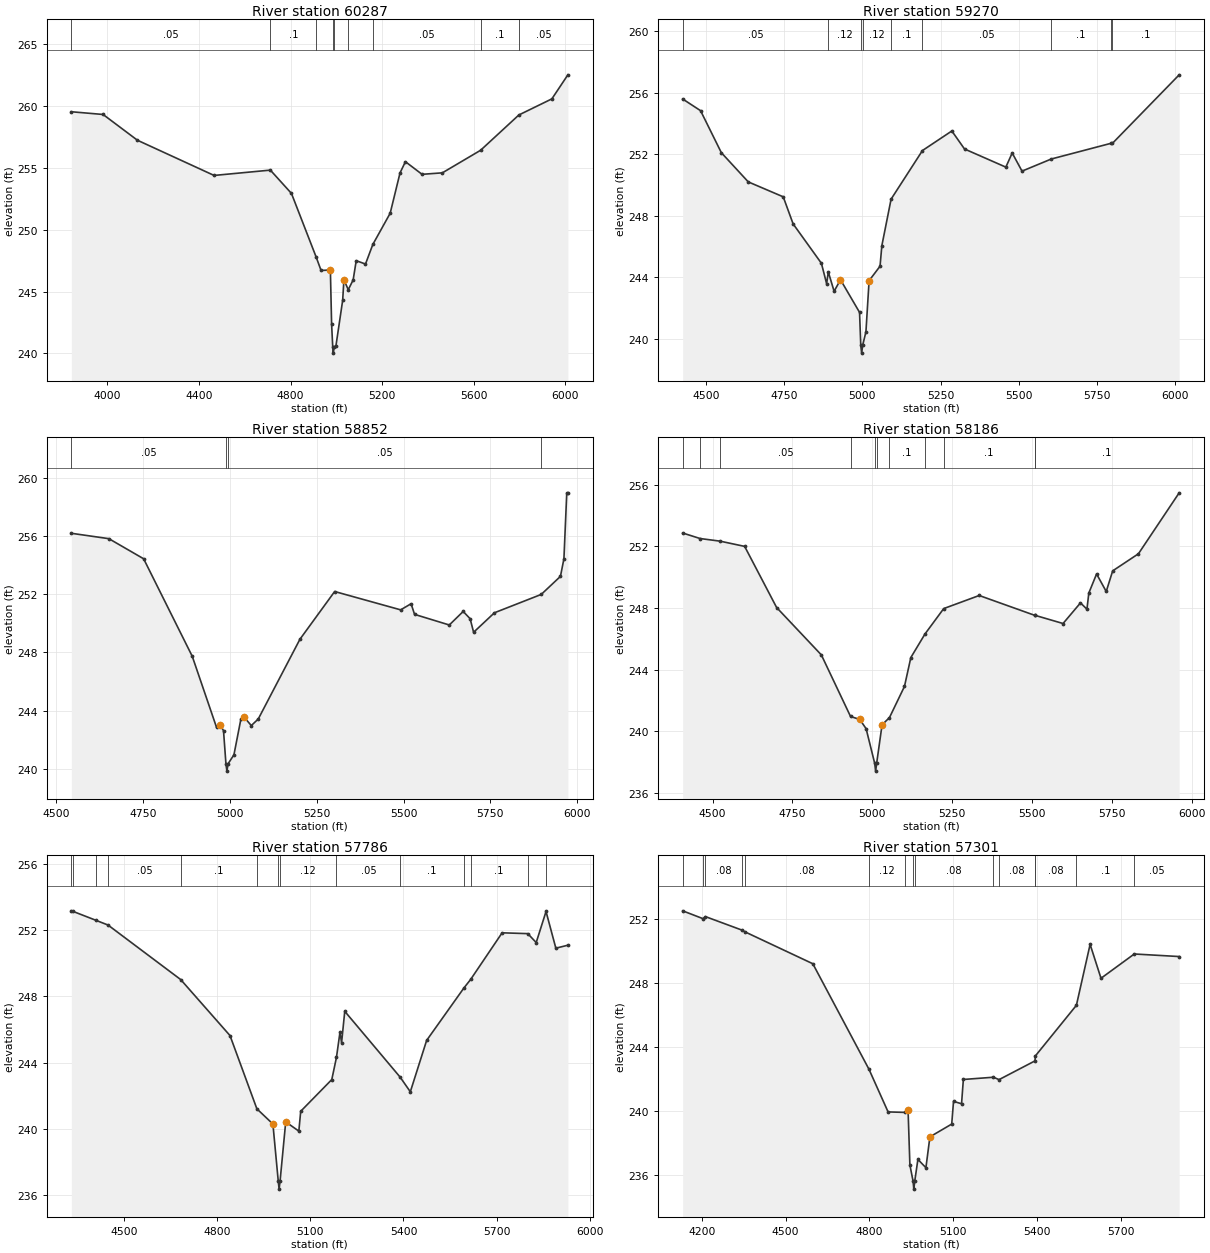
Type RM Length L Ch R = 1 ,60287   ,1017,1017,1017
BEGIN DESCRIPTION:
Mapping XS ee99c064
END DESCRIPTION:
XS GIS Cut Line= 3
      2279046.27     13347844.48        2278537.     13347838.69
      2276997.68     13348457.89
#Sta/Elev= 30
  3842.3  259.51  3980.9  259.29  4130.9  257.21  4465.6  254.37  4711.4   254.8
  4803.5  252.92  4911.7  247.77  4932.9   246.7  4973.5  246.74  4978.9  242.36
  4983.8  240.53  4986.5  240.03  4989.8  240.53  4997.6  240.59  5027.2  244.29
  5032.6  245.94  5051.7  245.15    5073  245.94  5086.4  247.49  5126.9  247.22
  5158.9   248.8  5234.7  251.32  5277.8  254.58  5301.3  255.48  5373.9  254.46
  5462.6  254.58  5629.5   256.4  5796.7  259.25  5940.9  260.55  6010.8  262.49
#Mann= 9 ,-1 , 0
  3842.3     .05       0  4711.4      .1       0  4911.7     .12       0
  4983.8     .07       0  4989.8     .12       0  5051.7      .1       0
  5158.9     .05       0  5629.5      .1       0  5796.7     .05       0
Bank Sta=4973.5,5032.6
XS Rating Curve= 0 ,0
Exp/Cntr=0.3,0.1

Type RM Length L Ch R = 1 ,59270   ,418,418,418
BEGIN DESCRIPTION:
Mapping XS 8602f0cc
END DESCRIPTION:
XS GIS Cut Line= 2
      2278274.05     13347109.82      2276712.61     13347391.85
#Sta/Elev= 30
  4425.6  255.59  4482.8  254.83  4549.2   252.1  4635.3   250.2    4747  249.23
  4778.6  247.47    4869  244.91  4885.7  243.58    4891  244.35  4909.6  243.09
    4930  243.84  4990.9  241.72  4994.8  239.57  4997.6  239.07  5000.8  239.57
  5011.3  240.46  5021.4  243.78  5056.4  244.72  5062.1  246.05  5091.7  249.08
    5192  252.24  5285.8  253.51  5326.3  252.34  5458.4  251.16  5478.7  252.08
  5510.1   250.9  5603.9  251.69  5794.8  252.71  5799.2  252.71  6012.3  257.16
#Mann= 9 ,-1 , 0
  4425.6     .05       0    4891     .12       0  4994.8     .07       0
  5000.8     .12       0  5091.7      .1       0    5192     .05       0
  5603.9      .1       0  5794.8     .05       0  5799.2      .1       0
Bank Sta=4930,5021.4
XS Rating Curve= 0 ,0
Exp/Cntr=0.3,0.1

Type RM Length L Ch R = 1 ,58852   ,666,666,666
BEGIN DESCRIPTION:
Mapping XS 1f2a0937
END DESCRIPTION:
XS GIS Cut Line= 2
      2278295.77     13346816.84      2276866.37     13346819.39
#Sta/Elev= 30
  4543.6  256.18  4651.6  255.81  4751.6  254.43  4891.6  247.73  4961.6  242.84
  4971.6  243.03  4981.6  242.62  4988.6  240.34  4991.4  239.84  4994.6  240.34
  5011.6  240.96  5031.6  243.41  5041.6  243.53  5061.6  242.97  5081.6  243.42
  5201.6   248.9  5301.6  252.18  5491.6  250.92  5521.6  251.34  5531.6  250.61
  5631.6  249.88  5671.6  250.81  5691.6  250.31  5701.6  249.38  5761.6  250.72
  5896.3  251.98  5951.6  253.22  5961.6  254.43  5969.8  258.96    5973  258.96
#Mann= 4 ,-1 , 0
  4543.6     .05       0  4988.6    .035       0  4994.6     .05       0
  5896.3      .1       0
Bank Sta=4971.6,5041.6
XS Rating Curve= 0 ,0
Exp/Cntr=0.3,0.1

Type RM Length L Ch R = 1 ,58186   ,400,400,400
BEGIN DESCRIPTION:
Mapping XS 46af28cf
END DESCRIPTION:
XS GIS Cut Line= 3
       2278371.7      13346187.5      2277243.28      13346144.1
      2276821.11     13346196.79
#Sta/Elev= 30
  4406.3  252.87  4461.1  252.51  4523.6  252.34  4600.4     252  4700.5  248.03
  4840.6  244.95    4932  240.95  4960.7  240.76  4980.7  240.16  5007.7   237.9
  5010.5   237.4  5013.7   237.9  5030.7  240.41  5053.9  240.88  5100.8   242.9
  5120.8  244.78  5165.1  246.31  5223.7  247.96  5334.9  248.81  5508.8  247.52
  5509.9  247.52  5597.4  246.99    5652  248.33  5672.2  247.92  5678.1  248.97
  5702.4  250.21  5732.6  249.07  5752.8  250.41  5833.4  251.52    5961  255.48
#Mann= 11 ,-1 , 0
  4406.3     .05       0  4461.1      .1       0  4523.6     .05       0
    4932     .12       0  5007.7     .07       0  5013.7     .12       0
  5053.9      .1       0  5165.1     .05       0  5223.7      .1       0
  5508.8     .05       0  5509.9      .1       0
Bank Sta=4960.7,5030.7
XS Rating Curve= 0 ,0
Exp/Cntr=0.3,0.1

Type RM Length L Ch R = 1 ,57786   ,485,485,485
BEGIN DESCRIPTION:
Mapping XS 0ac4fc57
END DESCRIPTION:
XS GIS Cut Line= 3
       2278444.4     13346056.28      2278166.63     13345894.25
      2276957.14     13345489.16
#Sta/Elev= 30
  4331.7  253.18  4337.8  253.14  4410.2  252.61  4449.6  252.32  4683.4  249.02
    4842  245.63  4928.4   241.2    4980  240.28  4997.1  236.84  4999.9  236.34
  5003.1  236.84  5021.2  240.41  5063.4  239.85  5069.4  241.05  5169.4  242.97
  5184.4  244.31  5195.7  245.83  5200.9   245.2  5211.1   247.1  5389.5  243.11
    5422  242.23  5474.5  245.34  5594.7  248.52  5616.1  249.03  5717.3  251.85
  5799.8   251.8  5826.9  251.26  5858.5  253.14  5890.1  250.92  5928.8   251.1
#Mann= 14 ,-1 , 0
  4331.7     .08       0  4337.8      .1       0  4410.2     .08       0
  4449.6     .05       0  4683.4      .1       0  4928.4     .12       0
  4997.1     .07       0  5003.1     .12       0  5184.4     .05       0
  5389.5      .1       0  5594.7     .05       0  5616.1      .1       0
  5799.8     .08       0  5858.5      .1       0
Bank Sta=4980,5021.2
XS Rating Curve= 0 ,0
Exp/Cntr=0.3,0.1

Type RM Length L Ch R = 1 ,57301   ,309,309,309
BEGIN DESCRIPTION:
Mapping XS ff63ebf4
END DESCRIPTION:
XS GIS Cut Line= 3
      2278391.28      13345979.6      2277481.56     13344882.38
      2277142.04     13344785.38
#Sta/Elev= 30
  4131.5   252.5  4204.4  252.01  4212.9  252.14  4344.4  251.29  4356.5  251.17
  4597.7  249.19  4798.8  242.59  4867.3  239.92  4926.4  239.89  4938.9  240.01
  4945.4   236.6  4956.8  235.59  4959.5  235.09  4962.8  235.59  4974.1  236.95
  5002.8  236.43  5017.1  238.36  5095.2  239.16  5101.7  240.58  5130.4  240.43
  5136.9  241.95  5244.6  242.09  5264.7  241.94  5393.2  243.11  5395.2  243.43
  5541.8  246.59  5590.9   250.4  5629.9  248.28  5749.1   249.8  5909.9  249.64
#Mann= 15 ,-1 , 0
  4131.5     .08       0  4204.4     .05       0  4212.9     .08       0
  4344.4      .1       0  4356.5     .08       0  4798.8     .12       0
  4926.4     .08       0  4956.8     .07       0  4962.8     .08       0
  5244.6      .1       0  5264.7     .08       0  5393.2      .1       0
  5395.2     .08       0  5541.8      .1       0  5749.1     .05       0
Bank Sta=4938.9,5017.1
XS Rating Curve= 0 ,0
Exp/Cntr=0.3,0.1

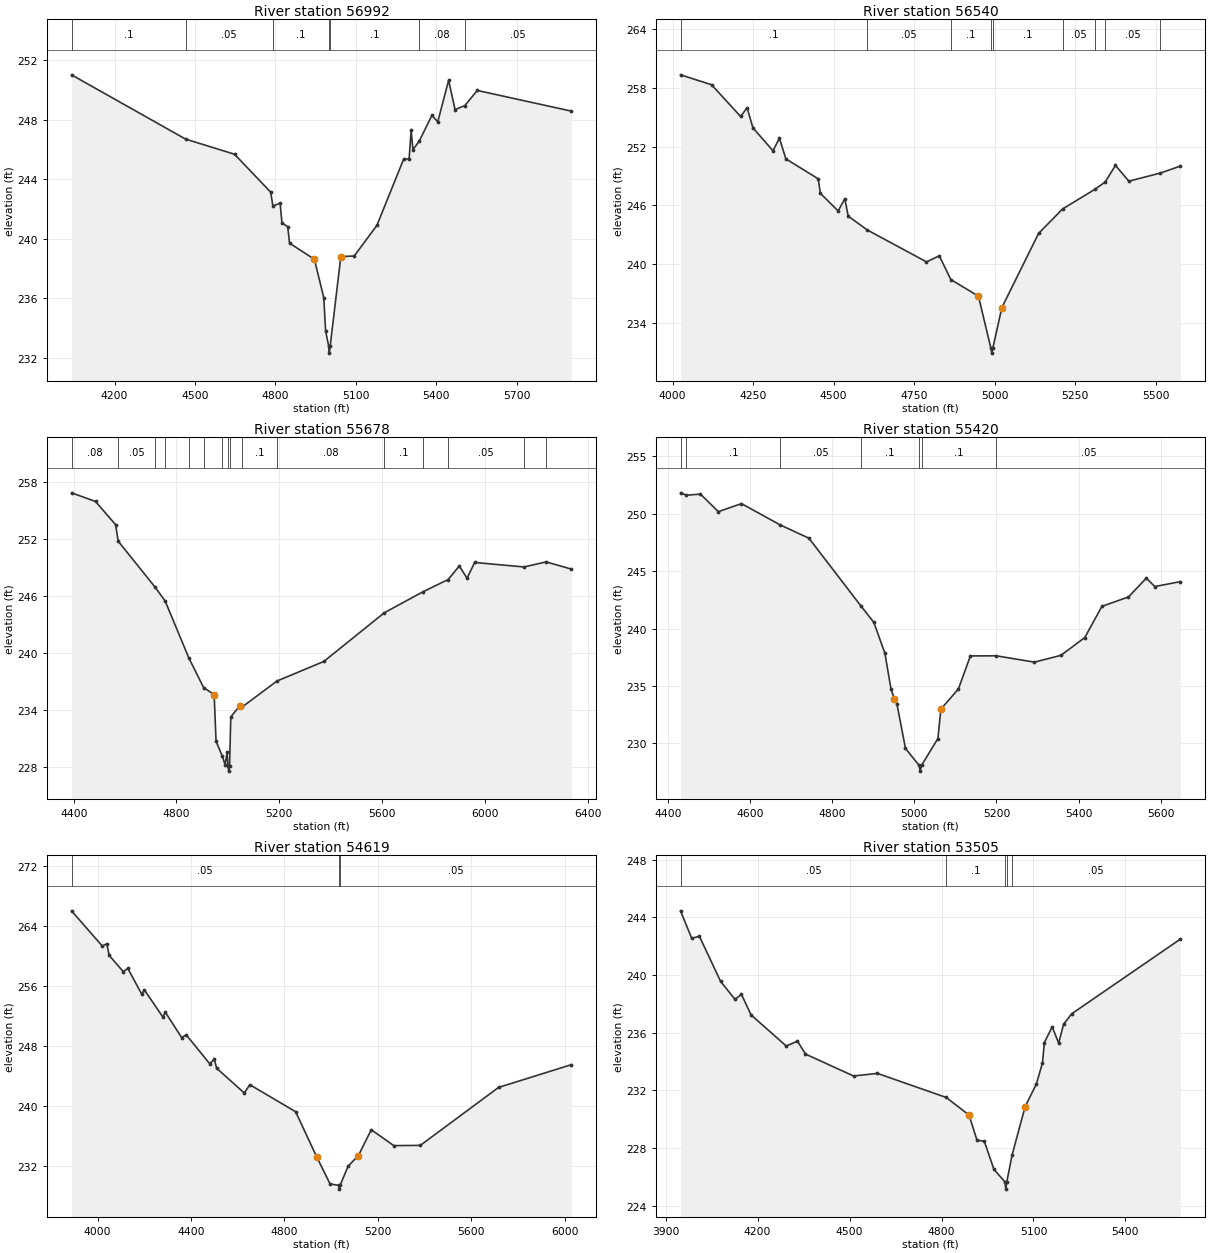
Type RM Length L Ch R = 1 ,56992   ,452,452,452
BEGIN DESCRIPTION:
Mapping XS 7ab08d34
END DESCRIPTION:
XS GIS Cut Line= 3
      2278467.66     13345715.71      2277516.28     13344674.05
      2277078.77     13344555.99
#Sta/Elev= 30
  4039.6  251.03  4464.8  246.71  4647.5  245.69  4782.2  243.14  4790.4  242.21
  4817.4   242.4  4824.2  241.07  4845.8  240.82  4852.5  239.71  4945.1  238.63
  4980.2  236.04    4987  233.79  4998.2  232.82  5000.9  232.32  5004.2  232.82
  5043.7  238.81  5093.7  238.85  5178.2  240.91  5277.5  245.34  5298.4  245.39
  5305.8  247.29  5312.6     246    5336  246.57  5383.5  248.31  5405.1  247.87
  5445.6  250.66  5469.6  248.69    5506  248.96  5552.4  249.98  5903.5  248.59
#Mann= 7 ,-1 , 0
  4039.6      .1       0  4464.8     .05       0  4790.4      .1       0
  4998.2     .07       0  5004.2      .1       0    5336     .08       0
    5506     .05       0
Bank Sta=4945.1,5043.7
XS Rating Curve= 0 ,0
Exp/Cntr=0.3,0.1

Type RM Length L Ch R = 1 ,56540   ,862,862,862
BEGIN DESCRIPTION:
Mapping XS 5c44a05c
END DESCRIPTION:
XS GIS Cut Line= 3
      2278953.66     13344713.69      2278519.64     13344748.41
      2277443.27     13344453.28
#Sta/Elev= 30
  4024.9  259.33  4121.1  258.32  4211.4  255.08  4231.5  255.97  4249.6  253.92
  4311.8  251.58  4331.8  252.86  4351.9  250.75  4452.2  248.72  4458.8  247.24
  4514.1  245.44  4534.9  246.69  4545.2  244.91  4604.5   243.5  4788.3  240.24
  4827.9  240.86  4863.8  238.44  4949.6  236.74  4988.1  231.43  4990.9  230.93
  4994.1  231.43  5022.2  235.58  5136.3  243.15  5210.6  245.64  5311.7  247.66
    5343   248.4  5374.8  250.09  5416.3  248.48  5513.7   249.3  5576.4  250.02
#Mann= 9 ,-1 , 0
  4024.9      .1       0  4604.5     .05       0  4863.8      .1       0
  4988.1     .07       0  4994.1      .1       0  5210.6     .05       0
  5311.7     .08       0    5343     .05       0  5513.7     .08       0
Bank Sta=4949.6,5022.2
XS Rating Curve= 0 ,0
Exp/Cntr=0.3,0.1

Type RM Length L Ch R = 1 ,55678   ,258,258,258
BEGIN DESCRIPTION:
Mapping XS 2707ef90
END DESCRIPTION:
XS GIS Cut Line= 3
      2278955.55     13343523.15      2277908.71      13344387.7
      2277321.42     13344382.51
#Sta/Elev= 30
  4391.6  256.81  4484.9   255.9  4563.1  253.46  4573.1  251.73  4717.5  246.87
  4756.2  245.42  4848.1  239.45  4905.8  236.33  4946.5  235.61  4953.9   230.7
  4978.7   229.1  4989.1  228.22  4996.9  229.53  5000.4  228.06  5003.2  227.56
  5006.4  228.06  5011.3  233.26  5046.4  234.43  5055.4   234.3  5190.9  237.03
  5373.4  239.09  5608.8  244.21    5759  246.41  5857.2   247.7  5900.3  249.12
  5930.3  247.84  5960.3  249.49  6151.8  249.02  6238.5  249.55  6336.6  248.79
#Mann= 16 ,-1 , 0
  4391.6     .08       0  4573.1     .05       0  4717.5     .08       0
  4756.2     .05       0  4848.1     .08       0  4905.8      .1       0
  4978.7     .08       0  5000.4     .07       0  5006.4     .08       0
  5055.4      .1       0  5190.9     .08       0  5608.8      .1       0
    5759     .08       0  5857.2     .05       0  6151.8     .08       0
  6238.5     .05       0
Bank Sta=4946.5,5046.4
XS Rating Curve= 0 ,0
Exp/Cntr=0.3,0.1

Type RM Length L Ch R = 1 ,55420   ,801,801,801
BEGIN DESCRIPTION:
VATOSS GULLY 65.0
END DESCRIPTION:
XS GIS Cut Line= 2
      2278924.34     13343314.78      2277951.58     13344048.26
#Sta/Elev= 30
    4430  251.82  4444.5  251.61  4478.5  251.71  4522.2  250.18  4578.5  250.88
  4672.6  249.03  4742.9  247.87  4869.4  241.98  4901.1  240.54  4928.2  237.84
  4942.8  234.76  4951.1  233.88  4957.4  233.43  4978.2  229.57  5011.4  228.09
  5014.2  227.59  5017.4  228.09  5057.3  230.43  5064.5  232.99  5107.2  234.74
  5136.4  237.62  5199.5  237.63  5292.5  237.08  5357.1  237.67  5415.2  239.22
    5457  241.94  5521.5  242.75  5565.2  244.39    5586  243.66  5648.3  244.09
#Mann= 7 ,-1 , 0
    4430     .05       0  4444.5      .1       0  4672.6     .05       0
  4869.4      .1       0  5011.4     .07       0  5017.4      .1       0
  5199.5     .05       0
Bank Sta=4951.1,5064.5
XS Rating Curve= 0 ,0
Exp/Cntr=0.3,0.1

Type RM Length L Ch R = 1 ,54619   ,1114,1114,1114
BEGIN DESCRIPTION:
VATOSS GULLY 64.0
END DESCRIPTION:
XS GIS Cut Line= 3
      2279308.81     13342751.89      2278566.66     13342777.93
       2277303.6     13343376.91
#Sta/Elev= 30
  3888.2  266.07  4019.4  261.38  4039.4  261.66  4049.4  260.12  4109.4  257.96
  4129.4  258.37  4189.5   254.9  4199.5  255.54  4279.5  251.88  4289.5  252.55
  4359.6  249.15  4379.6   249.5  4479.7  245.66  4499.7  246.22  4509.7  245.05
  4627.8  241.75  4651.8  242.85  4847.7  239.25  4938.7  233.17  4995.2  229.61
  5032.2  229.41  5034.9  228.91  5038.2  229.41  5072.3  231.97  5116.6   233.4
  5171.6  236.84  5268.1  234.72  5381.7  234.75  5716.7  242.49  6028.7  245.53
#Mann= 3 ,-1 , 0
  3888.2     .05       0  5032.2     .03       0  5038.2     .05       0
Bank Sta=4938.7,5116.6
XS Rating Curve= 0 ,0
Exp/Cntr=0.3,0.1

Type RM Length L Ch R = 1 ,53505   ,1100,1100,1100
BEGIN DESCRIPTION:
Mapping XS de15816e
END DESCRIPTION:
XS GIS Cut Line= 2
      2278615.84     13341699.64      2277071.69     13342224.48
#Sta/Elev= 30
  3948.5  244.46    3985  242.55  4009.9   242.7  4079.1  239.57  4126.1  238.32
  4147.2  238.66  4178.9  237.23  4293.5  235.08  4330.1  235.42  4356.2  234.52
  4513.1     233  4590.8  233.18  4815.4  231.51  4889.7  230.29  4915.8  228.54
  4939.3  228.48    4971  226.52  5006.9  225.65  5009.7  225.15  5012.9  225.65
  5030.5  227.54  5072.7  230.87  5109.4  232.44  5129.4  233.91  5135.5  235.32
  5161.1  236.41  5182.2  235.28  5198.2  236.59  5224.3  237.31  5579.4   242.5
#Mann= 5 ,-1 , 0
  3948.5     .05       0  4815.4      .1       0  5006.9     .07       0
  5012.9      .1       0  5030.5     .05       0
Bank Sta=4889.7,5072.7
XS Rating Curve= 0 ,0
Exp/Cntr=0.3,0.1

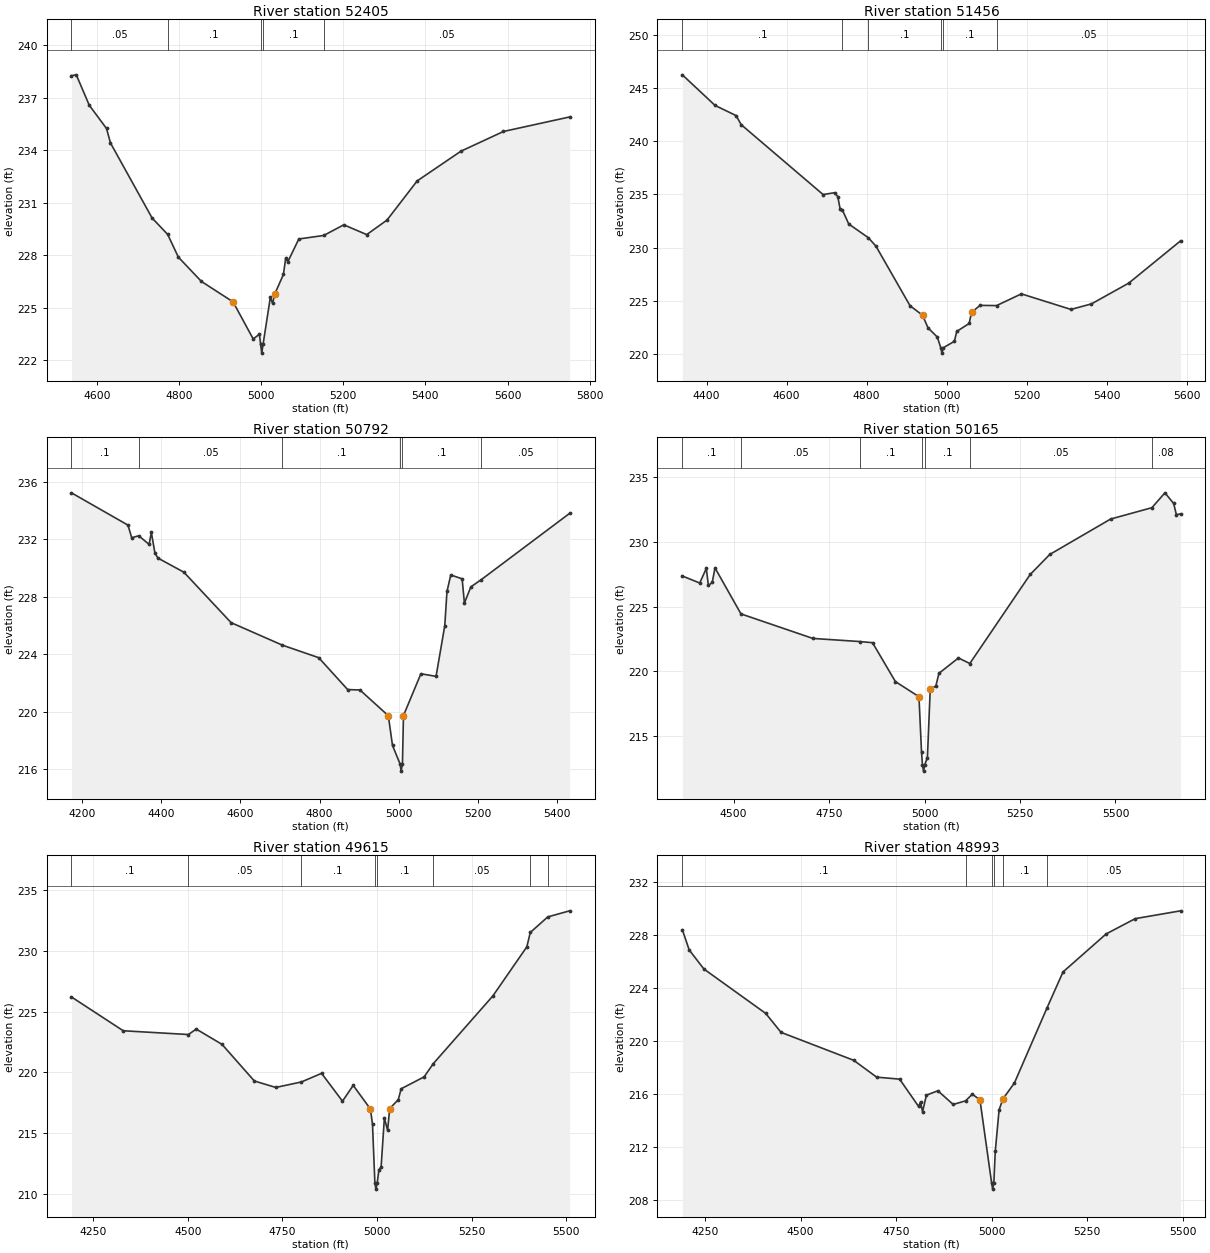
Type RM Length L Ch R = 1 ,52405   ,949,949,949
BEGIN DESCRIPTION:
Mapping XS 863a8ee8
END DESCRIPTION:
XS GIS Cut Line= 2
      2278248.97     13340851.25      2277094.51      13341224.5
#Sta/Elev= 30
  4537.9  238.26  4549.7  238.31  4581.3  236.57  4623.3  235.24    4633  234.41
  4734.3  230.12  4772.3  229.18  4798.3  227.88  4854.5  226.49  4931.6  225.32
  4980.6   223.2  4995.7  223.47  4998.6  222.89  5001.4  222.39  5004.6  222.89
  5022.4  225.59  5027.7  225.24  5033.2  225.78  5054.2  226.89  5059.7  227.82
    5065  227.62  5091.7  228.92  5152.2  229.12  5201.3  229.73  5257.1  229.17
  5306.4     230  5379.9  232.24  5486.4  233.94  5590.2  235.07  5751.2   235.9
#Mann= 5 ,-1 , 0
  4537.9     .05       0  4772.3      .1       0  4998.6     .07       0
  5004.6      .1       0  5152.2     .05       0
Bank Sta=4931.6,5033.2
XS Rating Curve= 0 ,0
Exp/Cntr=0.3,0.1

Type RM Length L Ch R = 1 ,51456   ,664,664,664
BEGIN DESCRIPTION:
VATOSS GULLY 63.0
END DESCRIPTION:
XS GIS Cut Line= 2
      2278143.87     13339890.42      2277076.97      13340532.3
#Sta/Elev= 30
  4339.5  246.22  4421.2  243.35  4473.6   242.4  4486.7  241.54  4691.2  234.99
  4720.1  235.16  4728.1  234.78  4733.9  233.62  4739.5  233.54  4755.3  232.23
  4804.3  230.94  4823.3  230.15  4908.7  224.55  4939.8  223.67  4953.5  222.48
  4976.7  221.62  4985.5  220.61  4988.3  220.11  4991.5  220.61  5019.5  221.22
  5025.3  222.15  5056.4  222.89  5062.2  223.93  5083.6  224.59  5124.9  224.57
  5186.9  225.67  5310.8  224.21    5362  224.73  5455.3  226.68  5584.6  230.64
#Mann= 6 ,-1 , 0
  4339.5      .1       0  4739.5     .05       0  4804.3      .1       0
  4985.5     .07       0  4991.5      .1       0  5124.9     .05       0
Bank Sta=4939.8,5062.2
XS Rating Curve= 0 ,0
Exp/Cntr=0.3,0.1

Type RM Length L Ch R = 1 ,50792   ,627,627,627
BEGIN DESCRIPTION:
VATOSS GULLY 62.0
END DESCRIPTION:
XS GIS Cut Line= 2
      2277683.81     13339638.68      2276572.68     13340228.97
#Sta/Elev= 30
  4173.4  235.23  4316.2  232.98  4325.6   232.1  4343.2  232.24  4369.6  231.64
  4375.2  232.47  4384.1  231.06  4391.6  230.69  4457.5   229.7  4576.6  226.19
  4706.4  224.62  4797.9  223.75    4871  221.53  4902.1   221.5  4973.7  219.71
  4984.3  217.64  5003.4  216.35  5006.1  215.85  5009.4  216.35    5012  219.72
    5056  222.63  5094.3  222.45  5116.3  225.97  5121.9  228.36  5131.5  229.51
  5160.2  229.24  5165.9  227.55  5182.2  228.68  5208.3  229.18  5431.6   233.8
#Mann= 6 ,-1 , 0
  4173.4      .1       0  4343.2     .05       0  4706.4      .1       0
  5003.4     .07       0  5009.4      .1       0  5208.3     .05       0
Bank Sta=4973.7,5012
XS Rating Curve= 0 ,0
Exp/Cntr=0.3,0.1

Type RM Length L Ch R = 1 ,50165   ,550,550,550
BEGIN DESCRIPTION:
VATOSS GULLY 61.0
END DESCRIPTION:
XS GIS Cut Line= 2
      2277258.43     13339204.66      2276077.92      13339760.2
#Sta/Elev= 30
  4365.7  227.37  4411.2  226.83  4428.4  227.96  4433.9  226.64  4443.9  226.87
  4451.2     228  4519.2  224.44  4707.5  222.54  4830.1   222.3  4863.8  222.21
  4923.7   219.2  4985.4  218.03  4992.1  213.73  4994.6  212.77  4997.3  212.27
  5000.6  212.77  5007.5  213.31  5014.9   218.6  5029.6  218.86  5037.7  219.84
  5088.8  221.03  5118.6   220.6  5276.7  227.49    5328  229.04  5487.3  231.78
  5595.5  232.66  5629.6  233.81  5652.4  232.99  5659.6  232.12  5670.4  232.18
#Mann= 7 ,-1 , 0
  4365.7      .1       0  4519.2     .05       0  4830.1      .1       0
  4994.6     .07       0  5000.6      .1       0  5118.6     .05       0
  5595.5     .08       0
Bank Sta=4985.4,5014.9
XS Rating Curve= 0 ,0
Exp/Cntr=0.3,0.1

Type RM Length L Ch R = 1 ,49615   ,622,622,622
BEGIN DESCRIPTION:
VATOSS GULLY 60.0
END DESCRIPTION:
XS GIS Cut Line= 2
      2277084.84      13338692.5       2275895.6     13339256.74
#Sta/Elev= 30
  4192.6  226.21  4329.4  223.43  4501.7  223.12  4522.3  223.57  4590.5  222.31
  4675.9   219.3  4732.5  218.77  4800.2  219.22  4853.5  219.93  4908.8  217.64
  4937.1  218.94  4982.5     217  4988.1  215.75  4994.4  210.91  4997.2  210.41
  5000.4  210.91  5005.3  212.02  5010.8  212.22  5019.5  216.27    5028  215.24
  5033.5  217.03  5056.3  217.77  5063.8  218.66  5124.5  219.64  5148.8  220.73
  5306.3   226.3  5395.9  230.33    5405  231.51  5451.2  232.79  5508.9  233.29
#Mann= 8 ,-1 , 0
  4192.6      .1       0  4501.7     .05       0  4800.2      .1       0
  4994.4     .07       0  5000.4      .1       0  5148.8     .05       0
    5405     .08       0  5451.2     .05       0
Bank Sta=4982.5,5033.5
XS Rating Curve= 0 ,0
Exp/Cntr=0.3,0.1

Type RM Length L Ch R = 1 ,48993   ,926,926,926
BEGIN DESCRIPTION:
VATOSS GULLY 59.0
END DESCRIPTION:
XS GIS Cut Line= 2
      2277145.64     13338388.67      2275843.49     13338458.12
#Sta/Elev= 30
  4190.6  228.38  4208.5  226.86    4247  225.42  4408.8  222.07  4448.9  220.64
  4639.2  218.53  4699.2  217.26  4759.3  217.11    4809  215.05    4814  215.39
  4819.4  214.65  4829.4   215.9  4859.5  216.23  4899.5   215.2  4931.8  215.47
  4949.6  215.97  4969.6  215.55    5000  209.31  5002.8  208.81    5006  209.31
  5009.7  211.66  5019.7  214.79  5029.7  215.61  5030.3  215.64  5059.8  216.82
  5144.9  222.47  5187.1   225.2  5300.1  228.07  5376.1  229.22  5494.6  229.81
#Mann= 6 ,-1 , 0
  4190.6      .1       0  4931.8     .12       0    5000     .07       0
    5006     .12       0  5030.3      .1       0  5144.9     .05       0
Bank Sta=4969.6,5029.7
XS Rating Curve= 0 ,0
Exp/Cntr=0.3,0.1