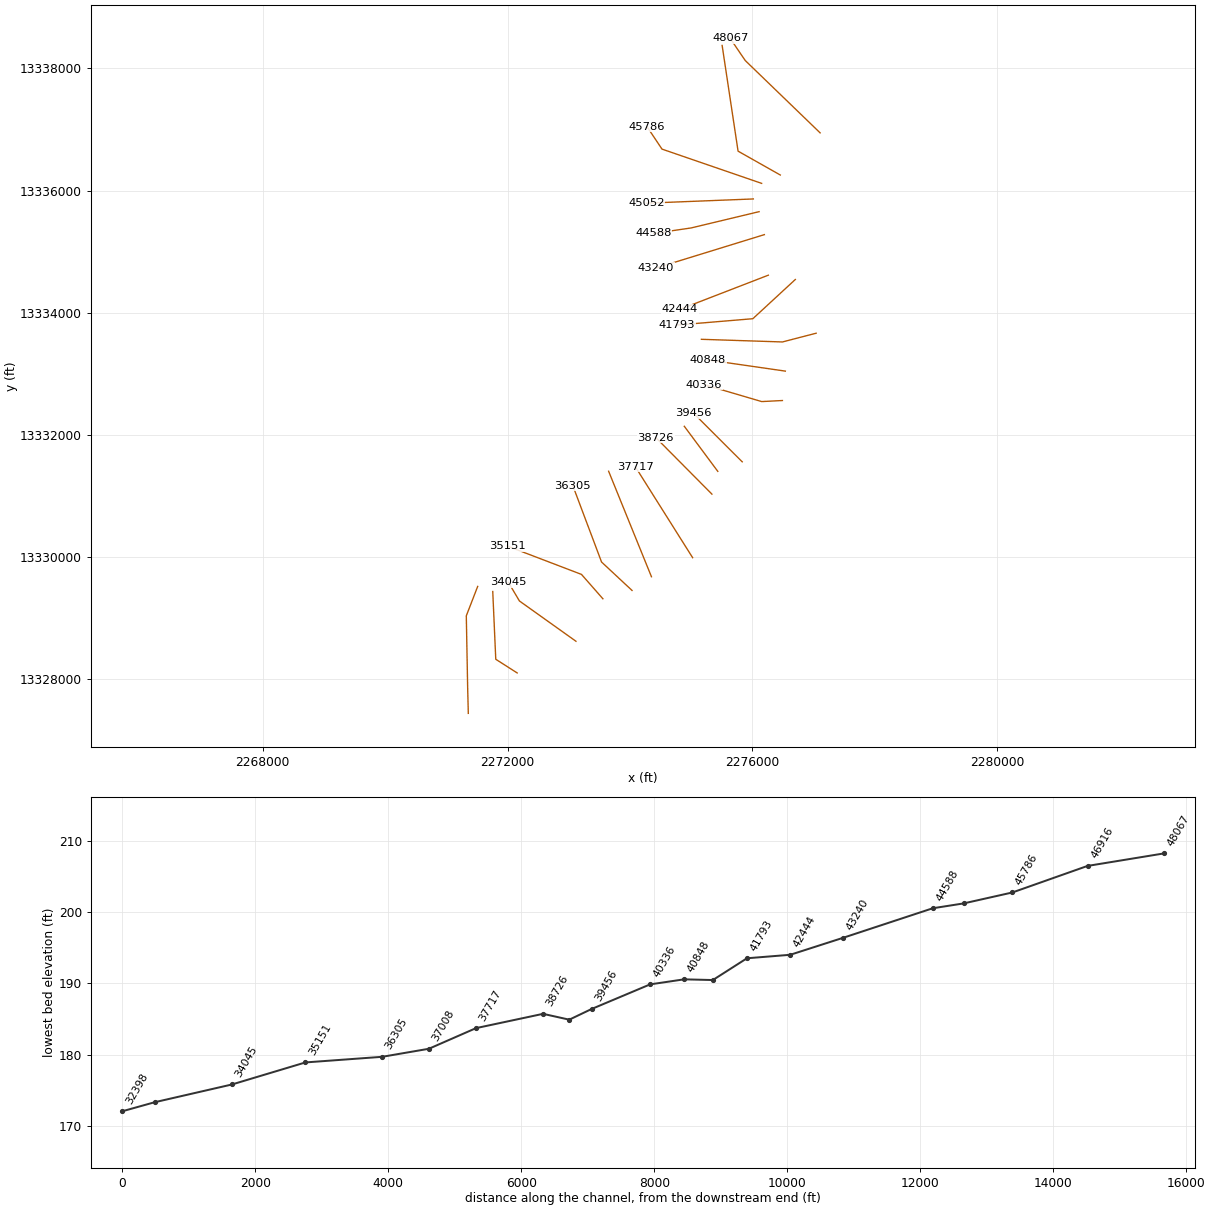
HEC-RAS study VATOSS GULLY.prj: VATOSS GULLY Base Level Engineering

--- VATOSS GULLY.g01 (geometry) --- (continued)

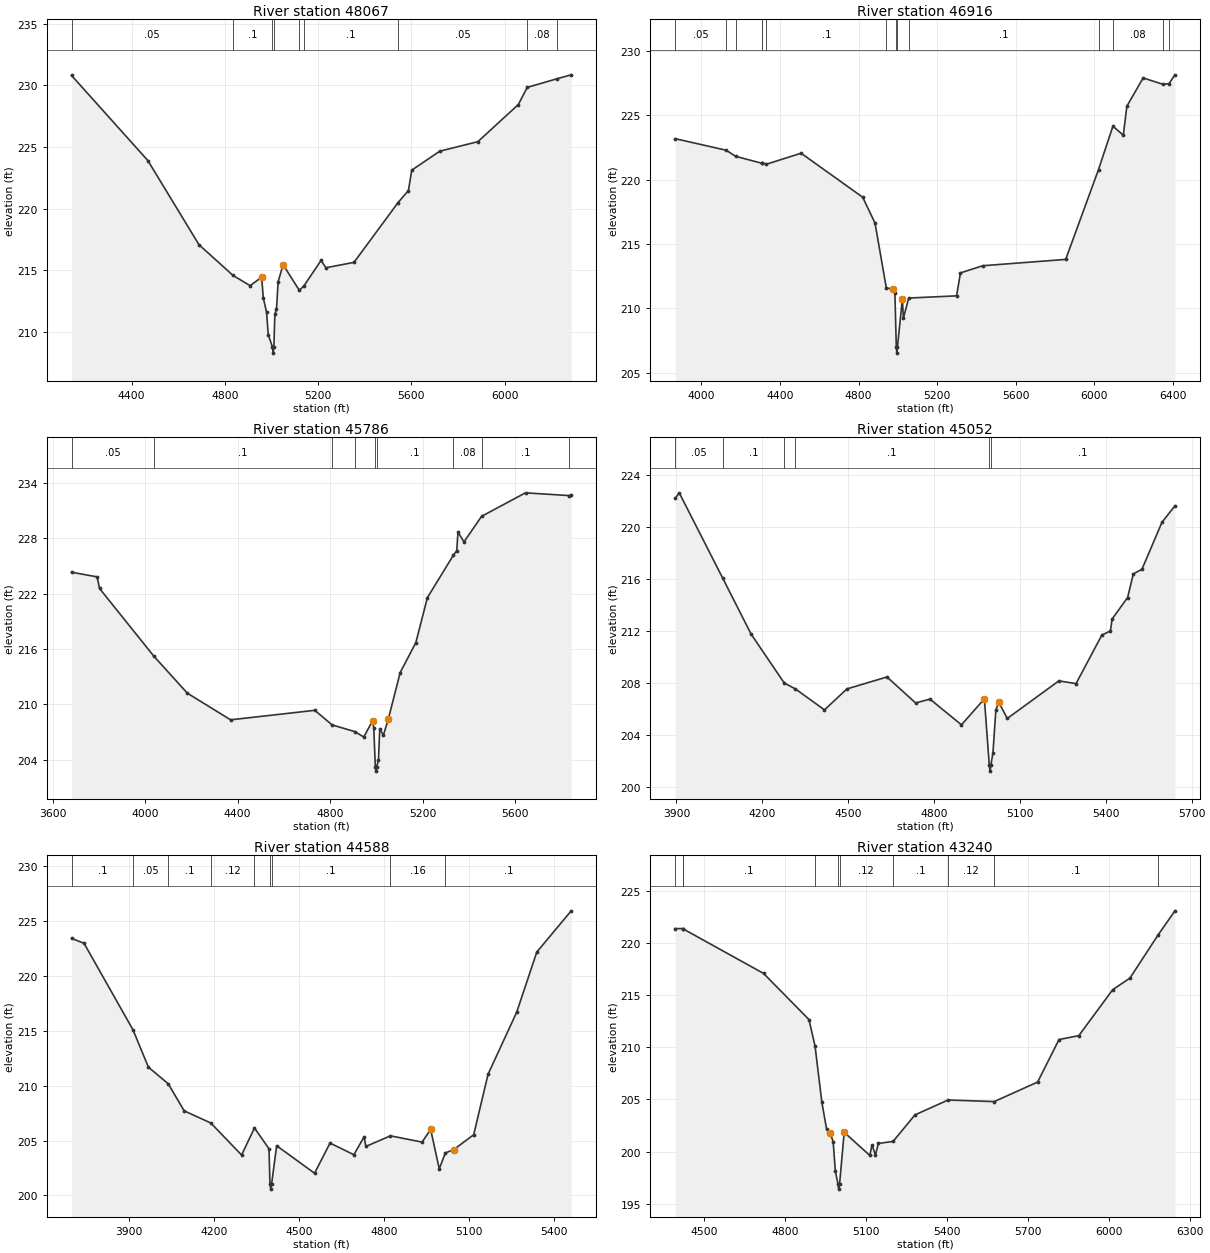
Type RM Length L Ch R = 1 ,48067   ,1151,1151,1151
BEGIN DESCRIPTION:
VATOSS GULLY 58.0
END DESCRIPTION:
XS GIS Cut Line= 3
      2277108.32      13336944.6      2275884.36     13338129.49
      2275637.72     13338492.97
#Sta/Elev= 30
  4142.4  230.79  4469.7  223.89  4688.9  217.07  4834.9  214.58  4908.3  213.75
  4957.7  214.43  4964.7  212.76  4978.8  211.59    4986  209.77  5004.1  208.78
  5006.9  208.28  5010.1  208.78  5014.3  211.43  5021.3  211.83  5028.4  214.07
  5049.6  215.45  5119.3  213.37  5138.5  213.72  5212.4  215.79  5233.5   215.2
  5353.8  215.64  5542.9  220.49  5587.2  221.46  5601.3  223.11  5721.5  224.65
  5884.8  225.42  6058.4  228.43  6096.5  229.82  6224.1  230.52  6285.2  230.84
#Mann= 9 ,-1 , 0
  4142.4     .05       0  4834.9      .1       0  5004.1     .07       0
  5010.1      .1       0  5119.3     .12       0  5138.5      .1       0
  5542.9     .05       0  6096.5     .08       0  6224.1     .05       0
Bank Sta=4957.7,5049.6
XS Rating Curve= 0 ,0
Exp/Cntr=0.3,0.1

Type RM Length L Ch R = 1 ,46916   ,1130,1130,1130
BEGIN DESCRIPTION:
VATOSS GULLY 57.0
END DESCRIPTION:
XS GIS Cut Line= 3
      2276457.29     13336254.49      2275767.18     13336645.12
      2275506.77     13338376.85
#Sta/Elev= 30
  3866.7  223.18  4126.5  222.28  4173.7  221.81  4307.7  221.27  4310.5  221.32
  4329.7  221.19  4507.5  222.05  4821.2  218.63  4883.9  216.62  4941.6  211.57
  4974.9  211.52  4985.1   211.2  4992.2  207.02  4994.9  206.52  4998.2  207.02
  5023.2  210.74  5028.2  209.23  5055.6   210.8  5299.2  210.97  5318.8  212.75
  5432.2  213.31  5854.7   213.8  6021.8  220.78  6095.1  224.15    6148  223.45
  6166.1   225.7  6249.1   227.9  6350.3   227.4  6380.8  227.46  6410.9  228.14
#Mann= 14 ,-1 , 0
  3866.7     .05       0  4126.5      .1       0  4173.7     .05       0
  4307.7      .1       0  4310.5     .05       0  4329.7      .1       0
  4941.6     .12       0  4992.2     .07       0  4998.2     .12       0
  5055.6      .1       0  6021.8     .05       0  6095.1     .08       0
  6350.3      .1       0  6380.8     .05       0
Bank Sta=4974.9,5023.2
XS Rating Curve= 0 ,0
Exp/Cntr=0.3,0.1

Type RM Length L Ch R = 1 ,45786   ,734,734,734
BEGIN DESCRIPTION:
VATOSS GULLY 56.0
END DESCRIPTION:
XS GIS Cut Line= 3
      2276152.27     13336117.62      2274524.09      13336678.6
      2274281.03      13337043.2
#Sta/Elev= 30
  3681.9  224.31  3792.5  223.81  3803.1  222.55  4037.7  215.23  4182.3  211.23
  4369.6  208.34  4733.6  209.37  4808.6  207.79  4906.1  207.07  4945.4  206.48
  4983.3  208.23  4988.6  207.48  4995.3  203.29    4998  202.79  5001.3  203.29
  5008.8  203.96  5014.5  207.39    5030  206.66  5051.1  208.39  5102.9  213.46
  5170.6   216.7  5220.4  221.56  5332.4  226.14  5347.3  226.64  5352.6  228.65
  5378.5  227.59  5454.8  230.36  5644.6   232.9  5833.5   232.6  5842.2  232.67
#Mann= 9 ,-1 , 0
  3681.9     .05       0  4037.7      .1       0  4808.6     .12       0
  4906.1      .1       0  4995.3     .07       0  5001.3      .1       0
  5332.4     .08       0  5454.8      .1       0  5833.5     .05       0
Bank Sta=4983.3,5051.1
XS Rating Curve= 0 ,0
Exp/Cntr=0.3,0.1

Type RM Length L Ch R = 1 ,45052   ,464,464,464
BEGIN DESCRIPTION:
VATOSS GULLY 55.0
END DESCRIPTION:
XS GIS Cut Line= 2
      2276016.84      13335862.4      2274272.51     13335793.19
#Sta/Elev= 30
  3895.9  222.22  3909.9  222.65    4061  216.12  4161.1  211.78  4276.9  208.02
  4315.1  207.58  4417.3  205.96  4495.5  207.57  4635.6  208.49  4735.7  206.49
  4785.7  206.79  4895.8  204.81  4975.9  206.81  4992.9  201.75  4995.6  201.25
  4998.9  201.75  5005.9  202.67  5015.9  205.93  5025.9  206.56  5055.9   205.3
  5236.1  208.19  5296.1  207.98  5386.2  211.71  5416.2  212.03  5422.2  212.95
  5476.3   214.6  5496.3  216.42  5526.3  216.77  5596.4  220.39  5641.6  221.65
#Mann= 6 ,-1 , 0
  3895.9     .05       0    4061      .1       0  4276.9     .05       0
  4315.1      .1       0  4992.9     .07       0  4998.9      .1       0
Bank Sta=4975.9,5025.9
XS Rating Curve= 0 ,0
Exp/Cntr=0.3,0.1

Type RM Length L Ch R = 1 ,44588   ,1348,1348,1348
BEGIN DESCRIPTION:
VATOSS GULLY 54.0
END DESCRIPTION:
XS GIS Cut Line= 3
      2276110.61     13335654.07      2275002.64     13335388.08
      2274387.72     13335296.85
#Sta/Elev= 30
  3698.6  223.44  3742.7  222.99  3915.4  215.09  3969.6  211.69  4039.4  210.18
  4095.6  207.71  4189.5   206.6    4298  203.68  4343.3  206.15  4394.6  204.25
  4397.9  201.07  4400.6  200.57  4403.9  201.07  4421.5  204.53  4555.1  202.02
  4609.7  204.77  4693.7  203.71    4730  205.35  4735.7  204.46  4822.6  205.43
    4934  204.86  4964.3  206.01  4994.7  202.42  5016.1  203.87  5045.2  204.17
    5116  205.53  5166.5  211.04  5267.6  216.71  5338.4  222.19  5459.7  225.95
#Mann= 9 ,-1 , 0
  3698.6      .1       0  3915.4     .05       0  4039.4      .1       0
  4189.5     .12       0  4343.3      .1       0  4397.9     .07       0
  4403.9      .1       0  4822.6     .16       0  5016.1      .1       0
Bank Sta=4964.3,5045.2
XS Rating Curve= 0 ,0
Exp/Cntr=0.3,0.1

Type RM Length L Ch R = 1 ,43240   ,796,796,796
BEGIN DESCRIPTION:
VATOSS GULLY 53.0
END DESCRIPTION:
XS GIS Cut Line= 2
      2276196.83     13335277.92      2274427.29     13334731.44
#Sta/Elev= 30
  4393.4  221.36  4420.3  221.36    4422  221.34  4720.6  217.07    4889  212.65
  4911.5  210.12  4936.7  204.76  4954.3  202.17  4968.1  201.76  4978.6  200.97
  4986.9  198.14  4996.5  196.92  4999.2  196.42  5002.5  196.92  5019.6  201.86
  5114.6  199.64  5122.7  200.66  5135.6  199.68    5146  200.79  5200.8  200.99
  5282.1  203.53  5404.6  204.95  5575.7   204.8  5736.5  206.67  5815.8  210.74
  5889.1  211.11  6014.7  215.51  6078.6  216.62  6183.5  220.77  6245.4  223.06
#Mann= 10 ,-1 , 0
  4393.4      .1       0  4420.3     .05       0    4422      .1       0
  4911.5     .12       0  4996.5     .07       0  5002.5     .12       0
  5200.8      .1       0  5404.6     .12       0  5575.7      .1       0
  6183.5     .05       0
Bank Sta=4968.1,5019.6
XS Rating Curve= 0 ,0
Exp/Cntr=0.3,0.1

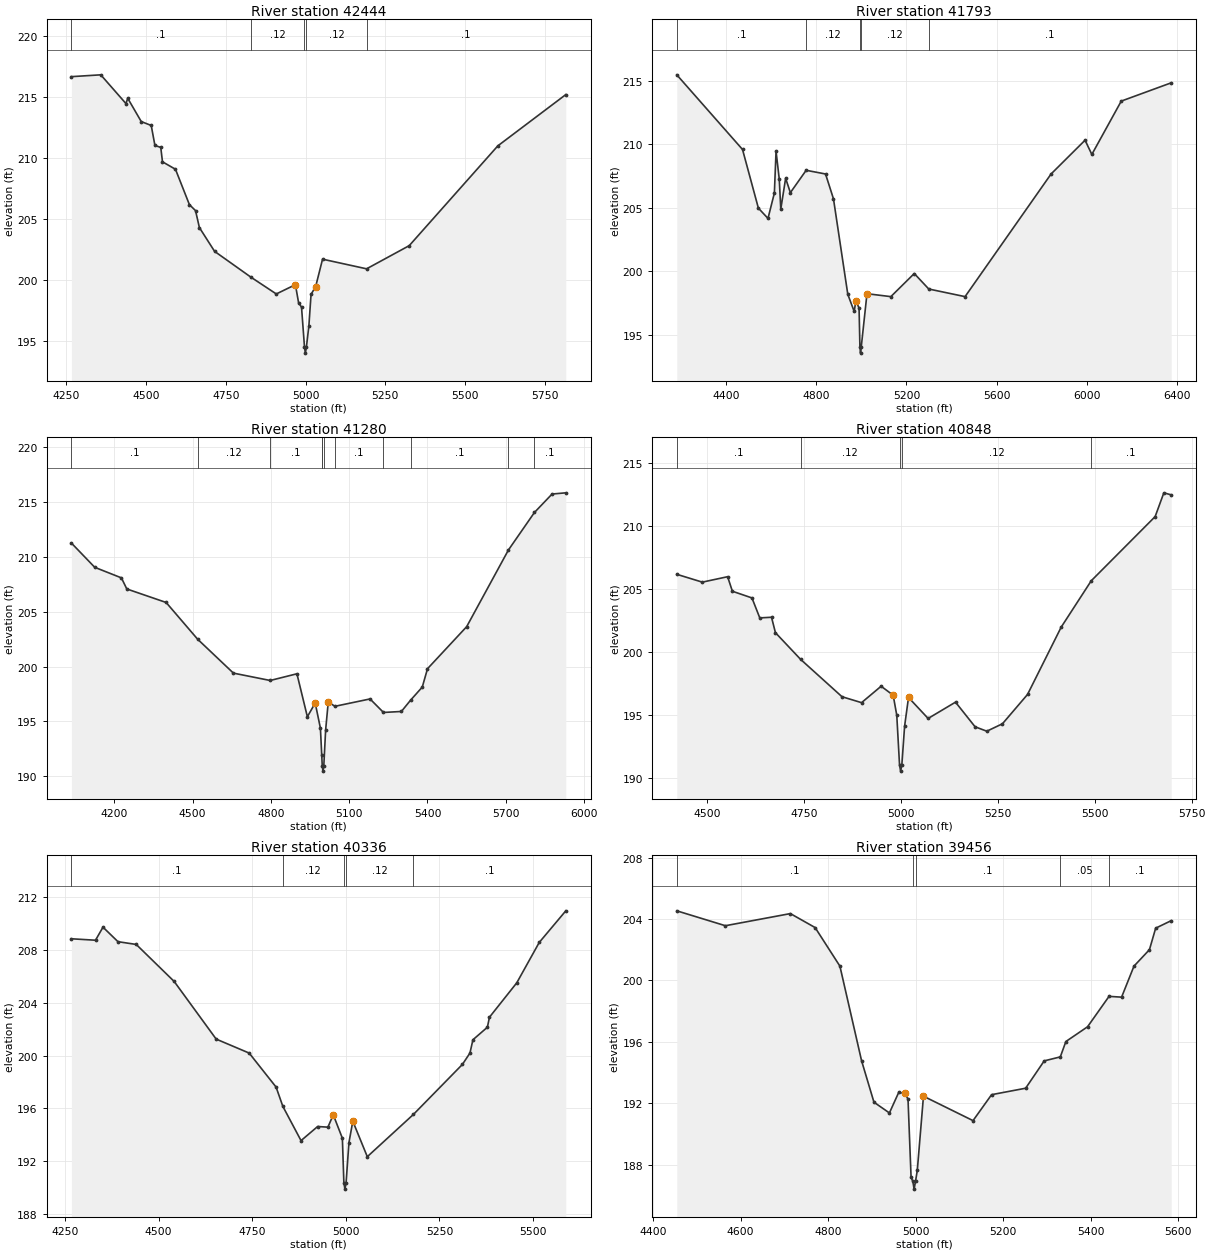
Type RM Length L Ch R = 1 ,42444   ,651,651,651
BEGIN DESCRIPTION:
VATOSS GULLY 52.0
END DESCRIPTION:
XS GIS Cut Line= 2
      2276261.95     13334613.86      2274816.61     13334053.95
#Sta/Elev= 30
    4266  216.69  4358.1  216.84  4437.2  214.48  4442.6  214.92    4485  213.01
  4516.3  212.69  4527.9  211.05  4546.2  210.89  4551.6  209.71  4592.3   209.1
    4636   206.2  4655.2  205.71  4667.3  204.32    4715  202.37  4828.6  200.26
  4908.4  198.88  4968.3  199.64  4978.3  198.16  4987.5   197.8  4996.8  194.53
  4999.5  194.03  5002.8  194.53  5010.5  196.25  5017.4  198.85  5031.9  199.49
  5053.4  201.73  5191.5  200.94  5325.2  202.84    5603  211.02    5816  215.22
#Mann= 5 ,-1 , 0
    4266      .1       0  4828.6     .12       0  4996.8     .07       0
  5002.8     .12       0  5191.5      .1       0
Bank Sta=4968.3,5031.9
XS Rating Curve= 0 ,0
Exp/Cntr=0.3,0.1

Type RM Length L Ch R = 1 ,41793   ,513,513,513
BEGIN DESCRIPTION:
VATOSS GULLY 51.0
END DESCRIPTION:
XS GIS Cut Line= 3
      2276702.93      13334543.2      2276008.47     13333900.83
      2274767.13     13333796.66
#Sta/Elev= 30
  4181.9  215.46  4473.3  209.58  4543.6  204.96  4586.2  204.15  4614.5  206.15
  4621.9  209.44  4636.1  207.26  4642.9  204.88  4664.4  207.31  4685.4  206.18
  4755.4  207.94  4841.3  207.65  4876.5  205.69    4940  198.17  4968.3  196.82
  4975.7  197.65  4989.9  197.09  4993.7  194.04  4996.4  193.54  4999.7  194.04
    5025  198.22  5130.8  197.99  5234.6  199.81  5298.9  198.59  5459.8  197.99
  5841.1  207.65  5991.7  210.31  6021.8  209.19  6152.2  213.39  6373.6  214.83
#Mann= 5 ,-1 , 0
  4181.9      .1       0  4755.4     .12       0  4993.7     .07       0
  4999.7     .12       0  5298.9      .1       0
Bank Sta=4975.7,5025
XS Rating Curve= 0 ,0
Exp/Cntr=0.3,0.1

Type RM Length L Ch R = 1 ,41280   ,432,432,432
BEGIN DESCRIPTION:
VATOSS GULLY 50.0
END DESCRIPTION:
XS GIS Cut Line= 3
      2277043.21     13333663.34        2276492.     13333520.12
      2275168.23     13333563.52
#Sta/Elev= 30
  4035.8  211.24  4125.3  209.03  4227.4  208.07  4248.1  207.06  4398.8  205.83
  4519.3  202.49  4656.5   199.4  4797.4  198.73  4899.8  199.34  4939.8  195.43
  4969.8  196.68  4989.8  194.39  4994.9  191.91  4996.8  190.98  4999.6  190.48
  5002.8  190.98  5009.8  194.23  5019.8  196.77  5045.5  196.38  5179.9  197.05
  5231.4  195.82    5300  195.91  5335.3  196.94    5380  198.13    5400   199.8
  5550.1  203.63  5710.1  210.61  5809.6  214.02  5877.2   215.7  5929.8  215.81
#Mann= 11 ,-1 , 0
  4035.8      .1       0  4519.3     .12       0  4797.4      .1       0
  4994.9     .12       0  4996.8     .07       0  5002.8     .12       0
  5045.5      .1       0  5231.4     .12       0  5335.3      .1       0
  5710.1     .05       0  5809.6      .1       0
Bank Sta=4969.8,5019.8
XS Rating Curve= 0 ,0
Exp/Cntr=0.3,0.1

Type RM Length L Ch R = 1 ,40848   ,512,512,512
BEGIN DESCRIPTION:
VATOSS GULLY 49.0
END DESCRIPTION:
XS GIS Cut Line= 2
      2276539.72     13333042.69      2275276.71     13333224.98
#Sta/Elev= 30
  4421.1  206.16    4487  205.54  4552.3  205.97  4564.6  204.82  4615.1  204.29
  4635.3  202.71  4665.6  202.76  4675.7  201.54  4740.6  199.43  4847.5  196.47
    4898     196  4948.5   197.3  4979.6  196.59  4988.9     195    4996  191.08
  4998.8  190.58    5002  191.08  5009.1  194.14  5019.2  196.41  5069.8  194.75
  5140.5  196.04    5191  194.09  5221.3  193.74  5261.7  194.33  5326.4  196.65
  5413.3  201.98  5490.9  205.65  5655.8  210.73  5678.2  212.61  5697.2  212.45
#Mann= 5 ,-1 , 0
  4421.1      .1       0  4740.6     .12       0    4996     .07       0
    5002     .12       0  5490.9      .1       0
Bank Sta=4979.6,5019.2
XS Rating Curve= 0 ,0
Exp/Cntr=0.3,0.1

Type RM Length L Ch R = 1 ,40336   ,880,880,880
BEGIN DESCRIPTION:
VATOSS GULLY 48.0
END DESCRIPTION:
XS GIS Cut Line= 3
        2276492.     13332560.91      2276153.46     13332543.55
      2275212.13     13332821.18
#Sta/Elev= 30
  4266.9  208.86  4331.3  208.75  4351.3  209.74  4391.3  208.64  4440.1  208.43
  4541.5  205.62  4653.6  201.25  4741.7  200.19  4813.6  197.61  4831.6  196.15
  4880.2  193.55  4924.6  194.62    4952  194.57  4966.3  195.51  4990.6  193.73
  4994.6  190.37  4997.4  189.87  5000.6  190.37  5008.1  193.39  5018.5  195.02
  5057.2  192.33  5180.5  195.54  5311.2  199.33  5331.3  200.19  5339.3   201.2
  5377.9  202.15  5383.4  202.91  5456.4  205.52  5516.3  208.58  5587.3  210.98
#Mann= 5 ,-1 , 0
  4266.9      .1       0  4831.6     .12       0  4994.6     .07       0
  5000.6     .12       0  5180.5      .1       0
Bank Sta=4966.3,5018.5
XS Rating Curve= 0 ,0
Exp/Cntr=0.3,0.1

Type RM Length L Ch R = 1 ,39456   ,336,336,336
BEGIN DESCRIPTION:
VATOSS GULLY 47.0
END DESCRIPTION:
XS GIS Cut Line= 2
      2275834.88     13331557.06      2275036.27     13332355.67
#Sta/Elev= 30
  4454.3  204.53  4565.3  203.56  4713.8  204.35  4770.3  203.44  4826.9  200.93
  4876.4  194.77  4904.7  192.07    4940  191.37  4961.3  192.71  4975.4  192.65
  4982.5  192.27  4989.5  187.17  4993.6  186.91  4996.4  186.41  4999.6  186.91
  5003.7  187.63  5017.8  192.46    5131  190.87  5173.4  192.56  5251.2  192.98
  5293.6  194.76  5330.4  195.02  5343.1  196.02  5392.6  196.98  5441.7  198.96
  5470.4  198.91  5498.7  200.93    5534     202  5548.2   203.4  5583.7  203.89
#Mann= 5 ,-1 , 0
  4454.3      .1       0  4993.6     .07       0  4999.6      .1       0
  5330.4     .05       0  5441.7      .1       0
Bank Sta=4975.4,5017.8
XS Rating Curve= 0 ,0
Exp/Cntr=0.3,0.1

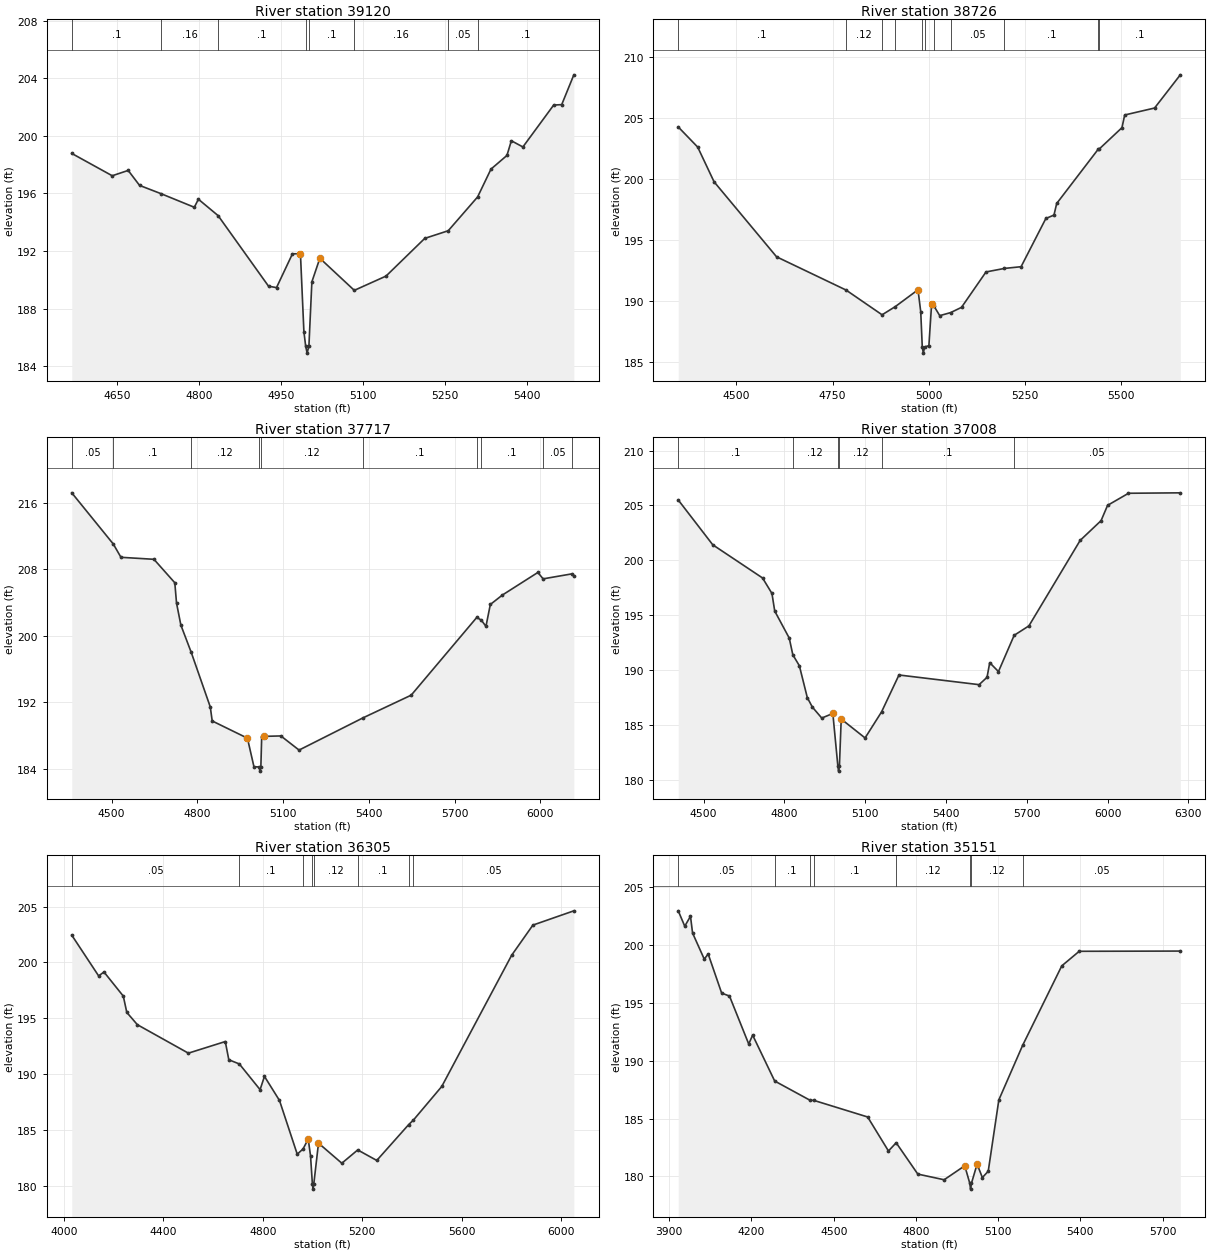
Type RM Length L Ch R = 1 ,39120   ,394,394,394
BEGIN DESCRIPTION:
VATOSS GULLY 46.0
END DESCRIPTION:
XS GIS Cut Line= 2
      2275435.56     13331400.82      2274888.69     13332138.65
#Sta/Elev= 30
  4566.7  198.78  4640.7  197.23  4669.9   197.6  4690.7  196.56  4730.3  195.98
  4790.9  195.04  4798.3   195.6  4834.4  194.46  4926.6  189.56  4941.2  189.46
  4970.4  191.81    4985  191.81  4991.3  186.41  4994.5  185.41  4997.2  184.91
  5000.5  185.41  5005.9  189.86  5020.5   191.5  5083.5  189.27  5141.5  190.26
  5212.4  192.88  5255.3  193.41  5309.1  195.76  5333.5  197.69  5362.7  198.64
  5370.8  199.66  5391.9  199.23  5448.2  202.14  5462.9  202.17  5485.1  204.24
#Mann= 8 ,-1 , 0
  4566.7      .1       0  4730.3     .16       0  4834.4      .1       0
  4994.5     .07       0  5000.5      .1       0  5083.5     .16       0
  5255.3     .05       0  5309.1      .1       0
Bank Sta=4985,5020.5
XS Rating Curve= 0 ,0
Exp/Cntr=0.3,0.1

Type RM Length L Ch R = 1 ,38726   ,1009,1009,1009
BEGIN DESCRIPTION:
VATOSS GULLY 45.0
END DESCRIPTION:
XS GIS Cut Line= 2
      2275340.04     13331027.59      2274421.32     13331954.97
#Sta/Elev= 30
  4348.9  204.26  4399.5  202.61    4442  199.77  4604.6  193.62  4785.1   190.9
  4878.9  188.87  4913.2  189.54  4972.3  190.92  4979.4  189.12  4983.4  186.23
  4986.2  185.73  4989.4  186.23  5000.6  186.34  5007.7  189.77  5013.9  189.58
  5028.8   188.8  5057.1  189.05  5085.4  189.48  5149.1  192.38  5197.1  192.67
  5240.3  192.81  5304.7  196.76  5325.8  197.04  5332.9  197.99  5441.2  202.45
  5443.4  202.45  5502.6   204.2  5509.7  205.24  5587.4  205.81  5654.3  208.53
#Mann= 11 ,-1 , 0
  4348.9      .1       0  4785.1     .12       0  4878.9      .1       0
  4913.2     .12       0  4983.4     .07       0  4989.4     .12       0
  5013.9      .1       0  5057.1     .05       0  5197.1      .1       0
  5441.2     .16       0  5443.4      .1       0
Bank Sta=4972.3,5007.7
XS Rating Curve= 0 ,0
Exp/Cntr=0.3,0.1

Type RM Length L Ch R = 1 ,37717   ,709,709,709
BEGIN DESCRIPTION:
VATOSS GULLY 44.0
END DESCRIPTION:
XS GIS Cut Line= 2
      2275024.54     13329986.69      2274089.88      13331473.4
#Sta/Elev= 30
  4360.6  217.17    4506  211.01  4532.6  209.42    4648  209.18    4721  206.36
    4727  203.92  4742.2  201.27  4778.6  197.98  4845.1  191.43  4851.8  189.75
    4975  187.68  4997.8  184.25    5016  184.22  5018.7  183.72    5022  184.22
  5024.9  187.87  5034.1   187.9    5092  187.95  5155.6  186.25  5379.7  190.13
  5547.8  192.85  5777.1  202.19    5793  201.87  5809.3  201.12  5824.6  203.75
    5867  204.89  5990.9   207.6  6009.2  206.83  6111.6  207.44  6116.7  207.19
#Mann= 10 ,-1 , 0
  4360.6     .05       0    4506      .1       0  4778.6     .12       0
    5016     .07       0    5022     .12       0  5379.7      .1       0
  5777.1     .05       0    5793      .1       0  6009.2     .05       0
  6111.6      .1       0
Bank Sta=4975,5034.1
XS Rating Curve= 0 ,0
Exp/Cntr=0.3,0.1

Type RM Length L Ch R = 1 ,37008   ,703,703,703
BEGIN DESCRIPTION:
VATOSS GULLY 43.0
END DESCRIPTION:
XS GIS Cut Line= 2
      2274351.53     13329674.78      2273651.57      13331402.8
#Sta/Elev= 30
  4405.6   205.5  4533.8  201.42  4718.7   198.4  4753.6  196.99  4763.9  195.39
  4817.8  192.93  4831.1  191.41  4855.4  190.41  4884.9  187.51  4903.6  186.65
  4938.5  185.65  4979.7  186.07  4998.2  181.32    5001  180.82  5004.2  181.32
  5010.8  185.56  5099.4  183.84  5160.6  186.21  5225.3  189.57  5522.8  188.69
  5552.3  189.36  5562.3  190.69  5594.7  189.88    5653  193.18  5707.8  194.04
  5898.1  201.82  5975.8  203.62  5999.9  205.01  6077.6  206.11    6270  206.15
#Mann= 6 ,-1 , 0
  4405.6      .1       0  4831.1     .12       0  4998.2     .07       0
  5004.2     .12       0  5160.6      .1       0    5653     .05       0
Bank Sta=4979.7,5010.8
XS Rating Curve= 0 ,0
Exp/Cntr=0.3,0.1

Type RM Length L Ch R = 1 ,36305   ,1154,1154,1154
BEGIN DESCRIPTION:
VATOSS GULLY 42.0
END DESCRIPTION:
XS GIS Cut Line= 3
      2274034.21     13329450.39      2273536.26     13329915.52
      2273065.67     13331168.57
#Sta/Elev= 30
  4031.2  202.44  4139.3  198.79  4160.8  199.14  4238.5  196.98  4252.6  195.52
  4295.1  194.42  4500.3  191.87  4648.8  192.91    4663  191.28  4705.5   190.9
  4788.8   188.6  4806.4  189.79  4866.9  187.63  4938.3  182.82  4961.7  183.29
  4982.5  184.18  4991.8  182.66  4999.1  180.19  5001.8  179.69  5005.1  180.19
  5023.8  183.81  5117.7  182.01  5181.6   183.2  5258.3  182.26  5386.6  185.47
  5405.8  185.88  5519.8  188.89  5800.9  200.64  5886.3  203.34  6051.1  204.62
#Mann= 8 ,-1 , 0
  4031.2     .05       0  4705.5      .1       0  4961.7     .12       0
  4999.1     .07       0  5005.1     .12       0  5181.6      .1       0
  5386.6     .12       0  5405.8     .05       0
Bank Sta=4982.5,5023.8
XS Rating Curve= 0 ,0
Exp/Cntr=0.3,0.1

Type RM Length L Ch R = 1 ,35151   ,1106,1106,1106
BEGIN DESCRIPTION:
VATOSS GULLY 41.0
END DESCRIPTION:
XS GIS Cut Line= 3
      2273558.12     13329313.65      2273207.95     13329713.06
      2271993.23     13330178.16
#Sta/Elev= 30
  3932.8  202.97  3956.6  201.64  3977.5   202.5  3985.1  201.05  4027.8  198.79
    4042  199.24  4091.3  195.85  4119.8   195.6    4190  191.45  4204.3  192.22
  4284.7  188.25  4412.6   186.6  4428.5  186.57  4623.9  185.14  4699.8   182.2
    4728  182.91  4806.9   180.2    4903  179.71  4978.2  180.92  4996.6   179.4
  4999.4   178.9  5002.6   179.4  5023.2  181.06  5042.5   179.9  5063.9  180.45
  5102.6  186.62  5189.3  191.33  5332.2  198.21  5395.8  199.47  5764.7  199.49
#Mann= 8 ,-1 , 0
  3932.8     .05       0  4284.7      .1       0  4412.6     .05       0
  4428.5      .1       0    4728     .12       0  4996.6     .07       0
  5002.6     .12       0  5189.3     .05       0
Bank Sta=4978.2,5023.2
XS Rating Curve= 0 ,0
Exp/Cntr=0.3,0.1

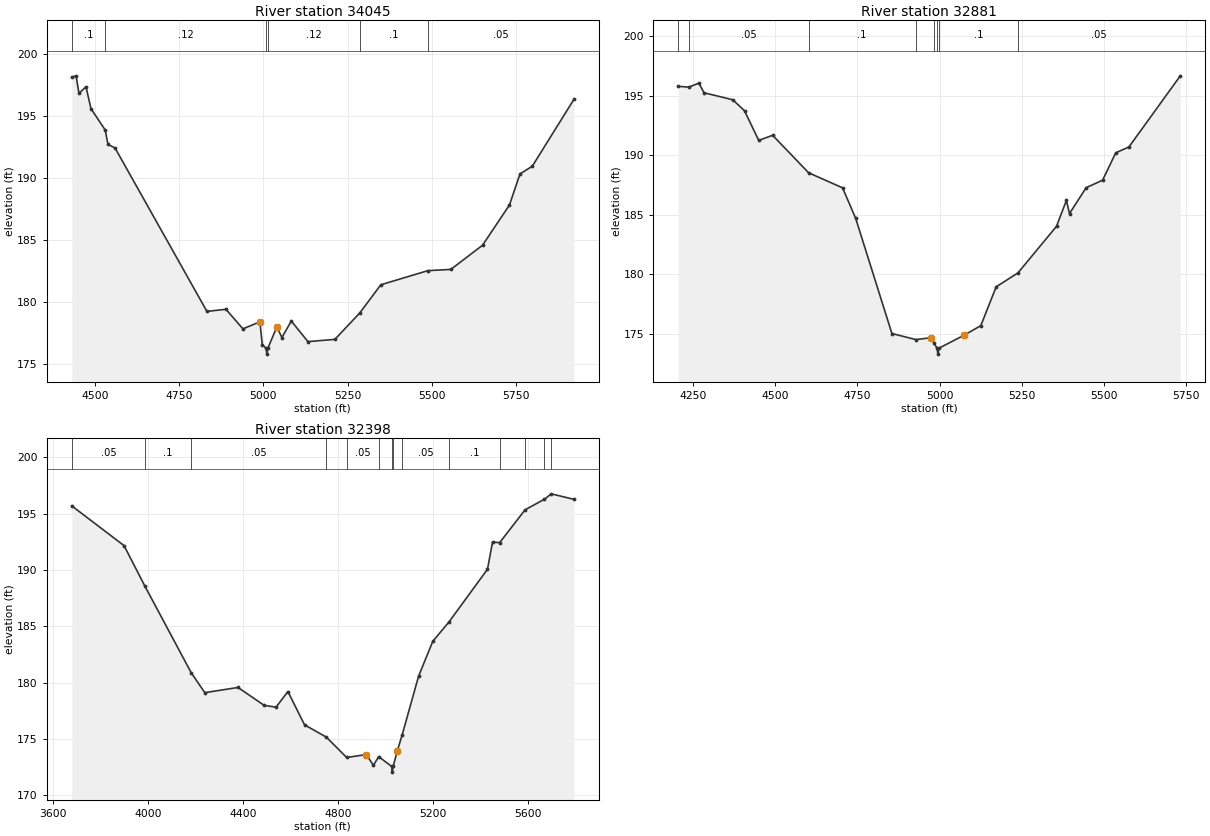
Type RM Length L Ch R = 1 ,34045   ,1164,1164,1164
BEGIN DESCRIPTION:
VATOSS GULLY 40.0
END DESCRIPTION:
XS GIS Cut Line= 3
      2273117.85     13328617.84      2272194.23     13329277.56
      2272013.47     13329583.05
#Sta/Elev= 30
  4431.4  198.17  4444.2  198.27  4452.8  196.85  4473.6  197.39  4488.4  195.62
  4530.7  193.89  4538.8  192.73  4559.7  192.45  4832.5  179.25    4889  179.42
  4939.4  177.84  4989.8  178.41  4996.9  176.53  5007.7   176.3  5010.4   175.8
  5013.7   176.3  5040.2  178.01  5054.9  177.14  5082.9  178.47  5132.3  176.81
  5212.2  176.99  5286.6  179.14  5348.6   181.4  5488.3  182.54  5556.3  182.64
  5650.4  184.59  5730.3  187.84  5761.6  190.35    5798  190.97  5921.4  196.36
#Mann= 6 ,-1 , 0
  4431.4      .1       0  4530.7     .12       0  5007.7     .07       0
  5013.7     .12       0  5286.6      .1       0  5488.3     .05       0
Bank Sta=4989.8,5040.2
XS Rating Curve= 0 ,0
Exp/Cntr=0.3,0.1

Type RM Length L Ch R = 1 ,32881   ,483,483,483
BEGIN DESCRIPTION:
VATOSS GULLY 39.0
END DESCRIPTION:
XS GIS Cut Line= 3
      2272157.36     13328098.92      2271807.19     13328323.25
        2271758.     13329432.89
#Sta/Elev= 30
  4205.2  195.78  4237.5  195.71  4268.2  196.05  4283.4  195.24    4371  194.65
  4406.7  193.73  4449.9  191.24  4492.2  191.67  4601.7  188.52  4704.8  187.26
  4744.8  184.69  4854.9  175.03  4927.7  174.52    4975  174.68  4982.4  174.25
    4992   173.8  4994.8   173.3    4998   173.8  5075.1   174.9  5125.2  175.69
  5171.9  178.95  5238.2  180.12  5355.4  184.03  5385.4   186.2  5394.9   185.1
  5445.5  187.27  5495.5   187.9  5535.6   190.2  5575.6  190.69  5731.8  196.66
#Mann= 8 ,-1 , 0
  4205.2      .1       0  4237.5     .05       0  4601.7      .1       0
  4927.7     .12       0  4982.4      .1       0    4992     .07       0
    4998      .1       0  5238.2     .05       0
Bank Sta=4975,5075.1
XS Rating Curve= 0 ,0
Exp/Cntr=0.3,0.1

Type RM Length L Ch R = 1 ,32398   ,589,589,589
BEGIN DESCRIPTION:
VATOSS GULLY 38.0
END DESCRIPTION:
XS GIS Cut Line= 4
      2271358.51     13327436.84      2271347.57     13327869.09
      2271325.68     13329034.57      2271511.73     13329516.11
#Sta/Elev= 30
  3679.3  195.69  3899.4  192.16  3987.7  188.54  4182.2  180.87  4239.5   179.1
  4379.5  179.56  4489.5  177.97  4539.5  177.81  4589.5   179.2  4659.5  176.24
  4751.4  175.15  4836.9  173.34  4919.6   173.6  4949.6  172.64  4971.7  173.42
  5026.6  172.54  5029.4  172.04  5032.6  172.54  5049.6  173.89  5070.4  175.33
  5139.6  180.55  5199.6  183.66  5267.8  185.38  5429.9  190.06  5451.3  192.48
  5481.1  192.42  5588.2  195.34  5669.8  196.28  5698.7  196.76  5793.6  196.27
#Mann= 14 ,-1 , 0
  3679.3     .05       0  3987.7      .1       0  4182.2     .05       0
  4751.4      .1       0  4836.9     .05       0  4971.7      .1       0
  5026.6     .07       0  5032.6      .1       0  5070.4     .05       0
  5267.8      .1       0  5481.1     .05       0  5588.2      .1       0
  5669.8     .05       0  5698.7      .1       0
Bank Sta=4919.6,5049.6
XS Rating Curve= 0 ,0
Exp/Cntr=0.3,0.1