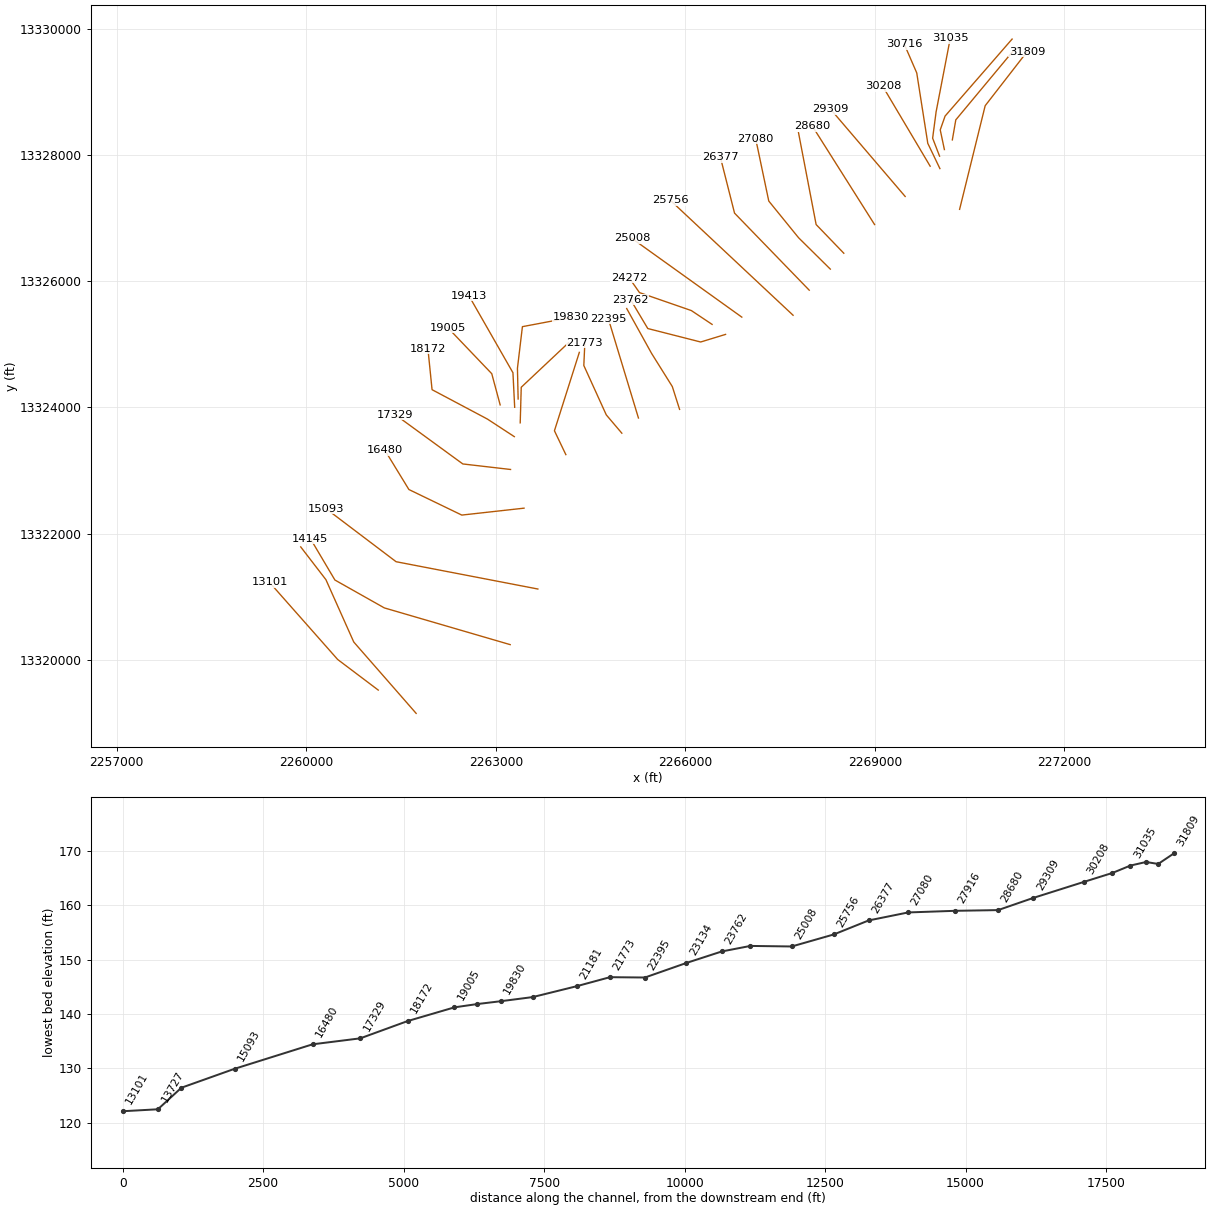
HEC-RAS study VATOSS GULLY.prj: VATOSS GULLY Base Level Engineering

--- VATOSS GULLY.g01 (geometry) --- (continued)

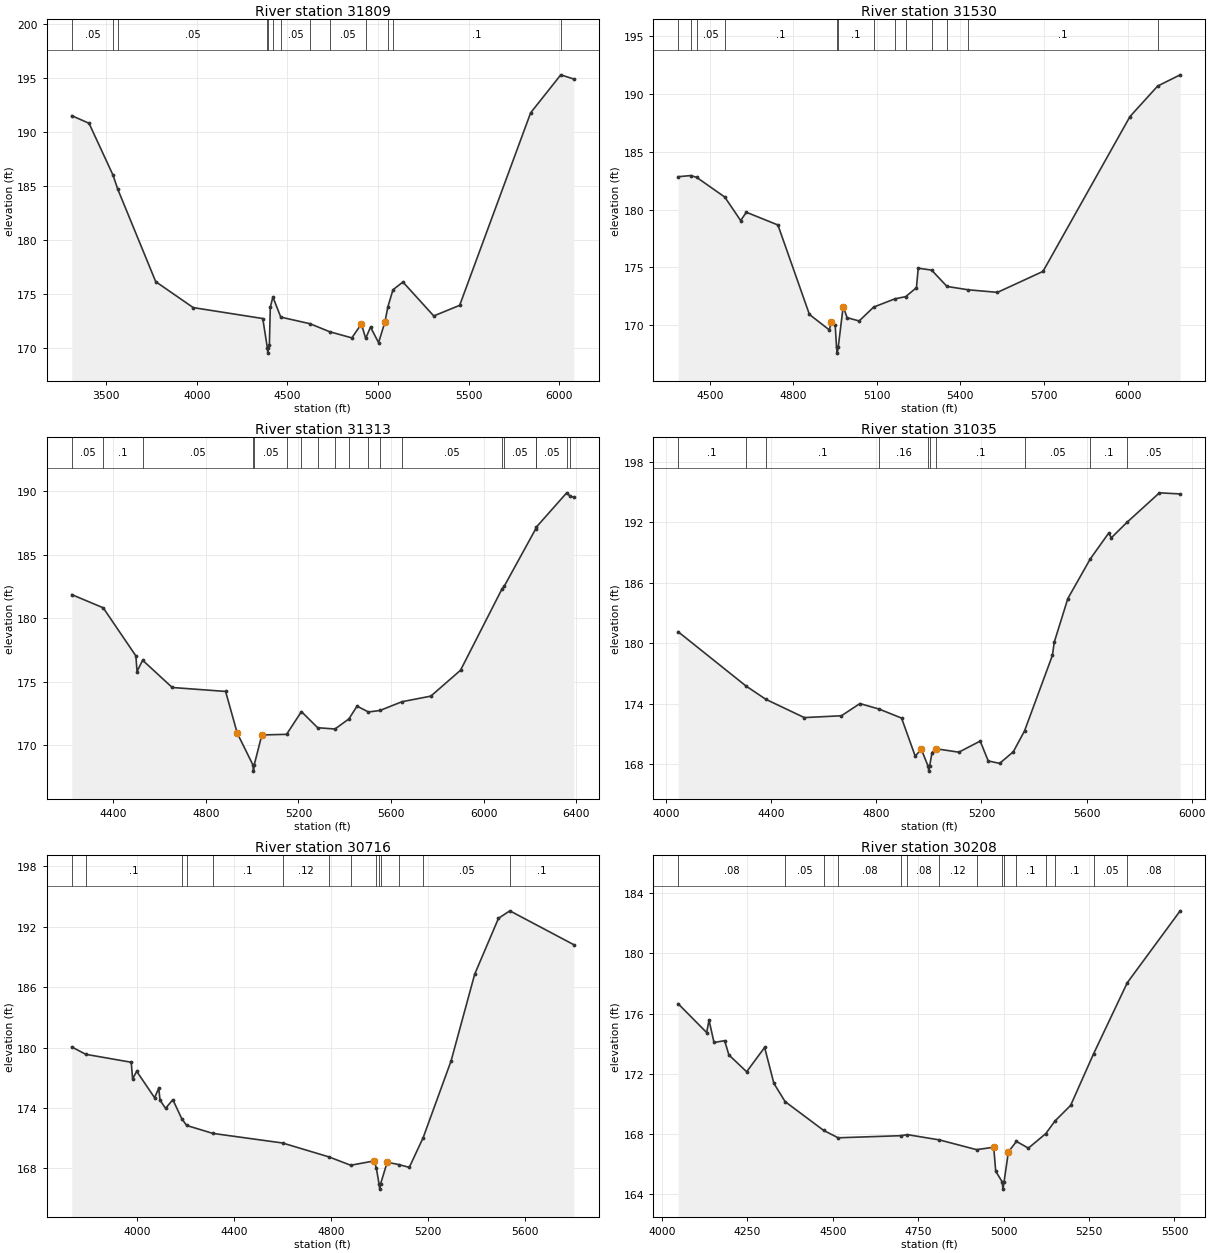
Type RM Length L Ch R = 1 ,31809   ,279,279,279
BEGIN DESCRIPTION:
Mapping XS 911d6900
END DESCRIPTION:
XS GIS Cut Line= 3
      2270340.78     13327135.91      2270745.68      13328777.4
      2271407.73     13329630.95
#Sta/Elev= 30
  3309.8   191.5    3405   190.8  3537.3  186.01  3563.5  184.71  3773.2  176.15
  3980.3  173.75  4364.1  172.74  4389.2  170.04    4392  169.54  4395.2  170.04
  4400.5  170.25  4405.6  173.78  4419.9  174.73  4463.5  172.87  4624.8  172.26
  4733.2  171.52  4855.7  170.95  4908.5  172.24  4932.1   170.9  4958.7  171.95
  5003.3  170.51  5037.8  172.39  5054.7  173.83  5082.8   175.4  5137.6  176.12
  5307.8  172.98  5450.8  173.96  5842.7  191.77    6009  195.28  6080.7  194.89
#Mann= 13 ,-1 , 0
  3309.8     .05       0  3537.3      .1       0  3563.5     .05       0
  4389.2     .07       0  4395.2     .05       0  4419.9      .1       0
  4463.5     .05       0  4624.8      .1       0  4733.2     .05       0
  4932.1      .1       0  5054.7     .05       0  5082.8      .1       0
    6009     .05       0
Bank Sta=4908.5,5037.8
XS Rating Curve= 0 ,0
Exp/Cntr=0.3,0.1

Type RM Length L Ch R = 1 ,31530   ,217,217,217
BEGIN DESCRIPTION:
Mapping XS 8e58640e
END DESCRIPTION:
XS GIS Cut Line= 3
      2270225.87     13328235.72      2270280.58     13328553.06
      2271227.16     13329691.14
#Sta/Elev= 30
  4386.8  182.84  4432.8  182.94  4453.5  182.78  4554.2  181.08  4611.2  179.05
  4631.5  179.77  4744.9  178.67  4858.1  170.94  4929.7   169.6  4936.2   170.3
  4950.6  170.02  4955.4   168.1  4958.1   167.6  4961.4   168.1  4979.2  171.62
  4993.5  170.66  5036.5  170.38  5088.8  171.58    5165  172.29  5203.7  172.48
  5242.2  173.25  5248.7  174.94  5296.7  174.77    5352  173.36  5428.3  173.07
  5533.2  172.85  5696.6  174.66    6009  188.04  6108.2  190.67  6189.1  191.64
#Mann= 13 ,-1 , 0
  4386.8     .05       0  4432.8      .1       0  4453.5     .05       0
  4554.2      .1       0  4955.4     .07       0  4961.4      .1       0
  5088.8     .05       0    5165      .1       0  5203.7     .05       0
  5296.7      .1       0    5352     .05       0  5428.3      .1       0
  6108.2     .05       0
Bank Sta=4936.2,4979.2
XS Rating Curve= 0 ,0
Exp/Cntr=0.3,0.1

Type RM Length L Ch R = 1 ,31313   ,278,278,278
BEGIN DESCRIPTION:
Mapping XS f3556188
END DESCRIPTION:
XS GIS Cut Line= 4
      2270100.01     13328082.53      2270034.36     13328394.38
      2270110.96     13328613.25      2271171.76     13329832.62
#Sta/Elev= 30
  4221.5  181.87  4357.2  180.83  4498.2  177.04  4503.3  175.81  4527.3   176.7
  4655.2  174.55  4885.5  174.24  4935.8  170.95  5003.1  168.46  5005.8  167.96
  5009.1  168.46  5041.9  170.81  5148.7  170.86  5212.8  172.65    5283  171.38
  5357.5  171.28  5417.4  172.07  5452.8  173.08  5502.2  172.62  5551.7  172.74
  5646.9  173.43  5771.3  173.87  5899.5  175.91    6078   182.3    6089  182.56
  6223.4  187.03  6225.8  187.17  6357.7  189.89  6370.5  189.66  6388.3  189.53
#Mann= 19 ,-1 , 0
  4221.5     .05       0  4357.2      .1       0  4527.3     .05       0
  5003.1     .04       0  5009.1     .05       0  5148.7      .1       0
  5212.8     .05       0    5283      .1       0  5357.5     .05       0
  5417.4      .1       0  5502.2     .05       0  5551.7      .1       0
  5646.9     .05       0    6078      .1       0    6089     .05       0
  6223.4      .1       0  6225.8     .05       0  6357.7      .1       0
  6370.5     .08       0
Bank Sta=4935.8,5041.9
XS Rating Curve= 0 ,0
Exp/Cntr=0.3,0.1

Type RM Length L Ch R = 1 ,31035   ,319,319,319
BEGIN DESCRIPTION:
Mapping XS 4d8f43d7
END DESCRIPTION:
XS GIS Cut Line= 4
      2270023.42     13327978.49      2269913.98     13328263.06
      2269968.69     13328678.91      2270193.04     13329844.39
#Sta/Elev= 30
  4045.2  181.12  4303.6  175.74  4379.2  174.42  4525.4  172.61  4666.6  172.79
  4737.2     174  4810.7  173.45  4895.7  172.56  4947.6  168.79  4971.1  169.46
  4996.5   167.8  4999.2   167.3  5002.5   167.8  5011.8  169.14  5026.8  169.52
  5113.7  169.18  5195.1  170.28  5225.7  168.31  5269.2  168.07  5321.1  169.22
  5363.9  171.29  5470.1  178.79  5476.9  180.08  5528.8  184.42    5614  188.34
    5684   190.9  5694.7  190.45  5753.7  191.97  5877.4   194.9  5956.4  194.79
#Mann= 10 ,-1 , 0
  4045.2      .1       0  4303.6     .05       0  4379.2      .1       0
  4810.7     .16       0  4996.5     .07       0  5002.5     .16       0
  5026.8      .1       0  5363.9     .05       0    5614      .1       0
  5753.7     .05       0
Bank Sta=4971.1,5026.8
XS Rating Curve= 0 ,0
Exp/Cntr=0.3,0.1

Type RM Length L Ch R = 1 ,30716   ,508,508,508
BEGIN DESCRIPTION:
Mapping XS 2818fcdd
END DESCRIPTION:
XS GIS Cut Line= 4
       2270028.9      13327781.5      2269837.37     13328180.98
      2269662.28     13329297.21      2269465.31     13329751.34
#Sta/Elev= 30
  3731.9  180.06  3789.7  179.33  3976.9  178.54  3982.4   176.9  3999.5  177.64
  4073.1  175.02  4090.2  175.97  4095.7  174.76  4118.4  173.97  4148.2  174.83
  4184.8  172.95  4205.1  172.27  4313.1  171.48    4600  170.53    4791  169.15
    4881  168.32  4977.4  168.75  4986.4  168.05  4997.8  166.45  5000.5  165.95
  5003.8  166.45  5031.1  168.62    5080  168.38  5122.2  168.11  5179.4  171.06
  5294.3  178.67  5391.6  187.28  5489.7  192.83  5536.5  193.57  5799.8  190.21
#Mann= 14 ,-1 , 0
  3731.9     .05       0  3789.7      .1       0  4184.8     .05       0
  4205.1     .12       0  4313.1      .1       0    4600     .12       0
    4791      .1       0    4881     .16       0  4986.4      .1       0
  4997.8     .07       0  5003.8      .1       0    5080     .16       0
  5179.4     .05       0  5536.5      .1       0
Bank Sta=4977.4,5031.1
XS Rating Curve= 0 ,0
Exp/Cntr=0.3,0.1

Type RM Length L Ch R = 1 ,30208   ,899,899,899
BEGIN DESCRIPTION:
Mapping XS 87913b8e
END DESCRIPTION:
XS GIS Cut Line= 2
      2269874.78     13327819.24      2269125.17     13329082.47
#Sta/Elev= 30
  4047.8  176.65  4131.2  174.73  4138.1  175.56  4152.7  174.07  4183.9  174.19
  4196.2  173.24  4248.2  172.12  4300.8  173.74    4328  171.34  4360.8  170.13
  4473.6  168.21  4515.8  167.72  4699.2  167.86  4718.4  167.93    4812  167.58
  4920.9  166.93  4971.1  167.09    4977  165.49  4995.5   164.8  4998.3   164.3
  5001.5   164.8    5014  166.78  5037.6  167.48  5072.5  167.03  5123.5     168
  5150.4  168.84  5196.2  169.88  5263.2  173.31  5361.9  178.05  5516.7  182.84
#Mann= 15 ,-1 , 0
  4047.8     .08       0  4360.8     .05       0  4473.6     .12       0
  4515.8     .08       0  4699.2      .1       0  4718.4     .08       0
    4812     .12       0  4920.9     .08       0  4995.5     .07       0
  5001.5     .08       0  5037.6      .1       0  5123.5     .08       0
  5150.4      .1       0  5263.2     .05       0  5361.9     .08       0
Bank Sta=4971.1,5014
XS Rating Curve= 0 ,0
Exp/Cntr=0.3,0.1

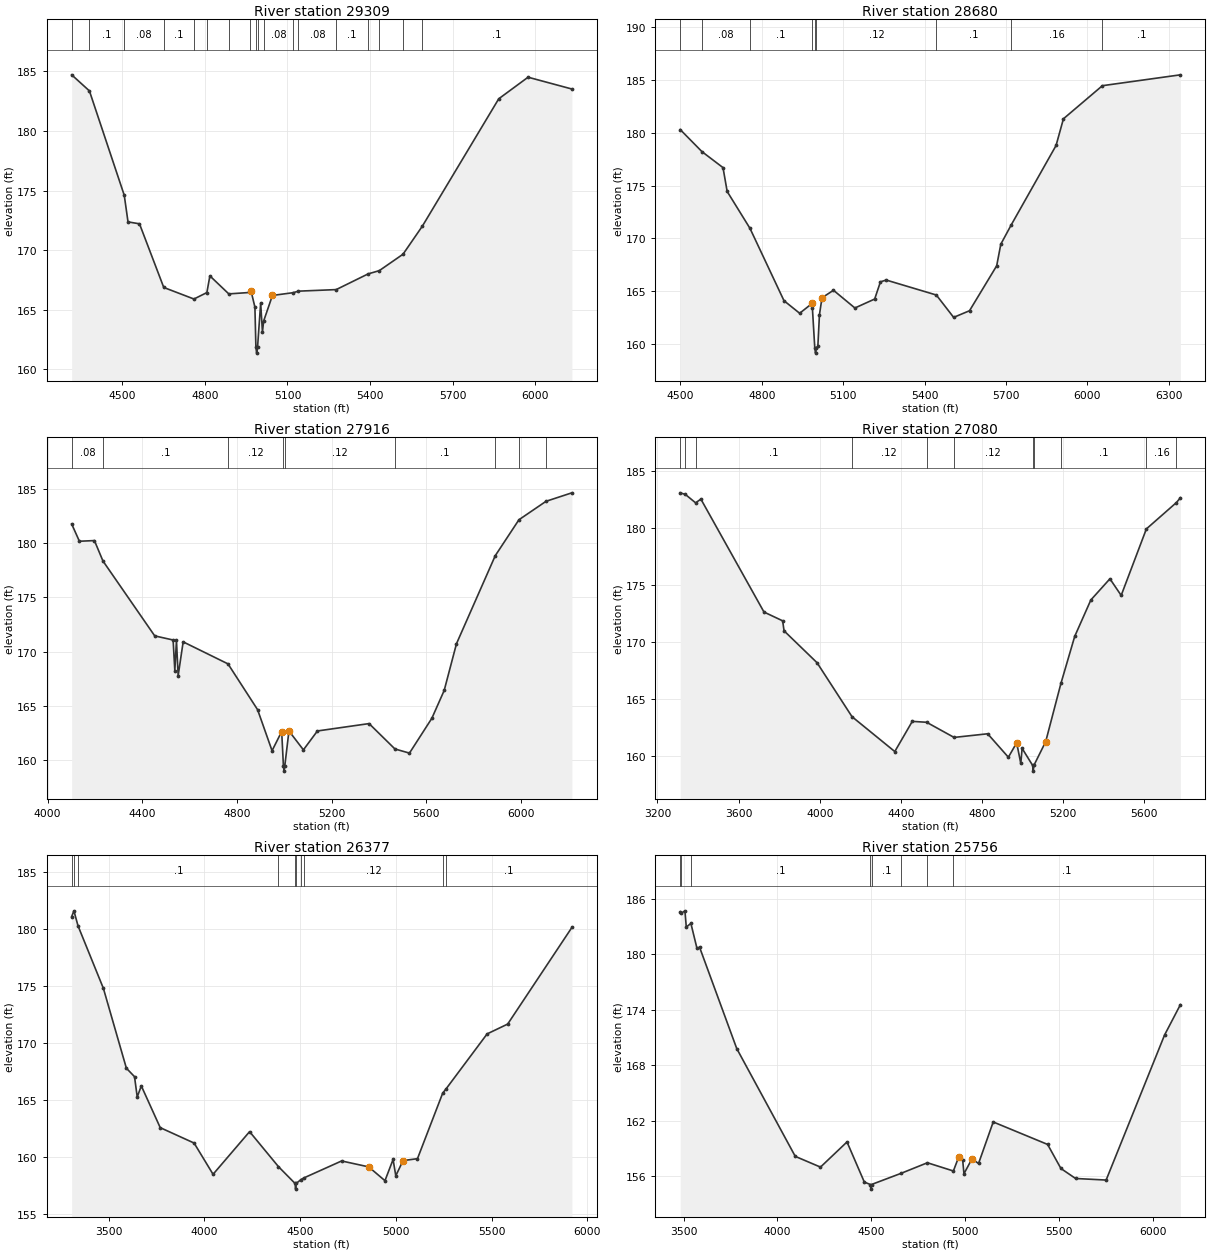
Type RM Length L Ch R = 1 ,29309   ,629,629,629
BEGIN DESCRIPTION:
Mapping XS f5057f63
END DESCRIPTION:
XS GIS Cut Line= 2
      2269478.97     13327340.04      2268298.45     13328721.95
#Sta/Elev= 30
    4316  184.71  4380.5  183.36  4507.1   174.6  4520.7  172.37  4562.4  172.21
  4650.6  166.87  4760.3   165.9  4807.2  166.44  4818.2  167.84  4886.9  166.33
  4963.8  166.45  4967.5   166.6  4981.8  165.22  4985.4  161.86  4988.1  161.36
  4991.4  161.86  5002.7  165.56  5009.2  163.13  5013.5  164.05  5045.5   166.2
  5120.5  166.43  5140.1  166.56  5277.1  166.69  5393.4  168.01  5433.7  168.28
    5520  169.66  5590.4  172.02  5867.8   182.7  5974.3  184.51  6133.5  183.52
#Mann= 18 ,-1 , 0
    4316     .05       0  4380.5      .1       0  4507.1     .08       0
  4650.6      .1       0  4760.3     .08       0  4807.2     .12       0
  4886.9     .08       0  4963.8      .1       0  4985.4     .07       0
  4991.4      .1       0  5013.5     .08       0  5120.5     .12       0
  5140.1     .08       0  5277.1      .1       0  5393.4     .08       0
  5433.7      .1       0    5520     .08       0  5590.4      .1       0
Bank Sta=4967.5,5045.5
XS Rating Curve= 0 ,0
Exp/Cntr=0.3,0.1

Type RM Length L Ch R = 1 ,28680   ,764,764,764
BEGIN DESCRIPTION:
Mapping XS 6f5192c5
END DESCRIPTION:
XS GIS Cut Line= 2
      2268994.75      13326895.1      2268010.65     13328453.25
#Sta/Elev= 30
  4499.8  180.31  4579.8  178.22  4657.5   176.7  4672.8  174.44  4756.9  170.94
  4882.2  164.08  4939.9  162.89  4985.7  163.82  4986.9  163.37  4995.6  159.61
  4998.4  159.11  5001.6  159.61  5006.9  159.74  5012.8  162.75  5022.2  164.36
  5064.5  165.07  5143.4  163.39  5216.3  164.24  5237.5  165.87  5258.8  166.04
  5443.5  164.62  5507.2   162.5  5565.7  163.13  5665.8  167.39    5681  169.44
  5719.2  171.26  5884.6   178.8  5911.7  181.33  6055.3  184.47  6342.7   185.5
#Mann= 9 ,-1 , 0
  4499.8      .1       0  4579.8     .08       0  4756.9      .1       0
  4986.9     .12       0  4995.6     .07       0  5001.6     .12       0
  5443.5      .1       0  5719.2     .16       0  6055.3      .1       0
Bank Sta=4985.7,5022.2
XS Rating Curve= 0 ,0
Exp/Cntr=0.3,0.1

Type RM Length L Ch R = 1 ,27916   ,836,836,836
BEGIN DESCRIPTION:
VATOSS GULLY 31.0
END DESCRIPTION:
XS GIS Cut Line= 3
      2268507.78     13326440.94      2268070.01     13326895.13
      2267790.95     13328350.61
#Sta/Elev= 30
  4101.9  181.75  4134.5  180.16    4198  180.22    4234  178.34  4452.7  171.44
  4530.4  171.06  4537.6  168.24  4544.5  171.02  4551.7  167.78  4572.8  170.89
  4762.2  168.86  4887.2  164.64  4948.3  160.86    4989  162.63  4996.2  159.48
    4999  158.98  5002.2  159.48  5019.6  162.68  5080.7  160.94  5139.9  162.68
  5358.1  163.36  5467.4  161.02  5528.7  160.64  5623.3  163.85  5675.3  166.41
  5727.3  170.72  5891.1  178.83  5991.1  182.14  6105.6  183.84  6214.7  184.62
#Mann= 9 ,-1 , 0
  4101.9     .08       0    4234      .1       0  4762.2     .12       0
  4996.2     .07       0  5002.2     .12       0  5467.4      .1       0
  5891.1     .16       0  5991.1      .1       0  6105.6     .16       0
Bank Sta=4989,5019.6
XS Rating Curve= 0 ,0
Exp/Cntr=0.3,0.1

Type RM Length L Ch R = 1 ,27080   ,703,703,703
BEGIN DESCRIPTION:
VATOSS GULLY 30.0
END DESCRIPTION:
XS GIS Cut Line= 4
      2268294.32      13326189.3      2267790.95      13326687.2
      2267320.38      13327267.2       2267112.6     13328256.92
#Sta/Elev= 30
    3312  183.12  3337.4  182.98    3388  182.24  3413.9  182.57  3725.1  172.65
    3817  171.88  3824.1     171  3986.7   168.2  4159.1  163.46    4370   160.4
  4456.3  163.05    4527  162.97  4662.3  161.64  4827.9  161.96    4930   159.9
  4970.9  161.17  4991.3  159.35  4997.7  160.68  5049.7  159.18  5052.4  158.68
  5055.7  159.18    5114  161.27  5189.1  166.38    5257  170.51  5336.6  173.71
  5430.7  175.57  5486.2  174.11  5610.4  179.95  5758.8  182.27  5778.2  182.69
#Mann= 11 ,-1 , 0
    3312      .1       0  3337.4     .08       0    3388      .1       0
  4159.1     .12       0    4527      .1       0  4662.3     .12       0
  5049.7     .07       0  5055.7     .12       0  5189.1      .1       0
  5610.4     .16       0  5758.8      .1       0
Bank Sta=4970.9,5114
XS Rating Curve= 0 ,0
Exp/Cntr=0.3,0.1

Type RM Length L Ch R = 1 ,26377   ,621,621,621
BEGIN DESCRIPTION:
VATOSS GULLY 29.0
END DESCRIPTION:
XS GIS Cut Line= 3
      2267960.58      13325855.5      2266778.68     13327075.69
      2266554.37       13327962.
#Sta/Elev= 30
  3306.7   181.1  3318.4  181.61  3339.9  180.29  3472.4  174.81  3592.5  167.81
    3635  167.07  3649.1  165.29  3670.5  166.26  3769.3   162.6  3946.2  161.25
  4045.3  158.51  4236.1  162.25    4387  159.18  4473.6  157.71  4476.4  157.21
  4479.6  157.71  4504.8  158.05  4520.6   158.2  4716.9  159.68  4858.4  159.16
  4943.3  157.95  4985.7  159.81  4999.9  158.38  5037.6  159.71  5113.1  159.88
    5245  165.63  5260.3  165.95    5477  170.82  5584.3  171.68  5919.7  180.15
#Mann= 10 ,-1 , 0
  3306.7      .1       0  3318.4     .08       0  3339.9      .1       0
    4387     .12       0  4473.6     .07       0  4479.6     .12       0
  4504.8      .1       0  4520.6     .12       0    5245     .16       0
  5260.3      .1       0
Bank Sta=4858.4,5037.6
XS Rating Curve= 0 ,0
Exp/Cntr=0.3,0.1

Type RM Length L Ch R = 1 ,25756   ,748,748,748
BEGIN DESCRIPTION:
VATOSS GULLY 28.0
END DESCRIPTION:
XS GIS Cut Line= 2
      2267705.09     13325458.49      2265761.68       13327280.
#Sta/Elev= 30
  3482.2  184.61  3486.6  184.43  3507.3  184.71  3514.6  182.96  3539.1  183.35
  3571.3  180.67  3585.4  180.77  3783.3  169.82  4094.9  158.17  4229.2  157.01
  4370.4  159.73  4462.7  155.39  4494.9  155.13  4497.6  154.63  4500.9  155.13
    4660  156.35  4798.5  157.48  4936.9  156.59  4964.9  158.09  4986.2  157.82
  4993.2  156.29  5035.7   157.9  5070.9   157.4    5149  161.89  5438.7  159.46
  5509.5  156.86  5587.6  155.78  5750.3  155.61  6061.5  171.29  6145.8  174.57
#Mann= 8 ,-1 , 0
  3482.2      .1       0  3486.6     .08       0  3539.1      .1       0
  4494.9     .07       0  4500.9      .1       0    4660     .16       0
  4798.5     .12       0  4936.9      .1       0
Bank Sta=4964.9,5035.7
XS Rating Curve= 0 ,0
Exp/Cntr=0.3,0.1

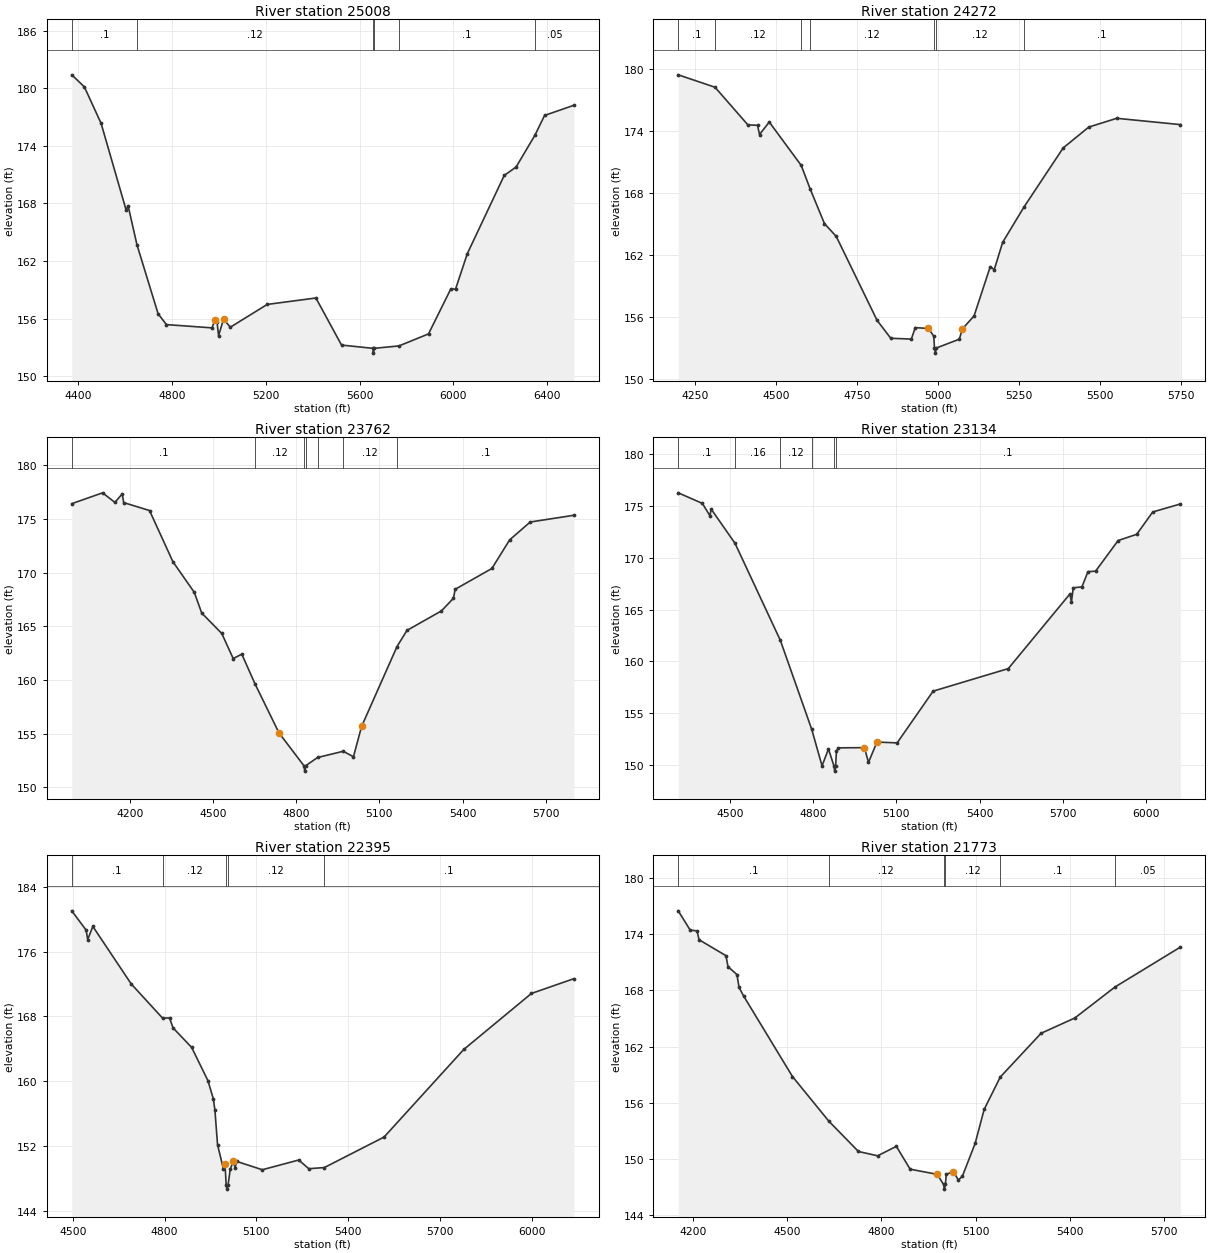
Type RM Length L Ch R = 1 ,25008   ,736,736,736
BEGIN DESCRIPTION:
VATOSS GULLY 27.0
END DESCRIPTION:
XS GIS Cut Line= 2
      2266893.63     13325428.68      2265153.57     13326676.27
#Sta/Elev= 30
  4372.5  181.39  4426.1  180.14  4497.4  176.35  4604.2  167.32  4612.8  167.76
  4650.4  163.71  4740.6  156.52  4776.2  155.39  4970.4  155.05  4983.7  155.91
  4992.3  155.62  4998.5  154.23  5019.6  155.95  5048.8  155.12    5206  157.49
  5413.6  158.16  5522.9  153.26  5656.2  152.92  5658.9  152.42  5662.2  152.92
  5767.7  153.17  5893.8  154.42  5988.4  159.08  6009.2  159.09  6059.6  162.79
  6216.8  170.92  6267.2  171.79  6348.1  175.12  6388.7  177.16  6513.6  178.22
#Mann= 6 ,-1 , 0
  4372.5      .1       0  4650.4     .12       0  5656.2     .07       0
  5662.2     .12       0  5767.7      .1       0  6348.1     .05       0
Bank Sta=4983.7,5019.6
XS Rating Curve= 0 ,0
Exp/Cntr=0.3,0.1

Type RM Length L Ch R = 1 ,24272   ,510,510,510
BEGIN DESCRIPTION:
VATOSS GULLY 26.0
END DESCRIPTION:
XS GIS Cut Line= 4
      2266423.05     13325313.78      2266094.72     13325532.67
      2265273.96      13325817.2      2265110.02     13326052.18
#Sta/Elev= 30
  4197.5  179.47    4311  178.27  4412.3  174.63  4442.3  174.58  4448.4  173.69
  4478.4   174.9  4577.1   170.7  4604.7  168.42  4648.9  165.06  4685.3  163.82
  4811.2   155.7  4853.5  153.96    4917  153.88  4929.2  154.99    4970  154.91
  4986.2  154.16  4988.5  153.02  4991.2  152.52  4994.5  153.02  5065.2  153.87
  5074.3  154.85  5110.7  156.13  5160.5  160.88    5173  160.61  5198.9  163.25
  5265.2  166.69  5385.7  172.39  5464.7  174.41  5551.1  175.26  5747.3  174.65
#Mann= 7 ,-1 , 0
  4197.5      .1       0    4311     .12       0  4577.1      .1       0
  4604.7     .12       0  4988.5     .07       0  4994.5     .12       0
  5265.2      .1       0
Bank Sta=4970,5074.3
XS Rating Curve= 0 ,0
Exp/Cntr=0.3,0.1

Type RM Length L Ch R = 1 ,23762   ,628,628,628
BEGIN DESCRIPTION:
VATOSS GULLY 25.0
END DESCRIPTION:
XS GIS Cut Line= 4
      2266636.38     13325155.11      2266242.45     13325034.74
      2265405.28     13325248.14      2265132.22     13325706.88
#Sta/Elev= 30
  3991.4  176.42  4102.5  177.43  4146.8  176.54  4173.3  177.33  4178.5  176.52
  4271.7  175.78    4356  171.01    4433  168.16  4459.8  166.23    4532  164.33
  4573.3  161.99  4604.3   162.4  4651.9  159.63  4738.4  155.06  4828.3     152
  4831.1   151.5  4834.3     152  4877.4  152.77  4969.8  153.35  5006.7  152.84
    5036  155.66  5163.8  163.11  5199.5  164.61  5323.9  166.43  5367.3  167.61
  5373.2  168.44  5505.6  170.38  5569.8  173.05  5643.8  174.71  5801.1  175.34
#Mann= 7 ,-1 , 0
  3991.4      .1       0  4651.9     .12       0  4828.3     .07       0
  4834.3     .12       0  4877.4      .1       0  4969.8     .12       0
  5163.8      .1       0
Bank Sta=4738.4,5036
XS Rating Curve= 0 ,0
Exp/Cntr=0.3,0.1

Type RM Length L Ch R = 1 ,23134   ,739,739,739
BEGIN DESCRIPTION:
VATOSS GULLY 24.0
END DESCRIPTION:
XS GIS Cut Line= 4
      2265908.68     13323967.77      2265793.77     13324328.89
      2265465.47     13324854.18      2265072.11     13325564.42
#Sta/Elev= 30
  4313.6  176.29  4400.5  175.27  4427.5  174.09  4432.8   174.7  4518.4  171.41
  4681.8  162.03  4794.9  153.43  4832.1   149.9  4855.3  151.53  4875.1  149.89
  4877.8  149.39  4881.1  149.89    4884  151.29  4890.6  151.64    4985  151.66
  4999.6  150.24  5030.2   152.2  5102.9  152.12  5232.6  157.12  5503.6   159.3
  5725.7  166.51  5731.4  165.76    5738  167.11  5769.2   167.2  5790.9  168.67
  5818.4  168.72  5899.7  171.68  5966.7  172.28  6024.5  174.44  6123.9  175.21
#Mann= 6 ,-1 , 0
  4313.6      .1       0  4518.4     .16       0  4681.8     .12       0
  4794.9      .1       0  4875.1     .07       0  4881.1      .1       0
Bank Sta=4985,5030.2
XS Rating Curve= 0 ,0
Exp/Cntr=0.3,0.1

Type RM Length L Ch R = 1 ,22395   ,622,622,622
BEGIN DESCRIPTION:
VATOSS GULLY 23.0
END DESCRIPTION:
XS GIS Cut Line= 2
      2265257.54     13323830.99      2264781.51     13325401.32
#Sta/Elev= 30
  4496.7  181.03  4543.6  178.65  4548.8  177.49  4565.5  179.11  4690.9  172.02
  4793.4   167.8  4816.3  167.82  4827.8  166.59  4888.4  164.19  4941.7  160.09
  4959.4  157.84  4964.6  156.43  4973.1   152.2  4992.3  149.19  4997.5  149.83
  5001.4  147.21  5004.1  146.71  5007.4  147.21  5014.8  149.21  5025.2  150.17
  5030.4  149.34  5035.7  150.13  5119.3   149.1  5238.4   150.3  5271.3  149.23
  5322.1  149.37  5517.3  153.13  5777.7  163.93  5998.9  170.84  6137.6  172.66
#Mann= 5 ,-1 , 0
  4496.7      .1       0  4793.4     .12       0  5001.4     .07       0
  5007.4     .12       0  5322.1      .1       0
Bank Sta=4997.5,5025.2
XS Rating Curve= 0 ,0
Exp/Cntr=0.3,0.1

Type RM Length L Ch R = 1 ,21773   ,592,592,592
BEGIN DESCRIPTION:
VATOSS GULLY 22.0
END DESCRIPTION:
XS GIS Cut Line= 4
      2264994.88     13323590.24      2264748.68     13323880.21
      2264393.01     13324662.67      2264409.38     13325022.81
#Sta/Elev= 30
  4152.1   176.5    4190  174.45    4212  174.35  4218.5  173.41  4304.2  171.71
  4310.8  170.53  4339.4  169.69  4345.9  168.31  4360.2  167.42  4516.2   158.8
  4631.9  154.04  4726.5  150.79  4787.7  150.33  4847.4  151.34  4891.3   148.9
  4977.8  148.35  4997.8  147.27  5000.6  146.77  5003.8  147.27  5006.3  148.36
  5029.4  148.63  5045.1  147.74    5058  148.16  5098.6  151.66  5127.2  155.28
  5178.5  158.74  5308.7  163.42  5416.2  165.05  5544.2  168.36  5752.5  172.62
#Mann= 6 ,-1 , 0
  4152.1      .1       0  4631.9     .12       0  4997.8     .07       0
  5003.8     .12       0  5178.5      .1       0  5544.2     .05       0
Bank Sta=4977.8,5029.4
XS Rating Curve= 0 ,0
Exp/Cntr=0.3,0.1

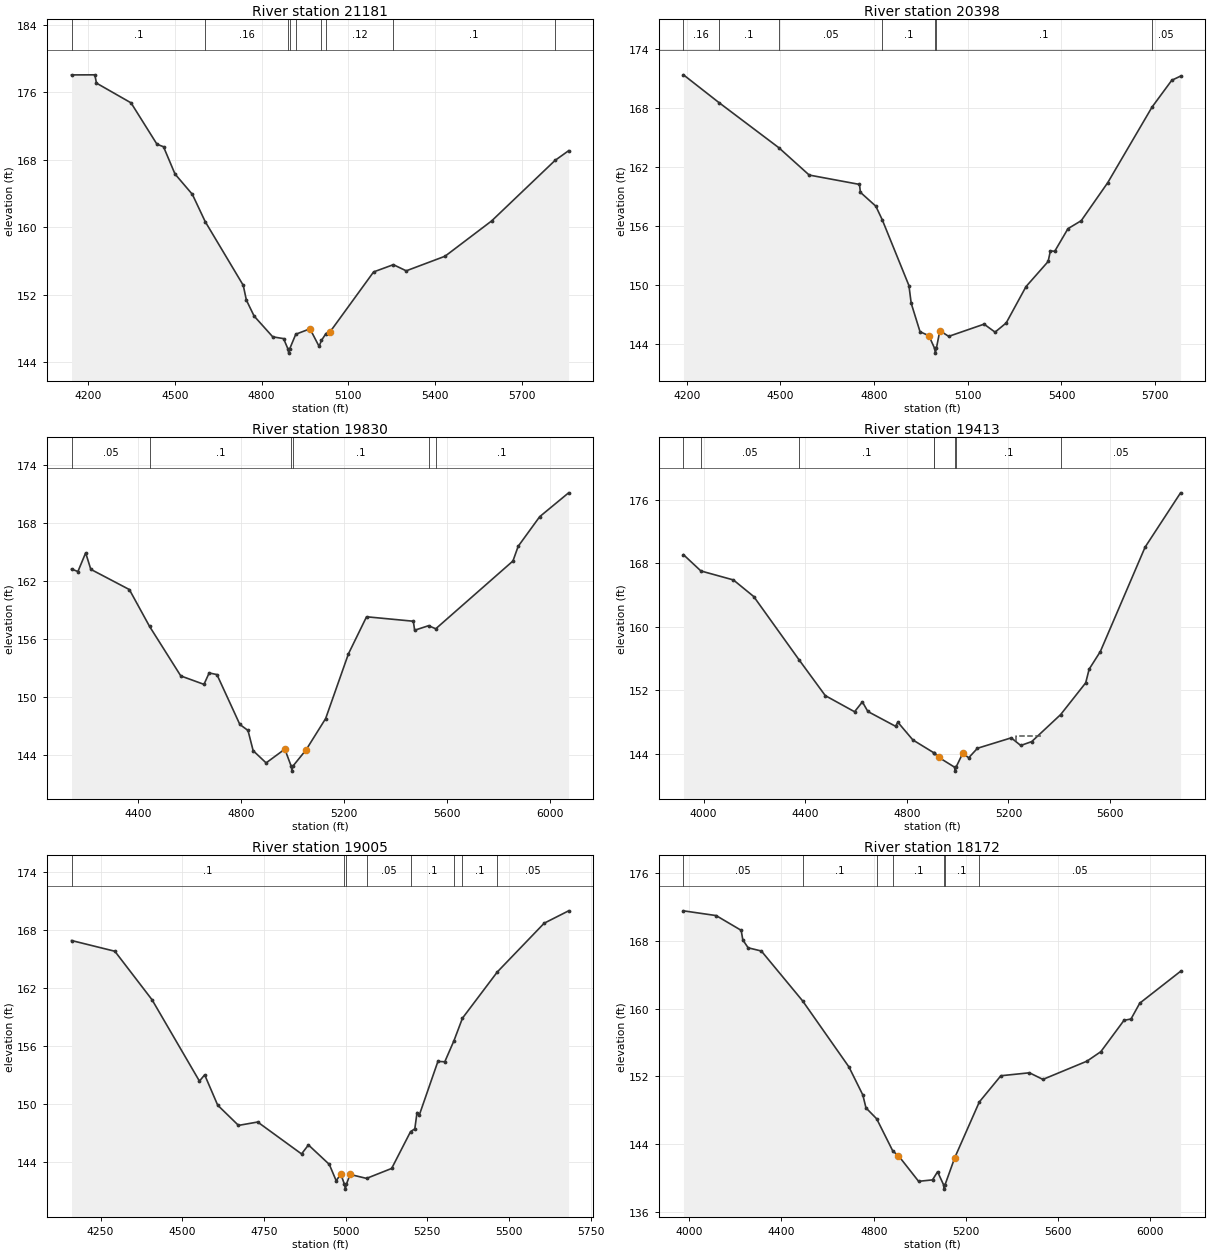
Type RM Length L Ch R = 1 ,21181   ,783,783,783
BEGIN DESCRIPTION:
VATOSS GULLY 21.0
END DESCRIPTION:
XS GIS Cut Line= 3
      2264108.49     13323250.95      2263927.92     13323628.51
      2264321.89     13324870.61
#Sta/Elev= 30
  4141.5  178.07  4222.3  178.08  4227.8   177.1  4347.6  174.76  4437.4  169.86
  4460.1  169.56  4499.9  166.33    4560  163.92  4604.5  160.69  4736.3  153.14
  4747.1  151.39  4773.9   149.5  4838.4  147.04  4875.9  146.83    4891  145.61
  4893.7  145.11    4897  145.61  4918.2  147.35  4967.4  147.99  4998.9  145.91
    5007  146.61  5022.7  147.43  5037.3  147.65  5187.7  154.73  5256.2  155.59
  5300.7  154.86  5435.1  156.59  5596.4  160.77    5816  167.94  5863.1  169.09
#Mann= 9 ,-1 , 0
  4141.5      .1       0  4604.5     .16       0    4891     .07       0
    4897     .16       0  4918.2     .12       0    5007      .1       0
  5022.7     .12       0  5256.2      .1       0    5816     .05       0
Bank Sta=4967.4,5037.3
XS Rating Curve= 0 ,0
Exp/Cntr=0.3,0.1

Type RM Length L Ch R = 1 ,20398   ,568,568,568
BEGIN DESCRIPTION:
VATOSS GULLY 20.0
END DESCRIPTION:
XS GIS Cut Line= 3
      2263386.22     13323754.36      2263402.63     13324317.95
      2264151.26     13325022.86
#Sta/Elev= 30
  4189.3  171.35  4302.7  168.54  4494.5  163.96    4592  161.18  4753.1  160.23
    4756  159.43  4805.4  158.02    4826  156.64  4911.4  149.97  4918.7  148.17
    4947  145.28  4975.3  144.88  4993.4  143.61  4996.1  143.11  4999.4  143.61
  5010.5  145.39  5038.8  144.81  5152.1  146.05  5187.3  145.24  5222.9  146.17
  5286.4  149.86  5357.3  152.41  5364.5  153.49  5378.3  153.44  5420.8  155.74
  5463.3  156.55  5548.2  160.41  5690.1  168.08  5753.3   170.8  5781.4  171.22
#Mann= 7 ,-1 , 0
  4189.3     .16       0  4302.7      .1       0  4494.5     .05       0
    4826      .1       0  4993.4     .07       0  4999.4      .1       0
  5690.1     .05       0
Bank Sta=4975.3,5010.5
XS Rating Curve= 0 ,0
Exp/Cntr=0.3,0.1

Type RM Length L Ch R = 1 ,19830   ,417,417,417
BEGIN DESCRIPTION:
Mapping XS da1617cf
END DESCRIPTION:
XS GIS Cut Line= 4
      2263353.39     13324131.88      2263342.44     13324618.89
      2263421.07      13325277.8      2264190.54     13325423.23
#Sta/Elev= 30
  4139.5  163.22  4164.4  162.96  4194.5  164.89  4214.5  163.19  4364.5   161.1
    4443   157.3  4564.6  152.18  4654.8  151.31  4674.9  152.49  4705.2  152.32
  4794.3  147.17    4826  146.55  4846.1  144.46  4896.5   143.2  4969.3  144.62
  4994.2  142.85    4997  142.35  5000.2  142.85  5051.8  144.54  5128.1  147.78
  5216.7  154.46  5287.2  158.29  5469.2  157.83  5474.3   156.9  5528.6  157.37
  5556.4  157.05  5856.7  164.05  5877.1  165.57  5960.9  168.63  6073.3  171.09
#Mann= 6 ,-1 , 0
  4139.5     .05       0    4443      .1       0  4994.2     .07       0
  5000.2      .1       0  5528.6     .16       0  5556.4      .1       0
Bank Sta=4969.3,5051.8
XS Rating Curve= 0 ,0
Exp/Cntr=0.3,0.1

Type RM Length L Ch R = 1 ,19413   ,408,408,408
BEGIN DESCRIPTION:
VATOSS GULLY 19.0
END DESCRIPTION:
XS GIS Cut Line= 3
      2263298.67     13324000.58      2263271.31     13324547.76
      2262572.29     13325771.06
#Sta/Elev= 30
  3920.8  169.09  3989.4  167.04  4117.3  165.91  4197.4  163.82  4375.6  155.86
  4479.1  151.34  4594.3  149.31  4625.1  150.55  4646.7  149.34  4755.6  147.48
  4764.7  147.99  4823.8  145.76  4905.4  144.16  4907.5  144.12    4926  143.56
  4987.8  142.33  4990.5  141.83  4993.8  142.33  5020.5   144.1  5043.5  143.51
  5078.1  144.71    5211  146.02  5248.5  145.06  5291.7  145.55  5405.5  148.95
  5504.2  152.95  5517.7  154.67  5561.8  156.89    5738  170.04  5877.6  176.88
#Mann= 8 ,-1 , 0
  3920.8      .1       0  3989.4     .05       0  4375.6      .1       0
  4905.4     .05       0  4907.5      .1       0  4987.8     .07       0
  4993.8      .1       0  5405.5     .05       0
#XS Ineff= 1 ,-1
 5228.52 5337.89  146.27
Permanent Ineff=
       F
Bank Sta=4926,5020.5
XS Rating Curve= 0 ,0
Exp/Cntr=0.3,0.1

Type RM Length L Ch R = 1 ,19005   ,833,833,833
BEGIN DESCRIPTION:
VATOSS GULLY 18.0
END DESCRIPTION:
XS GIS Cut Line= 3
      2263068.87     13324038.86      2262935.79     13324532.77
      2262238.43     13325263.22
#Sta/Elev= 30
  4161.1  166.93  4293.7  165.82  4407.6   160.8  4552.6  152.39  4568.6  153.04
  4608.5   149.9  4672.1  147.81  4730.8  148.16  4865.1  144.86  4886.2  145.79
    4950  143.78  4971.1  142.09  4985.3  142.77  4996.4  141.72  4999.2  141.22
  5002.4  141.72  5013.6  142.74    5064  142.33  5140.9  143.36  5198.8  147.17
  5211.7  147.45  5218.6  149.14  5225.9  148.92  5282.5  154.43  5303.5  154.39
  5331.6  156.57  5357.6   158.9  5464.3  163.68  5607.7  168.72  5682.5     170
#Mann= 8 ,-1 , 0
  4161.1      .1       0  4996.4     .07       0  5002.4      .1       0
    5064     .05       0  5198.8      .1       0  5331.6     .05       0
  5357.6      .1       0  5464.3     .05       0
Bank Sta=4985.3,5013.6
XS Rating Curve= 0 ,0
Exp/Cntr=0.3,0.1

Type RM Length L Ch R = 1 ,18172   ,843,843,843
BEGIN DESCRIPTION:
VATOSS GULLY 17.0
END DESCRIPTION:
XS GIS Cut Line= 4
      2263293.19      13323535.5       2262866.4     13323814.55
      2261990.93     13324279.65      2261925.27     13324930.78
#Sta/Elev= 30
    3975  171.52  4116.7  170.96  4225.3  169.22  4232.4  168.09  4255.5  167.16
  4312.8  166.78  4491.7   160.9  4692.6  153.11  4752.9   149.8  4766.5  148.28
    4813  146.99  4883.3  143.17  4906.8  142.66  4994.7  139.62    5055  139.79
    5077  140.75  5103.2   139.2    5106   138.7  5109.2   139.2  5151.5  142.41
    5258  148.98  5351.4  152.07  5475.3  152.42  5533.8  151.64  5724.7  153.79
    5785  154.91  5885.5  158.61  5915.7  158.76  5953.8  160.63  6130.7  164.39
#Mann= 7 ,-1 , 0
    3975     .05       0  4491.7      .1       0    4813     .05       0
  4883.3      .1       0  5103.2     .07       0  5109.2      .1       0
    5258     .05       0
Bank Sta=4906.8,5151.5
XS Rating Curve= 0 ,0
Exp/Cntr=0.3,0.1

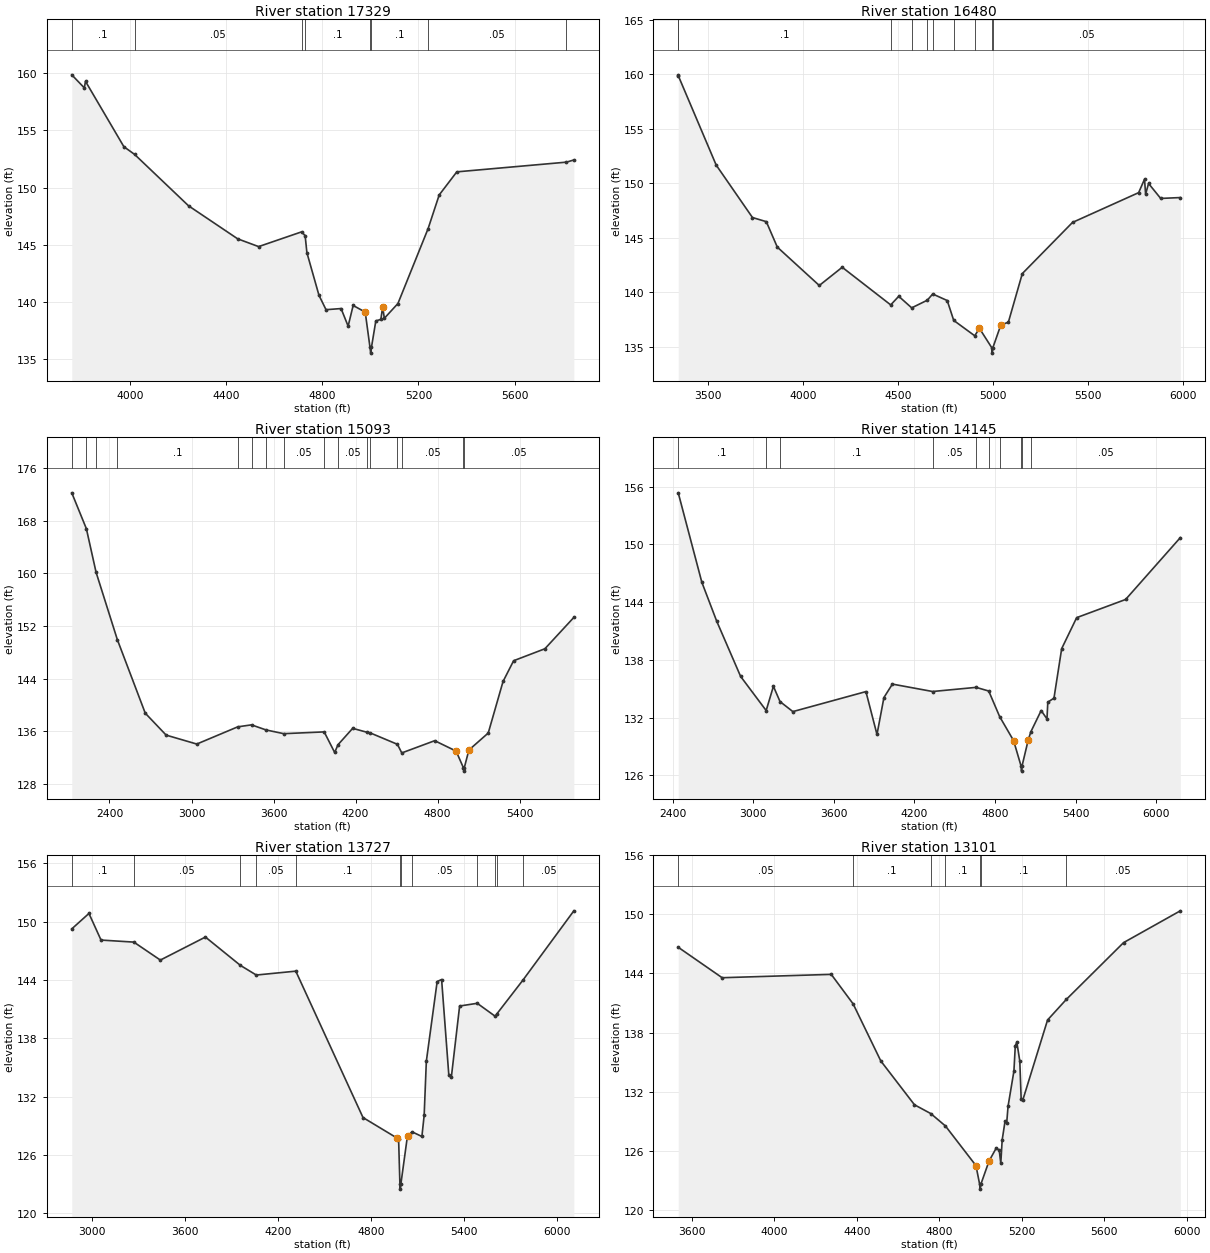
Type RM Length L Ch R = 1 ,17329   ,849,849,849
BEGIN DESCRIPTION:
VATOSS GULLY 16.0
END DESCRIPTION:
XS GIS Cut Line= 3
      2263232.99     13323015.68      2262477.91     13323103.23
      2261405.45     13323885.69
#Sta/Elev= 30
  3758.7  159.87  3810.8  158.73  3815.8   159.3  3975.4  153.58  4019.8  152.91
  4244.3  148.41  4448.6  145.52  4535.6  144.84  4714.3  146.13  4729.1   145.8
  4736.4  144.31  4786.6  140.58  4815.9  139.32  4878.5  139.42  4907.9  137.88
  4928.7  139.69  4978.9  139.11  4998.8  136.02  5001.6  135.52  5004.8  136.02
    5023  138.34  5043.8  138.47  5051.4  139.54  5058.5  138.57  5114.9  139.86
  5240.5  146.42  5286.5  149.36  5359.7  151.38  5815.7  152.23  5846.4  152.42
#Mann= 8 ,-1 , 0
  3758.7      .1       0  4019.8     .05       0  4714.3     .08       0
  4729.1      .1       0  4998.8     .07       0  5004.8      .1       0
  5240.5     .05       0  5815.7     .08       0
Bank Sta=4978.9,5051.4
XS Rating Curve= 0 ,0
Exp/Cntr=0.3,0.1

Type RM Length L Ch R = 1 ,16480   ,1387,1387,1387
BEGIN DESCRIPTION:
VATOSS GULLY 15.0
END DESCRIPTION:
XS GIS Cut Line= 4
      2263446.39     13322402.84       2262461.5     13322293.41
      2261624.32     13322698.32      2261246.76     13323316.65
#Sta/Elev= 30
  3342.2  159.93  3343.4  159.81  3542.1  151.66  3733.3  146.85  3806.3  146.47
  3864.1  144.14  4085.4  140.62  4206.2  142.29  4461.7  138.84    4504  139.63
  4572.3  138.57  4654.4  139.27    4683  139.84  4759.5  139.24  4793.7  137.42
  4904.4  136.01  4929.2  136.69    4994  134.92  4996.7  134.42    5000  134.92
  5042.1  137.01  5081.6  137.25  5155.1  141.71  5419.6   146.4  5768.1  149.13
    5799  150.36  5804.8  148.99  5820.3  149.97  5884.2   148.6  5987.6  148.68
#Mann= 10 ,-1 , 0
  3342.2     .05       0  3343.4      .1       0  4461.7     .08       0
  4572.3     .05       0  4654.4      .1       0    4683     .05       0
  4793.7     .08       0  4904.4     .05       0    4994     .03       0
    5000     .05       0
Bank Sta=4929.2,5042.1
XS Rating Curve= 0 ,0
Exp/Cntr=0.3,0.1

Type RM Length L Ch R = 1 ,15093   ,948,948,948
BEGIN DESCRIPTION:
VATOSS GULLY 14.0
END DESCRIPTION:
XS GIS Cut Line= 3
      2263665.32     13321122.46      2261421.87     13321554.73
      2260316.63     13322391.87
#Sta/Elev= 30
  2124.5  172.27  2231.3  166.81  2302.2  160.18  2457.7  149.93  2661.8  138.74
  2814.6   135.4  3038.6  134.04  3338.1  136.66  3438.7  136.96  3544.6  136.19
  3674.4  135.62  3970.2  135.89  4046.8  132.76  4071.3  133.94  4178.4  136.43
  4280.4  135.85  4305.2  135.75  4505.7     134  4537.5  132.69  4778.2  134.55
  4934.7  132.97  4988.5  130.42  4991.2  129.92  4994.5  130.42  5028.3  133.13
  5169.8  135.72    5278  143.56  5355.3  146.72  5583.9  148.54  5795.7  153.31
#Mann= 16 ,-1 , 0
  2124.5     .05       0  2231.3      .1       0  2302.2     .05       0
  2457.7      .1       0  3338.1     .08       0  3438.7     .05       0
  3544.6      .1       0  3674.4     .05       0  3970.2      .1       0
  4071.3     .05       0  4280.4      .1       0  4305.2     .05       0
  4505.7      .1       0  4537.5     .05       0  4988.5    .035       0
  4994.5     .05       0
Bank Sta=4934.7,5028.3
XS Rating Curve= 0 ,0
Exp/Cntr=0.3,0.1

Type RM Length L Ch R = 1 ,14145   ,418,418,418
BEGIN DESCRIPTION:
VATOSS GULLY 13.0
END DESCRIPTION:
XS GIS Cut Line= 4
      2263227.51     13320241.53      2261235.72     13320823.14
      2260453.38     13321264.73      2260064.87     13321921.37
#Sta/Elev= 30
  2442.2  155.37  2617.8  146.07  2728.6  142.02  2906.4  136.28  3096.6  132.73
  3150.4  135.25  3199.8  133.66  3295.3  132.62  3838.9   134.7  3921.3  130.24
  3972.8  134.08  4035.9  135.48  4335.1  134.71  4658.9  135.14  4752.8  134.76
  4834.1   132.1  4937.9   129.6  4994.1  126.93  4996.9  126.43  5000.1  126.93
  5046.2  129.64  5066.2  130.52    5143  132.73  5186.3  131.86  5192.4   133.6
  5238.3  134.02  5295.7  139.17  5407.2  142.39  5771.4  144.28  6178.5  150.71
#Mann= 10 ,-1 , 0
  2442.2      .1       0  3096.6     .08       0  3199.8      .1       0
  4335.1     .05       0  4658.9      .1       0  4752.8     .05       0
  4834.1      .1       0  4994.1     .07       0  5000.1      .1       0
  5066.2     .05       0
Bank Sta=4937.9,5046.2
XS Rating Curve= 0 ,0
Exp/Cntr=0.3,0.1

Type RM Length L Ch R = 1 ,13727   ,626,626,626
BEGIN DESCRIPTION:
VATOSS GULLY 12.0
END DESCRIPTION:
XS GIS Cut Line= 4
      2261739.24     13319152.64       2260751.8     13320282.77
      2260311.11      13321270.2      2259912.17     13321789.37
#Sta/Elev= 30
    2870  149.26  2980.7  150.85  3058.6  148.11  3270.2   147.9  3441.1  146.05
  3731.6  148.42  3957.4   145.5  4059.6  144.51  4314.2  144.91  4747.5  129.84
  4966.6  127.73    4977  127.66  4985.5  122.97  4988.2  122.47  4991.5  122.97
  5034.4  127.98  5064.9  128.36  5127.2  127.89  5141.8  130.06  5155.9  135.64
  5225.6  143.84  5254.3  144.05  5300.7  134.23    5317  133.99  5370.4  141.32
    5484   141.6  5600.2  140.26  5612.4  140.55  5780.1  144.02  6106.8  151.12
#Mann= 12 ,-1 , 0
    2870      .1       0  3270.2     .05       0  3957.4     .16       0
  4059.6     .05       0  4314.2      .1       0  4985.5     .07       0
  4991.5      .1       0  5064.9     .05       0    5484      .1       0
  5600.2     .05       0  5612.4      .1       0  5780.1     .05       0
Bank Sta=4966.6,5034.4
XS Rating Curve= 0 ,0
Exp/Cntr=0.3,0.1

Type RM Length L Ch R = 1 ,13101   ,594,594,594
BEGIN DESCRIPTION:
VATOSS GULLY 11.0
END DESCRIPTION:
XS GIS Cut Line= 3
      2261139.51      13319521.5      2260497.15     13320006.23
       2259419.2     13321226.46
#Sta/Elev= 30
  3535.1  146.66  3747.8  143.57  4276.5  143.91  4382.7  140.91  4516.7  135.12
  4679.9  130.67  4758.8  129.78  4829.9  128.52  4977.7   124.5  4995.6  122.61
  4998.3  122.11  5001.6  122.61  5041.2  124.96  5076.4  126.29  5090.6  126.05
  5098.1  124.73  5104.8   127.1    5119  129.04  5126.6  128.79  5133.3  130.52
  5161.7  134.09  5168.4  136.67  5175.9  137.02  5190.2  135.11  5196.8  131.27
  5204.4  131.13  5324.8  139.28  5415.3  141.36  5692.9  147.13    5968  150.36
#Mann= 7 ,-1 , 0
  3535.1     .05       0  4382.7      .1       0  4758.8     .05       0
  4829.9      .1       0  4995.6     .07       0  5001.6      .1       0
  5415.3     .05       0
Bank Sta=4977.7,5041.2
XS Rating Curve= 0 ,0
Exp/Cntr=0.3,0.1