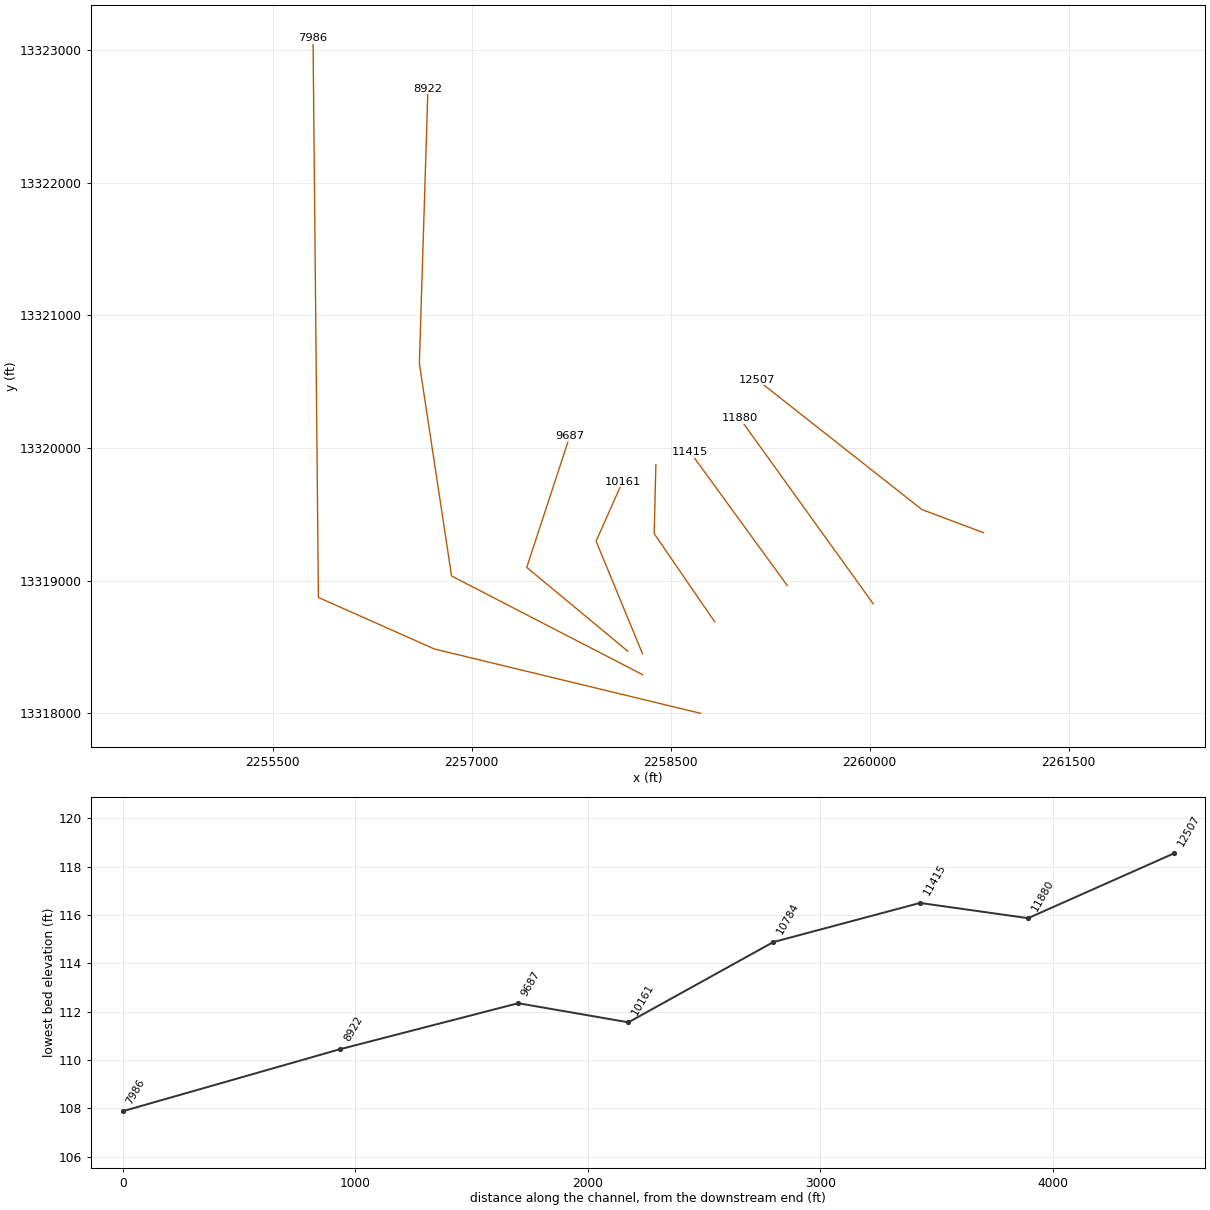
HEC-RAS study VATOSS GULLY.prj: VATOSS GULLY Base Level Engineering

--- VATOSS GULLY.g01 (geometry) --- (continued)

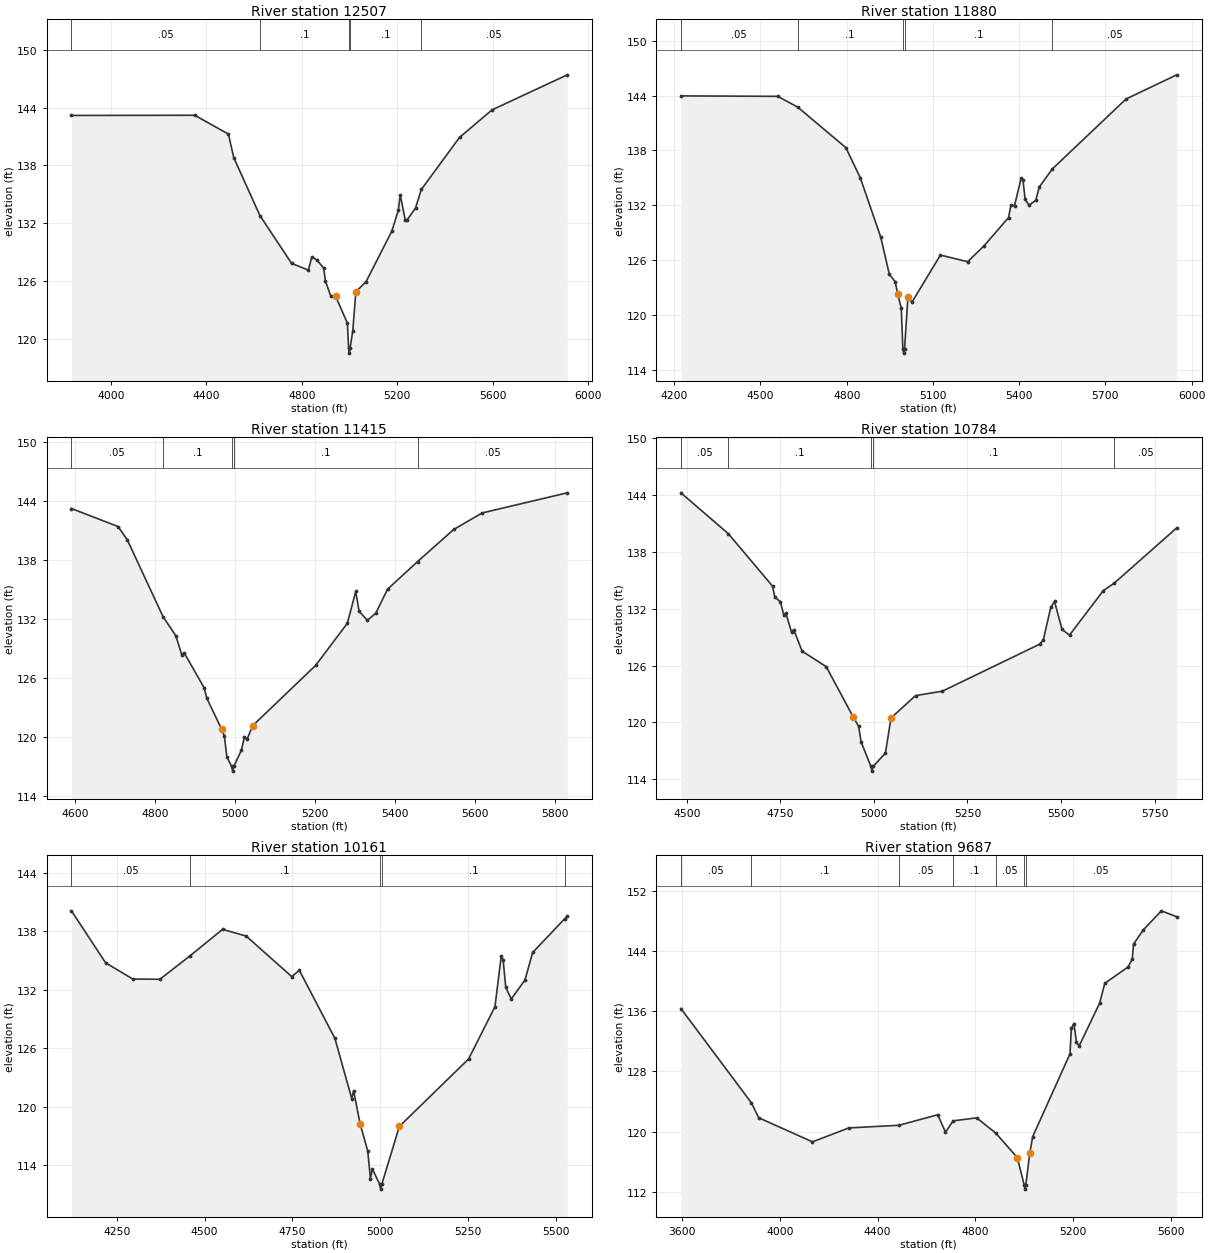
Type RM Length L Ch R = 1 ,12507   ,627,627,627
BEGIN DESCRIPTION:
VATOSS GULLY 10.0
END DESCRIPTION:
XS GIS Cut Line= 3
      2260858.27     13319360.58      2260393.19     13319535.67
      2259151.92     13320514.46
#Sta/Elev= 30
  3834.8  143.18  4351.4   143.2  4492.5  141.25    4515  138.81  4624.4  132.81
  4757.1  127.86  4827.6  127.15  4842.1  128.54  4862.9  128.21  4891.8  127.37
    4899  126.03  4920.6  124.52  4941.5  124.45  4991.1  121.66  4996.2  119.05
    4999  118.55  5002.2  119.05  5013.7  120.85  5026.4   124.9  5069.7  125.97
  5177.2  131.19  5204.7  133.37  5212.4  134.94  5233.3  132.39  5241.3  132.35
  5276.6  133.59  5300.9  135.51  5460.9   140.9  5597.3  143.76  5912.5  147.39
#Mann= 5 ,-1 , 0
  3834.8     .05       0  4624.4      .1       0  4996.2     .07       0
  5002.2      .1       0  5300.9     .05       0
Bank Sta=4941.5,5026.4
XS Rating Curve= 0 ,0
Exp/Cntr=0.3,0.1

Type RM Length L Ch R = 1 ,11880   ,465,465,465
BEGIN DESCRIPTION:
VATOSS GULLY 9.0
END DESCRIPTION:
XS GIS Cut Line= 2
      2260026.59     13318824.34      2259019.82     13320225.06
#Sta/Elev= 30
  4223.1  143.96  4560.1  143.91  4629.2  142.74    4797  138.31  4847.3  135.01
  4918.5  128.52    4948  124.51  4968.9  123.65  4977.4  122.31  4989.8  120.77
  4995.3  116.37  4998.1  115.87  5001.3  116.37    5013  122.01  5026.7  121.42
    5126  126.58  5220.5  125.85    5277  127.56    5363  130.67  5371.5  132.06
  5383.8  131.98  5407.1  135.01  5413.3  134.74  5420.8  132.67  5434.2  132.02
  5457.5  132.54    5470  134.01  5514.9  135.97  5771.8  143.62  5948.1  146.26
#Mann= 5 ,-1 , 0
  4223.1     .05       0  4629.2      .1       0  4995.3     .07       0
  5001.3      .1       0  5514.9     .05       0
Bank Sta=4977.4,5013
XS Rating Curve= 0 ,0
Exp/Cntr=0.3,0.1

Type RM Length L Ch R = 1 ,11415   ,631,631,631
BEGIN DESCRIPTION:
VATOSS GULLY 8.0
END DESCRIPTION:
XS GIS Cut Line= 2
      2259377.99     13318963.15      2258648.78     13319965.82
#Sta/Elev= 30
  4591.6  143.23  4708.1   141.4  4731.3  140.04  4820.8  132.21  4852.6  130.28
  4867.3  128.36  4873.5  128.54  4923.7  124.96    4930  123.92  4967.1  120.77
    4974  120.06  4980.1  117.96  4991.8     117  4994.6   116.5  4997.8     117
  5016.6  118.64  5024.2     120  5030.4  119.73  5045.1  121.14  5202.1  127.26
  5281.5  131.55  5302.4  134.79  5310.9  132.76  5331.8  131.85  5352.6  132.58
    5382  135.02    5457  137.83  5547.4   141.1  5618.5  142.78  5831.4  144.83
#Mann= 5 ,-1 , 0
  4591.6     .05       0  4820.8      .1       0  4991.8     .07       0
  4997.8      .1       0    5457     .05       0
Bank Sta=4967.1,5045.1
XS Rating Curve= 0 ,0
Exp/Cntr=0.3,0.1

Type RM Length L Ch R = 1 ,10784   ,623,623,623
BEGIN DESCRIPTION:
VATOSS GULLY 7.0
END DESCRIPTION:
XS GIS Cut Line= 3
      2258831.08     13318689.77      2258375.37     13319353.81
      2258388.35     13319873.28
#Sta/Elev= 30
  4484.3  144.18    4611  139.88  4729.1  134.36  4735.5  133.18  4750.1  132.73
  4758.9  131.36    4765   131.5  4779.9  129.51  4785.9  129.77  4808.2  127.51
  4872.6  125.88  4944.3  120.62  4959.2   119.6  4965.9  117.96  4992.1  115.38
  4994.8  114.88  4998.1  115.38  5030.9  116.78  5045.8  120.48  5111.4  122.83
  5183.2   123.3  5442.8  128.24  5452.8   128.7  5472.8  132.13  5482.8  132.74
  5502.8   129.8  5522.8   129.2  5612.8  133.87  5642.6  134.68  5809.3  140.49
#Mann= 5 ,-1 , 0
  4484.3     .05       0    4611      .1       0  4992.1     .07       0
  4998.1      .1       0  5642.6     .05       0
Bank Sta=4944.3,5045.8
XS Rating Curve= 0 ,0
Exp/Cntr=0.3,0.1

Type RM Length L Ch R = 1 ,10161   ,474,474,474
BEGIN DESCRIPTION:
VATOSS GULLY 6.0
END DESCRIPTION:
XS GIS Cut Line= 3
      2258287.72     13318446.85      2257937.72     13319296.85
      2258137.73     13319746.87
#Sta/Elev= 30
  4120.7  140.09    4218  134.76  4295.3   133.1  4372.5  133.07  4458.3  135.48
    4551  138.19  4618.2   137.5  4747.9  133.35  4769.6  133.99  4870.8  127.01
  4918.7  120.85  4924.1  121.64  4942.6  118.25  4964.2  115.48    4972  112.62
  4977.4  113.63  4998.3  112.06  5001.1  111.56  5004.3  112.06  5054.3  117.99
  5251.3   124.9  5326.5  130.26  5344.3  135.43  5349.8  135.05  5357.3  132.23
    5373  131.06    5412     133  5433.9  135.82  5525.1  139.28  5532.4  139.52
#Mann= 5 ,-1 , 0
  4120.7     .05       0  4458.3      .1       0  4998.3     .07       0
  5004.3      .1       0  5525.1     .05       0
Bank Sta=4942.6,5054.3
XS Rating Curve= 0 ,0
Exp/Cntr=0.3,0.1

Type RM Length L Ch R = 1 ,9687    ,765,765,765
BEGIN DESCRIPTION:
Mapping XS 376fc939
END DESCRIPTION:
XS GIS Cut Line= 3
      2258175.95     13318467.35      2257414.98      13319098.8
      2257738.79     13320086.43
#Sta/Elev= 30
  3595.6  136.34  3884.3   123.8  3913.8  121.83  4133.8  118.63  4282.3  120.48
  4487.5  120.83  4646.1  122.23  4677.9  119.92  4709.2  121.42  4805.3  121.82
  4884.1  119.78  4971.8  116.54  5000.3  112.85  5003.1  112.35  5006.3  112.85
  5022.8  117.17  5034.9  119.34  5187.3  130.33  5192.8  133.73  5203.3  134.34
  5213.8  131.87  5224.4  131.35  5308.5  137.06  5329.6  139.69  5424.3  141.85
    5442  142.89  5447.2  144.91  5487.4   146.8  5561.1  149.32  5623.8  148.53
#Mann= 7 ,-1 , 0
  3595.6     .05       0  3884.3      .1       0  4487.5     .05       0
  4709.2      .1       0  4884.1     .05       0  5000.3     .03       0
  5006.3     .05       0
Bank Sta=4971.8,5022.8
XS Rating Curve= 0 ,0
Exp/Cntr=0.3,0.1

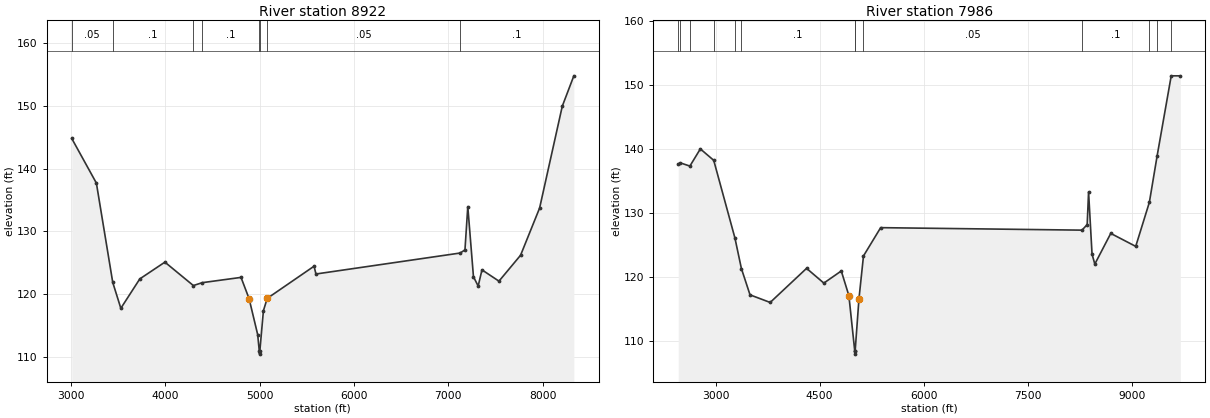
Type RM Length L Ch R = 1 ,8922    ,936,936,936
BEGIN DESCRIPTION:
VATOSS GULLY 5.0
END DESCRIPTION:
XS GIS Cut Line= 4
      2258289.23     13318289.29      2256848.31     13319034.04
      2256605.45     13320636.89      2256670.22     13322709.32
#Sta/Elev= 30
    3012  144.79  3272.6  137.69  3445.9  121.87  3531.5  117.75  3732.4  122.43
  3998.2   125.1  4299.6  121.37  4393.7  121.83  4804.3  122.67  4889.7  119.28
  4980.7  113.56  4997.5  110.95  5000.3  110.45  5003.5  110.95  5041.4  117.37
  5079.1   119.2  5081.9  119.33  5577.5  124.45  5597.7  123.21  7124.6  126.55
  7175.6  127.05  7205.6  133.94  7265.6  122.77  7315.6  121.29  7355.7  123.87
  7535.7  122.07  7764.6   126.2    7966  133.71  8206.1  149.93  8328.6  154.77
#Mann= 8 ,-1 , 0
    3012     .05       0  3445.9      .1       0  4299.6     .05       0
  4393.7      .1       0  4997.5     .07       0  5003.5      .1       0
  5079.1     .05       0  7124.6      .1       0
Bank Sta=4889.7,5081.9
XS Rating Curve= 0 ,0
Exp/Cntr=0.3,0.1

Type RM Length L Ch R = 1 ,7986    ,0,0,0
BEGIN DESCRIPTION:
VATOSS GULLY 1.0
END DESCRIPTION:
XS GIS Cut Line= 4
      2258726.42     13317997.84      2256718.79     13318483.56
       2255844.5     13318872.13      2255804.03     13323089.74
#Sta/Elev= 30
  2460.8  137.61  2488.7  137.83  2628.9  137.32  2779.5  140.01  2972.6  138.22
  3277.8  126.08  3371.6  121.28    3496  117.16  3786.7  115.97  4311.5  121.31
  4560.4     119    4812   120.9  4921.5  117.04    5006  108.38  5008.8  107.88
    5012  108.38  5066.5  116.49  5132.1  123.25  5379.8  127.68    8283  127.29
    8358  128.16    8378  133.27    8428  123.54    8468  121.98    8698  126.78
    9058  124.75  9254.7  131.65  9366.8  138.93  9569.8  151.45  9700.9  151.45
#Mann= 13 ,-1 , 0
  2460.8     .05       0  2488.7      .1       0  2628.9     .05       0
  2972.6      .1       0  3277.8     .05       0  3371.6      .1       0
    5006     .07       0    5012      .1       0  5132.1     .05       0
    8283      .1       0  9254.7     .05       0  9366.8      .1       0
  9569.8     .05       0
Bank Sta=4921.5,5066.5
XS Rating Curve= 0 ,0
Exp/Cntr=0.3,0.1

Chan Stop Cuts=-1
Use User Specified Reach Order=0
Composite Channel Slope=5