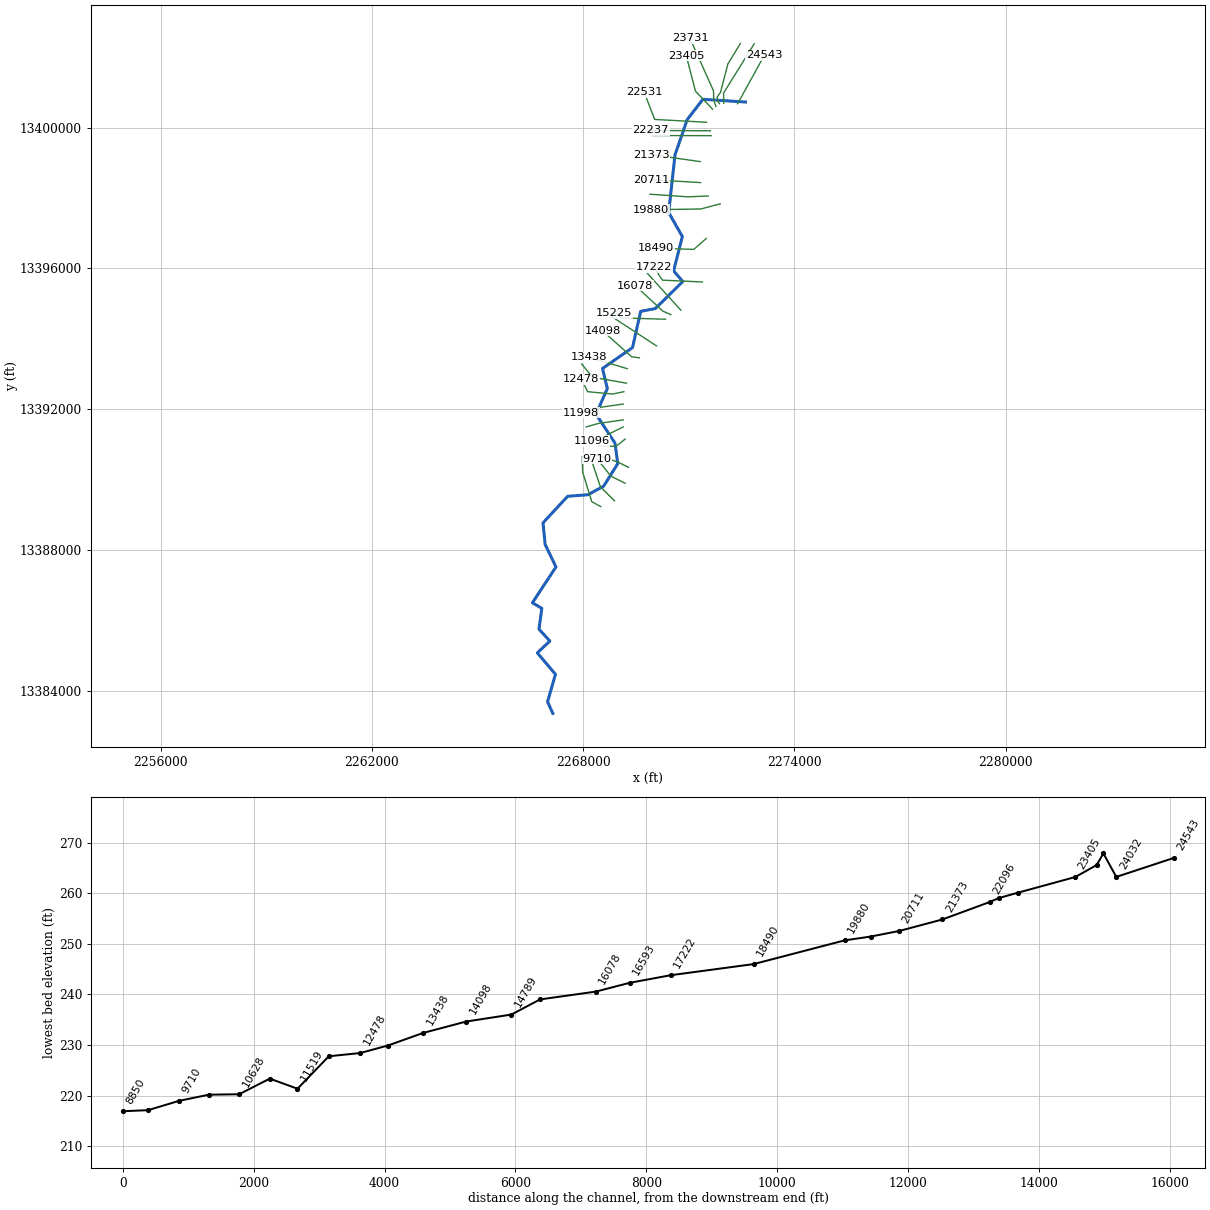
--- BEST BRANCH.prj (project) ---

Proj Title=BEST BRANCH Base Level Engineering
Current Plan=p01
Default Exp/Contr=0.3,0.1
English Units
Geom File=g01
Flow File=f01
Plan File=p01
Y Axis Title=Elevation
X Axis Title(PF)=Main Channel Distance
X Axis Title(XS)=Station
BEGIN DESCRIPTION:
BEST BRANCH
END DESCRIPTION:
DSS Export Rating Curves= 0
DSS Export Rating Curve Sorted= 0
DSS Export Volume Flow Curves= 0
DXF OffsetX= 0
DXF OffsetY= 0
DXF ScaleX= 1
DXF ScaleY= 10

--- BEST BRANCH.p01 (plan) ---

Plan Title=Multiple Run
Short Identifier=Multiple
Geom File=g01
Flow File=f01
Subcritical Flow
K Sum by GR= 0
Std Step Tol= 0.01
Critical Tol= 0.01
Num of Std Step Trials= 20
Max Error Tol= 0.3
Flow Tol Ratio= 0.001
Split Flow NTrial= 30
Split Flow Tol= 0.02
Split Flow Ratio= 0.02
Log Output Level= 0
Friction Slope Method= 1
Unsteady Friction Slope Method= 2
Unsteady Bridges Friction Slope Method= 1
Parabolic Critical Depth
Global Vel Dist=  1 , 1 , 1
Global Log Level= 0
CheckData=True
Encroach Param= -1, 0, 0, 0
BEGIN DESCRIPTION:
Multiple Run
END DESCRIPTION:

--- BEST BRANCH.f01 (steady flow) ---

Flow Title=Multiple
Program Version=4.10
Number of Profiles= 7
Profile Names=10-year,25-year,50-year,1pct_min,100-year,1pct_plu,500-year
River Rch & RM=BEST BRANCH,Reach-1         ,24543
     184     251     305     273     370     500     550
River Rch & RM=BEST BRANCH,Reach-1         ,24032
     275     383     472     429     580     785     888
River Rch & RM=BEST BRANCH,Reach-1         ,22096
     315     441     546     497     672     909    1034
River Rch & RM=BEST BRANCH,Reach-1         ,17222
     401     568     708     649     877    1187    1368
River Rch & RM=BEST BRANCH,Reach-1         ,13438
     443     628     784     719     973    1316    1521
River Rch & RM=BEST BRANCH,Reach-1         ,7451
     516     735     922     849    1148    1553    1807
Boundary for River Rch & Prof#=BEST BRANCH,Reach-1         , 1
Up Type= 0
Dn Type= 3
Dn Slope=0.005
Boundary for River Rch & Prof#=BEST BRANCH,Reach-1         , 2
Up Type= 0
Dn Type= 3
Dn Slope=0.005
Boundary for River Rch & Prof#=BEST BRANCH,Reach-1         , 3
Up Type= 0
Dn Type= 3
Dn Slope=0.005
Boundary for River Rch & Prof#=BEST BRANCH,Reach-1         , 4
Up Type= 0
Dn Type= 3
Dn Slope=0.005
Boundary for River Rch & Prof#=BEST BRANCH,Reach-1         , 5
Up Type= 0
Dn Type= 3
Dn Slope=0.005
Boundary for River Rch & Prof#=BEST BRANCH,Reach-1         , 6
Up Type= 0
Dn Type= 3
Dn Slope=0.005
Boundary for River Rch & Prof#=BEST BRANCH,Reach-1         , 7
Up Type= 0
Dn Type= 3
Dn Slope=0.005
DSS Import GetInterval= 0
DSS Import GetPeak= 0
DSS Import FillOption= 0

--- BEST BRANCH.g01 (geometry) ---

Geom Title=Existing Conditions
Program Version=4.10

River Reach=BEST BRANCH     ,Reach-1
Reach XY= 30
      2272608.64       13400728.        2271398.     13400805.58
      2270951.82     13400224.85      2270607.72     13399226.85
      2270427.99     13397586.49      2270816.26     13396906.57
      2270567.93     13395931.77      2270827.72     13395626.85
      2270049.29     13394858.91      2269633.12     13394780.07
      2269400.91     13393750.34      2268549.07      13393156.3
      2268685.95     13392587.56      2268364.42     13391857.22
      2268904.19     13391035.75      2268982.38     13390453.79
      2268580.24     13389811.42      2268136.43     13389569.56
      2267558.71     13389524.45      2266859.53     13388770.81
      2266920.41     13388157.91      2267227.18     13387516.96
      2266559.35     13386501.15      2266824.89      13386342.3
      2266745.93     13385749.49      2267055.08     13385411.23
      2266697.54     13385076.89      2267212.99     13384467.23
      2266988.63     13383686.23      2267137.72     13383356.85

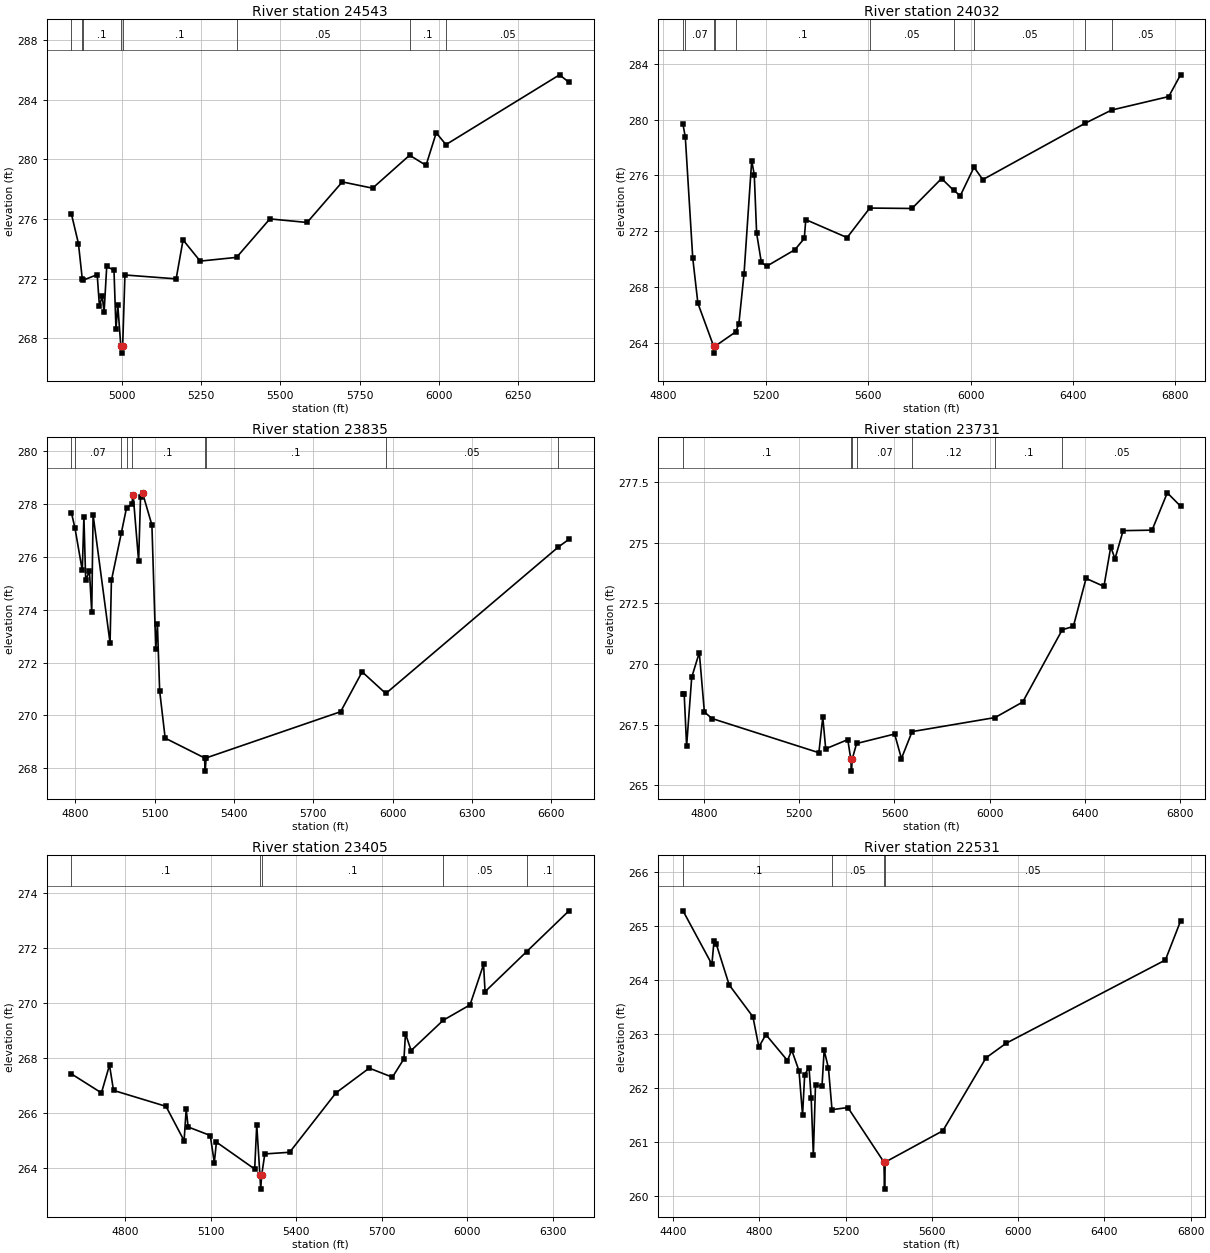
Type RM Length L Ch R = 1 ,24543   ,880,880,880
BEGIN DESCRIPTION:
BEST BRANCH 30.0
END DESCRIPTION:
XS GIS Cut Line= 3
      2272383.36     13400679.95      2272505.02     13400895.53
      2273142.01     13402052.88
#Sta/Elev= 30
  4841.4  276.33  4863.5  274.35  4875.8  271.94  4876.8  271.88  4922.7  272.26
  4929.7  270.15  4938.6  270.83  4944.4  269.73  4952.7  272.81  4975.6  272.56
  4981.9  268.61  4987.7   270.2    4997   267.5  4999.8     267    5003   267.5
  5010.1  272.24  5171.6  271.98  5193.4  274.59  5247.3  273.17    5362  273.42
  5467.1     276  5584.4  275.76  5695.4  278.48  5790.9  278.06  5907.7  280.27
  5959.4  279.59  5991.6  281.77  6022.2  280.98  6380.3  285.66    6410  285.16
#Mann= 8 ,-1 , 0
  4841.4      .1       0  4875.8     .07       0  4876.8      .1       0
    4997     .07       0    5003      .1       0    5362     .05       0
  5907.7      .1       0  6022.2     .05       0
Bank Sta=4997,5003
XS Rating Curve= 0 ,0
Exp/Cntr=0.3,0.1

Type RM Length L Ch R = 1 ,24032   ,197,197,197
BEGIN DESCRIPTION:
BEST BRANCH 30.1
END DESCRIPTION:
XS GIS Cut Line= 3
      2271991.91     13400688.78      2271984.97     13400980.34
      2272856.12     13402382.51
#Sta/Elev= 30
  4877.5  279.65  4886.5  278.74  4915.6  270.04  4935.6  266.82    4997  263.74
  4999.8  263.24    5003  263.74  5083.7  264.77  5095.6  265.36  5115.6   268.9
  5145.7  277.06  5155.7  276.04  5164.9  271.85  5183.3  269.75  5204.5  269.48
  5314.3  270.66    5351  271.47  5356.8  272.82  5518.2  271.53  5606.6  273.65
  5771.3  273.62    5887  275.77  5934.6  274.91  5960.2  274.54  6013.5  276.58
    6048  275.69    6447  279.73  6550.5  280.68  6773.8  281.65  6819.9  283.21
#Mann= 10 ,-1 , 0
  4877.5      .1       0  4886.5     .07       0    4997     .07       0
    5003     .07       0  5083.7      .1       0  5606.6     .05       0
  5934.6      .1       0  6013.5     .05       0    6447      .1       0
  6550.5     .05       0
Bank Sta=4997,5003
XS Rating Curve= 0 ,0
Exp/Cntr=0.3,0.1

Type RM Length L Ch R = 1 ,23835   ,104,104,104
BEGIN DESCRIPTION:
Mapping XS 4ccb5739
END DESCRIPTION:
XS GIS Cut Line= 6
      2271869.72     13400682.85      2271821.87     13400750.21
      2271804.51     13400871.74        2271900.     13401001.95
      2272108.33     13401809.24      2272463.48     13402389.61
#Sta/Elev= 30
  4785.1  277.68  4798.6  277.09  4826.2  275.49  4832.3  277.52  4839.1  275.12
  4853.2  275.47  4861.9  273.91    4867   277.6  4931.2  272.74  4936.3  275.11
  4973.4  276.89  4993.6  277.87    5013  277.99  5018.4  278.36  5039.2  275.84
  5046.4  278.26  5053.9  278.43  5089.4  277.21    5104  272.51  5110.2  273.45
  5118.7  270.93  5139.5  269.14  5288.3  268.39    5291  267.89  5294.3  268.39
  5802.8  270.14  5884.2  271.65  5973.6  270.83  6626.2  276.38  6666.1  276.67
#Mann= 9 ,-1 , 0
  4785.1      .1       0  4798.6     .07       0  4973.4      .1       0
  4993.6     .07       0    5013      .1       0  5288.3     .07       0
  5294.3      .1       0  5973.6     .05       0  6626.2      .1       0
Bank Sta=5018.4,5053.9
XS Rating Curve= 0 ,0
Exp/Cntr=0.3,0.1

Type RM Length L Ch R = 1 ,23731   ,326,326,326
BEGIN DESCRIPTION:
Mapping XS 4d054275
END DESCRIPTION:
XS GIS Cut Line= 4
      2271769.79     13400602.64      2271709.03     13400767.57
      2271700.35     13401045.35      2271032.32     13402537.57
#Sta/Elev= 30
  4712.2  268.77  4717.1  268.77  4727.3  266.61  4748.7  269.45  4780.6  270.47
  4801.9  268.02  4833.9  267.75  5282.5  266.34    5299  267.81  5311.2   266.5
  5403.9  266.88  5416.5  266.08  5419.3  265.58  5422.5  266.08    5441  266.72
  5600.5  267.11  5629.1   266.1  5673.9  267.21  6022.2  267.79  6138.1  268.43
  6304.2  271.41  6350.8  271.55  6404.2  273.53  6479.2   273.2  6507.9  274.83
  6525.6  274.34  6559.8   275.5  6681.2  275.52  6745.2  277.06  6800.8  276.51
#Mann= 7 ,-1 , 0
  4712.2      .1       0  5416.5     .07       0  5422.5      .1       0
    5441     .07       0  5673.9     .12       0  6022.2      .1       0
  6304.2     .05       0
Bank Sta=5416.5,5422.5
XS Rating Curve= 0 ,0
Exp/Cntr=0.3,0.1

Type RM Length L Ch R = 1 ,23405   ,874,874,874
BEGIN DESCRIPTION:
Mapping XS 1cdb2afd
END DESCRIPTION:
XS GIS Cut Line= 3
      2271674.28     13400524.54      2271188.19     13401036.67
      2270927.99     13402042.78
#Sta/Elev= 30
    4611  267.41  4716.3  266.72  4744.6  267.73  4758.7  266.81  4942.8  266.23
  5006.3  264.98  5013.6  266.13  5020.5  265.48  5098.1  265.17  5112.3  264.18
  5119.6  264.93  5253.9  263.95  5261.1  265.56  5272.3  263.72    5275  263.22
  5278.3  263.72  5289.4   264.5  5376.5  264.56    5539  266.72  5655.7  267.62
    5737  267.29  5777.6  267.96  5782.8  268.87  5802.7  268.26  5915.2  269.36
  6009.3  269.92  6056.8  271.39    6062   270.4  6208.2  271.86  6356.3  273.34
#Mann= 5 ,-1 , 0
    4611      .1       0  5272.3     .07       0  5278.3      .1       0
  5915.2     .05       0  6208.2      .1       0
Bank Sta=5272.3,5278.3
XS Rating Curve= 0 ,0
Exp/Cntr=0.3,0.1

Type RM Length L Ch R = 1 ,22531   ,294,294,294
BEGIN DESCRIPTION:
Mapping XS dd75c564
END DESCRIPTION:
XS GIS Cut Line= 3
      2271501.51     13400152.38      2270030.74     13400233.28
      2269729.41     13401012.34
#Sta/Elev= 30
  4445.2  265.28  4579.2  264.29  4589.2  264.73  4599.2  264.67  4659.3  263.91
  4769.5  263.32  4797.1  262.76  4829.6  262.99  4929.7  262.51  4949.8   262.7
  4983.3  262.32  4999.8   261.5  5009.8  262.25  5029.9  262.38  5039.9  261.81
  5049.9  260.76  5059.9  262.06    5090  262.03    5100   262.7    5120  262.37
  5136.5   261.6  5210.1  261.64  5377.4  260.63  5380.2  260.13  5383.4  260.63
  5650.8  261.21  5851.1  262.56  5944.6  262.83  6683.3  264.37  6753.5  265.09
#Mann= 4 ,-1 , 0
  4445.2      .1       0  5136.5     .05       0  5377.4     .07       0
  5383.4     .05       0
Bank Sta=5377.4,5383.4
XS Rating Curve= 0 ,0
Exp/Cntr=0.3,0.1

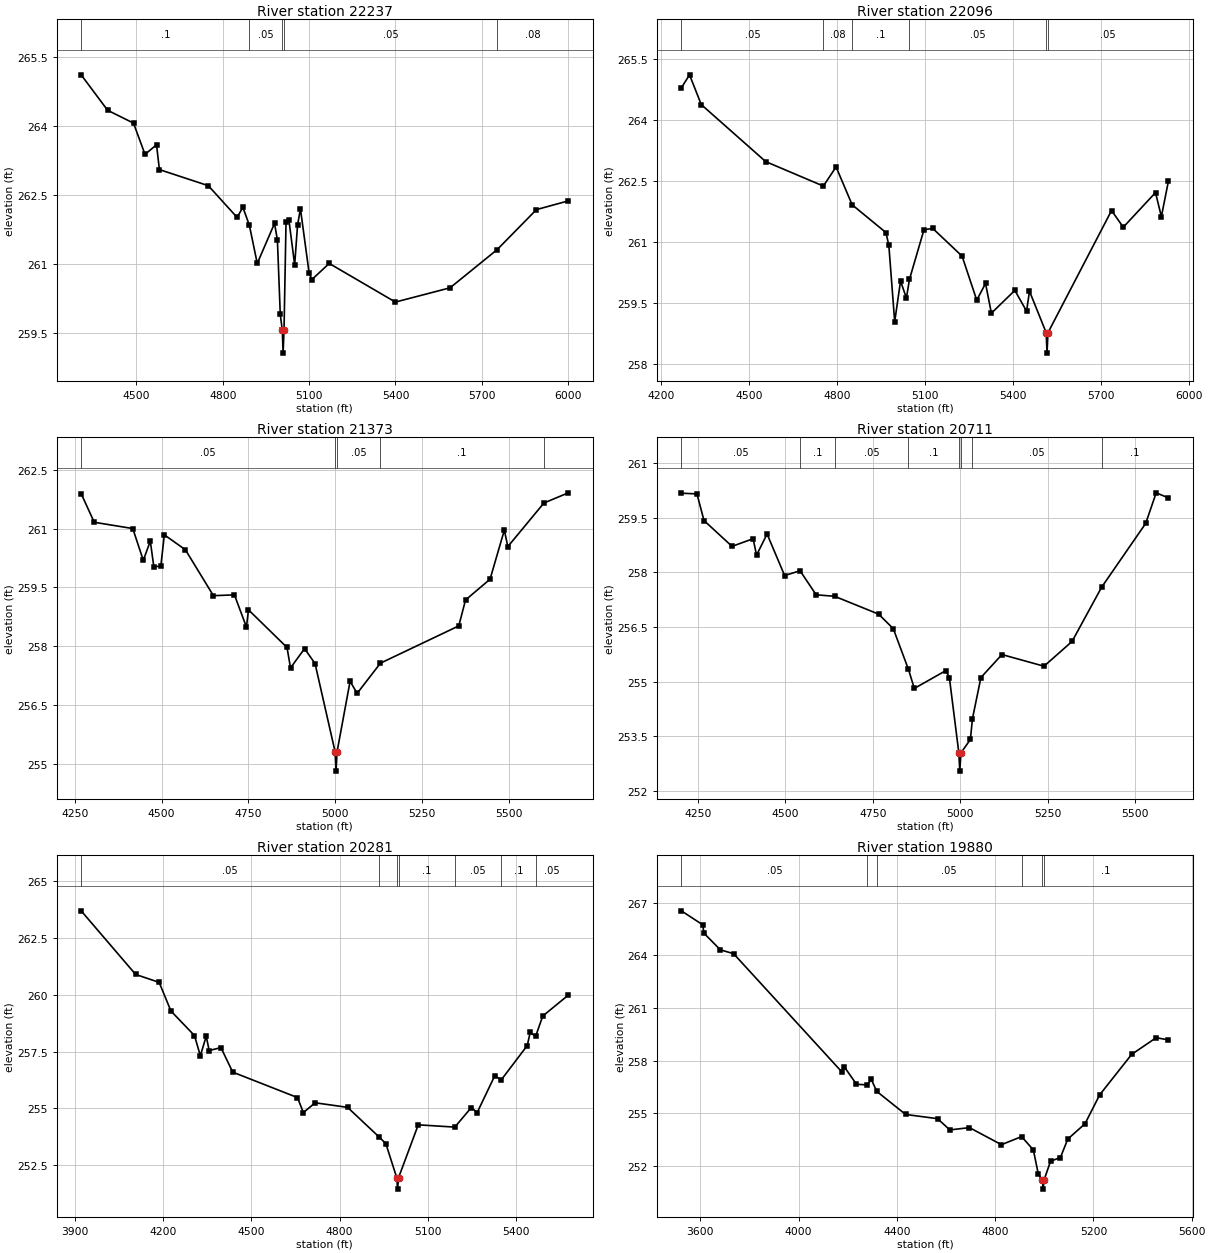
Type RM Length L Ch R = 1 ,22237   ,141,141,141
BEGIN DESCRIPTION:
BEST BRANCH 29.0
END DESCRIPTION:
XS GIS Cut Line= 2
      2271609.65     13399910.84      2269916.98     13399919.52
#Sta/Elev= 30
  4307.9  265.11  4399.8  264.34  4489.8  264.06  4529.8  263.38  4569.8  263.59
  4579.8  263.05  4749.8   262.7  4849.8  262.01  4869.8  262.23  4892.4  261.84
  4919.8  261.01  4979.8  261.88  4989.8  261.52  4999.8   259.9  5006.8  259.56
  5009.6  259.06  5012.8  259.56  5019.8  261.92  5029.8  261.95  5049.8  260.98
  5059.8  261.84  5069.8   262.2  5099.8  260.81  5109.8  260.66  5169.8  261.01
  5399.8  260.17  5589.8  260.48  5753.3  261.31  5889.9  262.18  6000.6  262.37
#Mann= 5 ,-1 , 0
  4307.9      .1       0  4892.4     .05       0  5006.8     .04       0
  5012.8     .05       0  5753.3     .08       0
Bank Sta=5006.8,5012.8
XS Rating Curve= 0 ,0
Exp/Cntr=0.3,0.1

Type RM Length L Ch R = 1 ,22096   ,723,723,723
BEGIN DESCRIPTION:
BEST BRANCH 28.0
END DESCRIPTION:
XS GIS Cut Line= 2
      2271635.76     13399771.95      2269973.47     13399776.29
#Sta/Elev= 30
    4269  264.78    4297   265.1    4337  264.37    4557  262.97  4753.6  262.37
    4797  262.84  4851.9  261.91    4967  261.23    4977  260.92    4997  259.04
    5017  260.04    5037  259.62  5047.4  260.08    5097   261.3    5127  261.33
    5227  260.65    5277  259.57    5307  259.98    5327  259.25    5407  259.81
    5447   259.3    5457  259.79    5514  258.77  5516.8  258.27    5520  258.77
    5737  261.77    5777  261.36    5887  262.21    5907  261.62  5931.3   262.5
#Mann= 6 ,-1 , 0
    4269     .05       0  4753.6     .08       0  4851.9      .1       0
  5047.4     .05       0    5514     .07       0    5520     .05       0
Bank Sta=5514,5520
XS Rating Curve= 0 ,0
Exp/Cntr=0.3,0.1

Type RM Length L Ch R = 1 ,21373   ,662,662,662
BEGIN DESCRIPTION:
BEST BRANCH 27.0
END DESCRIPTION:
XS GIS Cut Line= 2
      2271325.06     13399034.58      2269935.17     13399233.14
#Sta/Elev= 30
  4267.9  261.89  4305.6  261.16  4416.7     261    4447  260.19  4467.2  260.68
  4477.3  260.03  4497.5  260.04  4507.6  260.84  4568.3  260.46  4649.1  259.29
  4709.7  259.31  4744.3  258.49  4750.1  258.93  4861.2  257.97  4871.3  257.45
  4911.7  257.94    4942  257.56  4999.6  255.32  5002.4  254.82  5005.6  255.32
    5043  257.11  5063.2   256.8  5130.4  257.57  5356.2  258.52  5375.7  259.18
  5446.4  259.71  5487.5  260.96  5497.6  260.54  5601.5  261.65  5671.9  261.91
#Mann= 5 ,-1 , 0
  4267.9     .05       0  4999.6    .035       0  5005.6     .05       0
  5130.4      .1       0  5601.5     .05       0
Bank Sta=4999.6,5005.6
XS Rating Curve= 0 ,0
Exp/Cntr=0.3,0.1

Type RM Length L Ch R = 1 ,20711   ,430,430,430
BEGIN DESCRIPTION:
BEST BRANCH 26.0
END DESCRIPTION:
XS GIS Cut Line= 2
      2271332.35     13398438.92       2269942.6     13398519.81
#Sta/Elev= 30
  4202.8  260.17  4247.5  260.15  4267.5  259.42  4347.7  258.71  4407.8  258.92
  4417.8  258.47  4447.8  259.05  4497.9  257.91  4542.1  258.04  4588.1  257.38
  4640.7  257.34  4766.5  256.85  4808.5  256.45  4851.9  255.33  4868.6  254.81
  4958.7   255.3  4968.7  255.11  4995.8  253.04  4998.5  252.54  5001.8  253.04
  5028.8  253.41  5034.7  253.98  5058.9  255.11    5119  255.74  5239.2  255.42
  5319.3   256.1  5403.9  257.59  5529.7  259.34  5559.7  260.18  5594.9  260.04
#Mann= 8 ,-1 , 0
  4202.8     .05       0  4542.1      .1       0  4640.7     .05       0
  4851.9      .1       0  4995.8     .07       0  5001.8      .1       0
  5034.7     .05       0  5403.9      .1       0
Bank Sta=4995.8,5001.8
XS Rating Curve= 0 ,0
Exp/Cntr=0.3,0.1

Type RM Length L Ch R = 1 ,20281   ,401,401,401
BEGIN DESCRIPTION:
BEST BRANCH 25.0
END DESCRIPTION:
XS GIS Cut Line= 3
      2271553.03     13398056.52      2270964.69     13398034.45
      2269898.38     13398107.99
#Sta/Elev= 30
  3920.6   263.7    4106   260.9  4186.1  260.55  4226.1  259.29  4306.2  258.21
  4326.2  257.32  4346.2  258.18  4356.2  257.55  4396.2  257.68  4436.3   256.6
  4656.7  255.48  4676.7  254.82  4716.8  255.25  4827.1  255.05    4934  253.75
  4957.4  253.45  4994.5  251.95  4997.2  251.45  5000.5  251.95  5067.6  254.28
    5192  254.18  5248.1  255.04  5268.1  254.82  5328.3  256.45  5349.5  256.25
  5438.5  257.77  5448.5  258.35  5466.8  258.17  5491.3  259.07  5578.2  259.99
#Mann= 7 ,-1 , 0
  3920.6     .05       0    4934      .1       0  4994.5     .07       0
  5000.5      .1       0    5192     .05       0  5349.5      .1       0
  5466.8     .05       0
Bank Sta=4994.5,5000.5
XS Rating Curve= 0 ,0
Exp/Cntr=0.3,0.1

Type RM Length L Ch R = 1 ,19880   ,1390,1390,1390
BEGIN DESCRIPTION:
BEST BRANCH 24.0
END DESCRIPTION:
XS GIS Cut Line= 3
      2271891.28      13397835.9      2271339.74     13397688.82
      2269927.83     13397666.76
#Sta/Elev= 30
  3522.8  266.53  3609.3  265.74  3615.3  265.25  3681.7  264.31  3735.6  264.09
  4175.6  257.37  4185.6  257.66  4235.7  256.66    4280  256.62  4295.7  256.94
  4318.6  256.25  4435.7  254.94  4565.7   254.7  4615.7  254.06  4695.7  254.19
  4825.7  253.22  4907.9  253.68  4955.7  252.92  4975.7  251.55  4992.7  251.19
  4995.5  250.69  4998.7  251.19  5025.7  252.28  5065.8  252.49  5095.8  253.54
  5165.8  254.41  5225.8  256.06  5355.8  258.36  5455.8  259.31  5505.7  259.18
#Mann= 6 ,-1 , 0
  3522.8     .05       0    4280      .1       0  4318.6     .05       0
  4907.9      .1       0  4992.7     .07       0  4998.7      .1       0
Bank Sta=4992.7,4998.7
XS Rating Curve= 0 ,0
Exp/Cntr=0.3,0.1

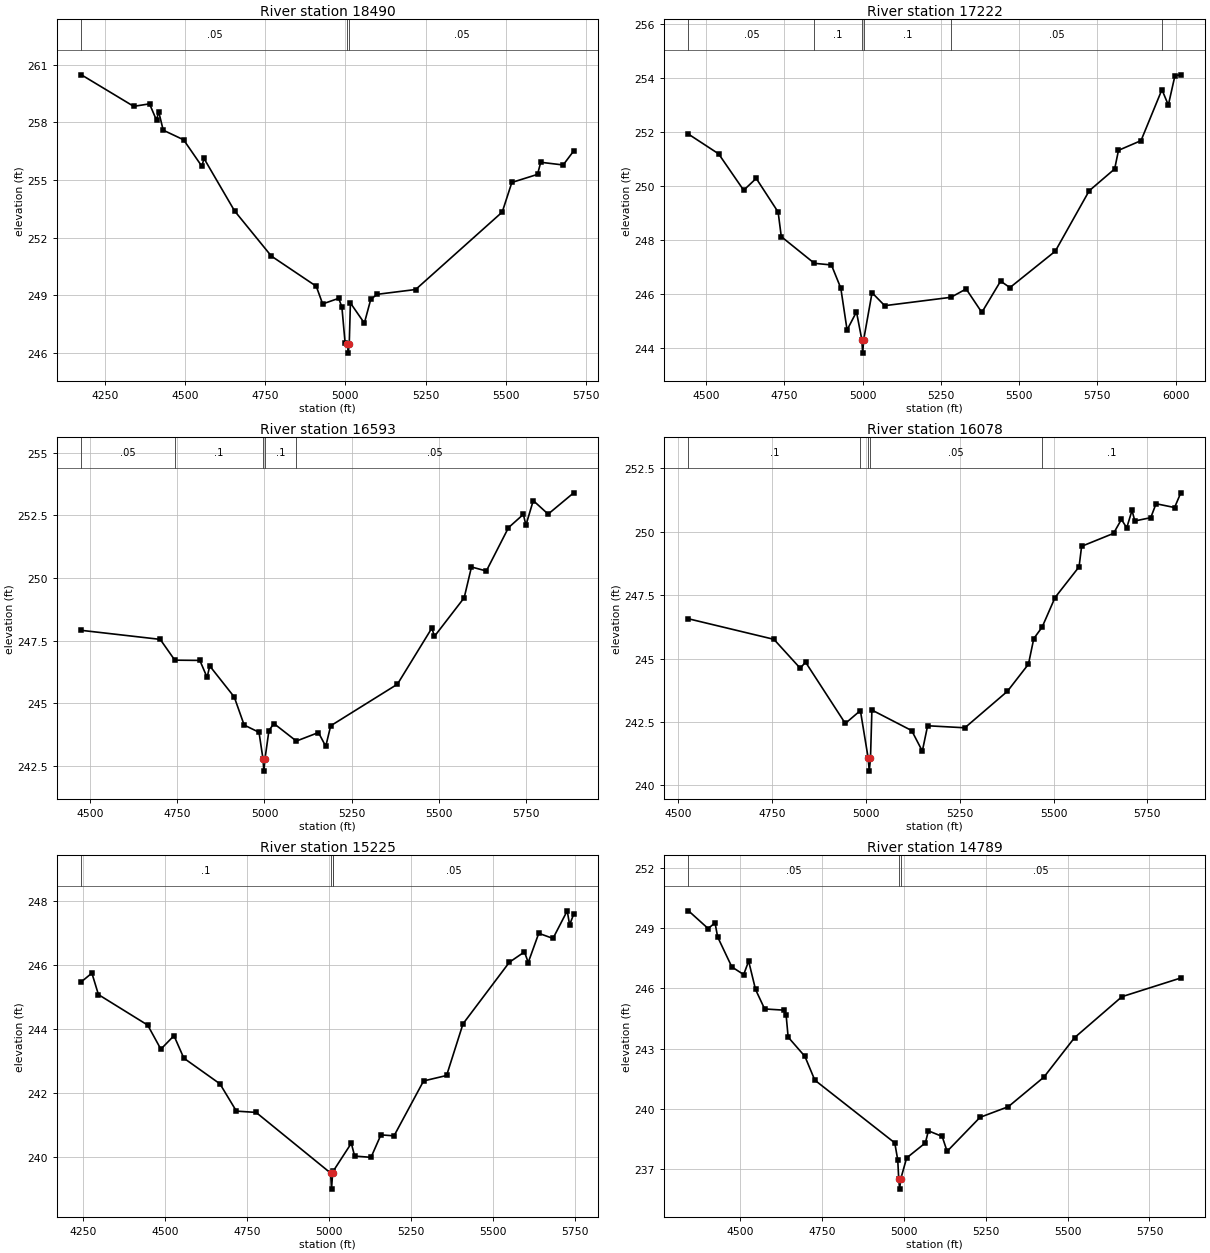
Type RM Length L Ch R = 1 ,18490   ,1268,1268,1268
BEGIN DESCRIPTION:
BEST BRANCH 23.0
END DESCRIPTION:
XS GIS Cut Line= 3
      2271494.17     13396850.46      2271141.19     13396541.61
      2270074.82     13396571.02
#Sta/Elev= 30
  4176.5  260.48  4339.7  258.84    4389  258.97  4410.8  258.12  4417.5  258.57
  4431.7   257.6  4495.3   257.1  4552.3  255.72  4558.9  256.13  4654.3   253.4
    4769  251.05  4909.1  249.48  4929.1  248.56  4979.1  248.85  4989.1   248.4
  4999.1  246.54  5006.1   246.5  5008.9     246  5012.1   246.5  5015.7  248.61
  5059.2  247.56  5079.2   248.8  5099.2  249.06  5219.2  249.31  5489.3  253.34
  5519.3  254.88  5599.4   255.3  5609.4  255.93  5679.4  255.79  5712.3  256.52
#Mann= 3 ,-1 , 0
  4176.5     .05       0  5006.1     .03       0  5012.1     .05       0
Bank Sta=5006.1,5012.1
XS Rating Curve= 0 ,0
Exp/Cntr=0.3,0.1

Type RM Length L Ch R = 1 ,17222   ,629,629,629
BEGIN DESCRIPTION:
BEST BRANCH 22.0
END DESCRIPTION:
XS GIS Cut Line= 3
      2271383.84     13395615.01      2270251.36     13395666.49
      2270009.46     13396033.01
#Sta/Elev= 30
    4444  251.92  4540.2  251.19  4620.3  249.84  4660.3  250.28  4730.4  249.03
  4740.4  248.12  4846.2  247.13  4900.6  247.07  4930.6  246.21  4950.6  244.66
  4980.7  245.33  4997.7   244.3  5000.4   243.8  5003.7   244.3  5030.4  246.04
  5070.8  245.56  5282.4  245.87    5331  246.18  5381.1  245.31  5441.1  246.47
  5470.9  246.23  5615.8  247.58  5724.1  249.82  5805.5  250.63  5817.7  251.32
  5889.7  251.68  5956.5  253.57    5977     253  5998.1  254.09  6016.8  254.12
#Mann= 6 ,-1 , 0
    4444     .05       0  4846.2      .1       0  4997.7     .07       0
  5003.7      .1       0  5282.4     .05       0  5956.5      .1       0
Bank Sta=4997.7,5003.7
XS Rating Curve= 0 ,0
Exp/Cntr=0.3,0.1

Type RM Length L Ch R = 1 ,16593   ,515,515,515
BEGIN DESCRIPTION:
BEST BRANCH 21.0
END DESCRIPTION:
XS GIS Cut Line= 2
      2270773.46     13394813.47      2269824.82     13395857.71
#Sta/Elev= 30
  4475.4  247.91  4701.2  247.55  4743.1  246.72  4814.8  246.71  4835.7  246.03
  4843.1  246.49  4913.4  245.25  4941.8  244.13  4984.4  243.84  4995.6  242.79
  4998.3  242.29  5001.6  242.79  5012.8  243.91    5027  244.19  5091.4  243.49
  5154.7  243.83  5175.6  243.28  5189.8   244.1    5381  245.76  5479.7     248
  5487.1  247.67  5572.3  249.21  5593.2  250.44  5635.8  250.28  5699.3  252.01
  5741.9  252.54  5749.3  252.11  5770.3  253.09  5812.9  252.55  5886.2   253.4
#Mann= 5 ,-1 , 0
  4475.4     .05       0  4743.1      .1       0  4995.6     .07       0
  5001.6      .1       0  5091.4     .05       0
Bank Sta=4995.6,5001.6
XS Rating Curve= 0 ,0
Exp/Cntr=0.3,0.1

Type RM Length L Ch R = 1 ,16078   ,853,853,853
BEGIN DESCRIPTION:
BEST BRANCH 20.0
END DESCRIPTION:
XS GIS Cut Line= 3
      2270486.68     13394688.42      2270266.07     13394784.02
       2269479.3     13395511.96
#Sta/Elev= 30
  4526.9  246.57  4754.6  245.76  4824.7  244.62  4838.9  244.86  4944.9  242.44
  4985.1  242.95    5006  241.06  5008.7  240.56    5012  241.06  5015.8  242.97
  5121.8  242.16  5150.2  241.35  5164.3  242.35  5263.6  242.27    5377  243.71
  5433.1  244.78  5447.3  245.79  5469.5  246.24    5504  247.41    5568  248.62
  5574.8  249.43  5659.9  249.94  5680.9  250.49  5695.1  250.16  5709.2  250.85
  5716.6  250.43  5759.1  250.56  5773.2  251.11  5822.6  250.96  5839.2  251.54
#Mann= 5 ,-1 , 0
  4526.9      .1       0  4985.1     .05       0    5006    .035       0
    5012     .05       0  5469.5      .1       0
Bank Sta=5006,5012
XS Rating Curve= 0 ,0
Exp/Cntr=0.3,0.1

Type RM Length L Ch R = 1 ,15225   ,436,436,436
BEGIN DESCRIPTION:
BEST BRANCH 19.0
END DESCRIPTION:
XS GIS Cut Line= 3
      2270339.57     13394556.05      2269126.21     13394592.82
      2268876.82     13394732.18
#Sta/Elev= 30
  4246.2  245.47  4278.1  245.74  4298.1  245.07  4448.1  244.12  4488.2  243.37
  4528.2  243.79  4558.2  243.09  4668.2  242.29  4718.3  241.44  4778.3   241.4
  5005.4  239.51  5008.1  239.01  5011.4  239.51  5012.6  239.56  5068.4  240.44
  5078.4  240.04  5128.4     240  5158.5   240.7  5198.5  240.67  5288.5  242.38
  5358.6  242.55  5408.6  244.16    5550  246.08  5595.8   246.4  5607.3  246.07
  5639.3  246.98  5682.7  246.82  5726.1  247.68  5733.3  247.24  5745.8  247.58
#Mann= 4 ,-1 , 0
  4246.2      .1       0  5005.4     .07       0  5011.4      .1       0
  5012.6     .05       0
Bank Sta=5005.4,5011.4
XS Rating Curve= 0 ,0
Exp/Cntr=0.3,0.1

Type RM Length L Ch R = 1 ,14789   ,691,691,691
BEGIN DESCRIPTION:
BEST BRANCH 18.0
END DESCRIPTION:
XS GIS Cut Line= 2
       2270082.2      13393798.6      2268824.97     13394622.06
#Sta/Elev= 30
  4342.7  249.86  4402.6  248.98  4423.7  249.26  4431.7  248.56    4475  247.07
  4511.2  246.69  4526.3  247.36  4547.3  245.95  4575.2  244.98  4634.8  244.92
  4640.8  244.66  4646.9  243.58  4698.1  242.62  4728.3  241.44  4972.4  238.32
  4981.5  237.47  4984.5  236.52  4987.3  236.02  4990.5  236.52  5008.6  237.57
  5065.9  238.32    5075  238.92  5117.1  238.64  5132.2   237.9  5232.7  239.59
  5319.1  240.12  5427.7  241.59  5521.1  243.55  5665.9  245.59  5845.6  246.52
#Mann= 3 ,-1 , 0
  4342.7     .05       0  4984.5     .03       0  4990.5     .05       0
Bank Sta=4984.5,4990.5
XS Rating Curve= 0 ,0
Exp/Cntr=0.3,0.1

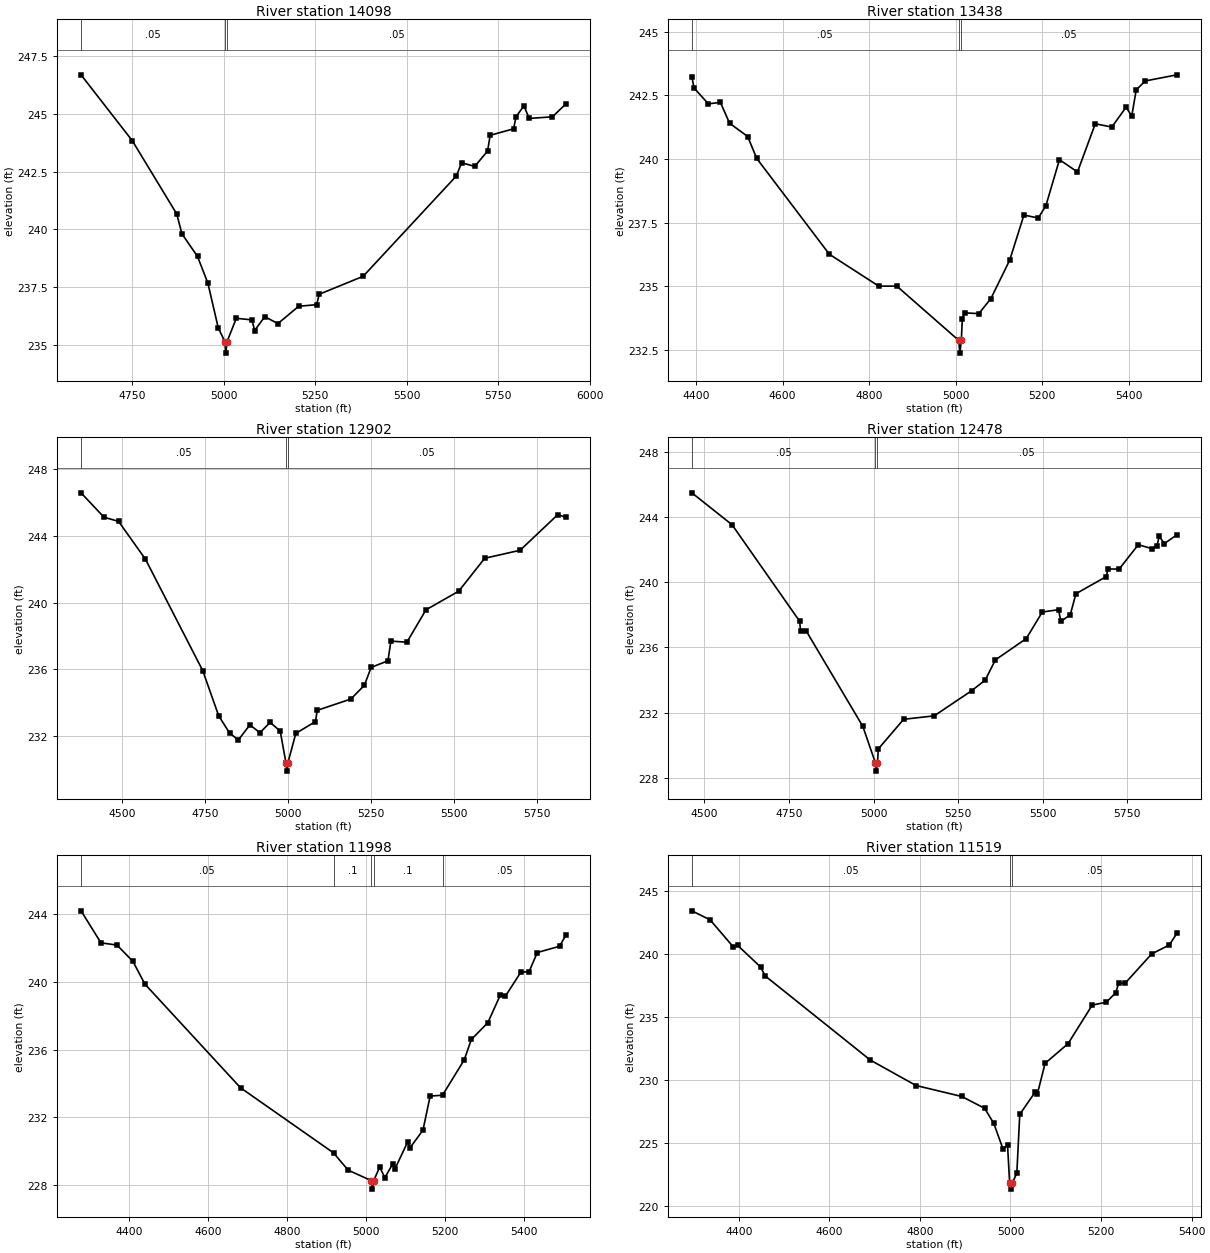
Type RM Length L Ch R = 1 ,14098   ,660,660,660
BEGIN DESCRIPTION:
BEST BRANCH 17.0
END DESCRIPTION:
XS GIS Cut Line= 3
      2269596.87     13393460.31      2269376.24     13393489.73
      2268552.64     13394225.09
#Sta/Elev= 30
  4609.3   246.7  4749.7  243.84    4871  240.67  4885.2  239.81  4927.8  238.83
  4956.2  237.67  4984.6  235.73  5002.6  235.14  5005.3  234.64  5008.6  235.14
    5034  236.15  5076.6  236.08  5084.1  235.62  5111.7  236.22  5147.7  235.92
  5204.5  236.67  5253.8  236.74  5260.5  237.19  5380.9  237.97  5635.9  242.32
  5650.1  242.89    5686  242.73  5721.2   243.4  5728.1  244.08  5792.2  244.36
  5798.9  244.88  5820.6  245.36  5834.8  244.81  5898.4  244.88    5936  245.45
#Mann= 3 ,-1 , 0
  4609.3     .05       0  5002.6     .03       0  5008.6     .05       0
Bank Sta=5002.6,5008.6
XS Rating Curve= 0 ,0
Exp/Cntr=0.3,0.1

Type RM Length L Ch R = 1 ,13438   ,536,536,536
BEGIN DESCRIPTION:
BEST BRANCH 16.0
END DESCRIPTION:
XS GIS Cut Line= 2
      2269251.25     13393151.44      2268177.55     13393475.02
#Sta/Elev= 30
  4390.1  243.21  4395.3  242.78  4428.3  242.16    4456  242.22  4477.3   241.4
  4519.1  240.88    4540  240.02  4707.9  236.26    4822  235.01  4863.8  235.01
    5007  232.88  5009.7  232.38    5013  232.88  5015.3  233.73  5020.5  233.96
  5053.5  233.93  5081.3  234.52  5124.9  236.03  5157.7   237.8  5190.7  237.68
  5208.4  238.16  5239.8  239.97  5281.5  239.49  5322.7  241.38  5360.9  241.25
  5393.9  242.03  5406.9  241.68  5417.3  242.71  5438.2  243.06  5511.5   243.3
#Mann= 3 ,-1 , 0
  4390.1     .05       0    5007     .03       0    5013     .05       0
Bank Sta=5007,5013
XS Rating Curve= 0 ,0
Exp/Cntr=0.3,0.1

Type RM Length L Ch R = 1 ,12902   ,424,424,424
BEGIN DESCRIPTION:
BEST BRANCH 15.0
END DESCRIPTION:
XS GIS Cut Line= 3
      2269229.14     13392739.63       2268265.8     13392908.77
      2267957.72     13393282.87
#Sta/Elev= 30
  4375.1  246.57  4444.2  245.11  4488.2  244.86  4569.4  242.59    4742  235.92
  4790.2  233.21  4823.3  232.17  4849.6  231.77  4884.2  232.67  4914.6   232.2
  4945.1  232.82  4975.6   232.3  4992.9   230.4  4995.6   229.9  4998.9   230.4
  5022.7  232.16    5082  232.87  5087.2  233.54  5188.8  234.22  5229.4  235.04
  5249.7  236.11  5300.5  236.51  5309.4  237.69  5357.6  237.62    5415  239.56
    5514  240.68  5592.2  242.65    5699  243.13  5812.4  245.26  5837.8   245.1
#Mann= 3 ,-1 , 0
  4375.1     .05       0  4992.9     .03       0  4998.9     .05       0
Bank Sta=4992.9,4998.9
XS Rating Curve= 0 ,0
Exp/Cntr=0.3,0.1

Type RM Length L Ch R = 1 ,12478   ,480,480,480
BEGIN DESCRIPTION:
BEST BRANCH 14.0
END DESCRIPTION:
XS GIS Cut Line= 4
      2269155.63     13392496.95      2268839.41     13392430.76
      2268126.08     13392496.95      2267949.59     13392849.92
#Sta/Elev= 30
  4462.9  245.48  4581.8  243.52  4781.6   237.6  4784.3  237.01  4800.3  237.03
  4968.4  231.15  5005.6  228.91  5008.4  228.41  5011.6  228.91    5014  229.77
    5089  231.59  5179.3   231.8  5289.8  233.34    5330  233.99  5360.1  235.23
  5451.4  236.54    5499  238.17    5547  238.31  5553.6  237.59  5581.5     238
  5598.3  239.29  5687.7  240.34  5693.3  240.81  5725.9   240.8  5782.8   242.3
  5821.9  242.06  5837.7   242.2  5844.3  242.81    5860  242.37    5897  242.91
#Mann= 3 ,-1 , 0
  4462.9     .05       0  5005.6     .03       0  5011.6     .05       0
Bank Sta=5005.6,5011.6
XS Rating Curve= 0 ,0
Exp/Cntr=0.3,0.1

Type RM Length L Ch R = 1 ,11998   ,479,479,479
BEGIN DESCRIPTION:
BEST BRANCH 13.0
END DESCRIPTION:
XS GIS Cut Line= 3
      2269137.76     13392146.86      2268437.72     13392046.85
      2267937.68     13391896.84
#Sta/Elev= 30
  4278.7  244.19  4329.2   242.3  4369.7  242.17  4410.1  241.21  4440.4  239.87
  4682.8  233.75  4918.4  229.91  4955.5  228.89  5014.2  228.27  5016.9  227.77
  5020.2  228.27  5035.4  229.07  5048.5  228.45  5068.5  229.26  5073.7  228.94
  5106.8  230.58    5112   230.2  5145.1  231.25  5163.3  233.26  5194.6  233.31
  5249.5  235.39  5267.7   236.6  5309.5  237.59  5340.8  239.21  5353.9  239.15
    5393  240.57  5413.9   240.6  5434.8  241.73  5491.3   242.1  5507.9  242.79
#Mann= 5 ,-1 , 0
  4278.7     .05       0  4918.4      .1       0  5014.2     .07       0
  5020.2      .1       0  5194.6     .05       0
Bank Sta=5014.2,5020.2
XS Rating Curve= 0 ,0
Exp/Cntr=0.3,0.1

Type RM Length L Ch R = 1 ,11519   ,423,423,423
BEGIN DESCRIPTION:
BEST BRANCH 12.0
END DESCRIPTION:
XS GIS Cut Line= 3
      2269137.75     13391696.86      2268437.72     13391596.85
      2268087.76     13391496.87
#Sta/Elev= 30
  4296.5  243.43  4336.9  242.71  4387.4  240.59  4397.5  240.69  4448.1  238.98
  4458.2  238.27  4690.5  231.59  4791.5  229.57  4892.5   228.7    4943  227.76
  4963.2  226.56  4983.4  224.54  4993.5  224.87  4998.1  221.85  5000.9  221.35
  5004.1  221.85    5014  222.62  5020.5  227.28  5054.3  229.04  5059.5  228.92
  5076.4  231.33  5127.1  232.89  5180.4  235.95  5211.6  236.18  5232.4  236.93
  5238.9  237.69  5253.2  237.69  5311.7  240.01  5350.7  240.72  5367.6  241.66
#Mann= 3 ,-1 , 0
  4296.5     .05       0  4998.1     .03       0  5004.1     .05       0
Bank Sta=4998.1,5004.1
XS Rating Curve= 0 ,0
Exp/Cntr=0.3,0.1

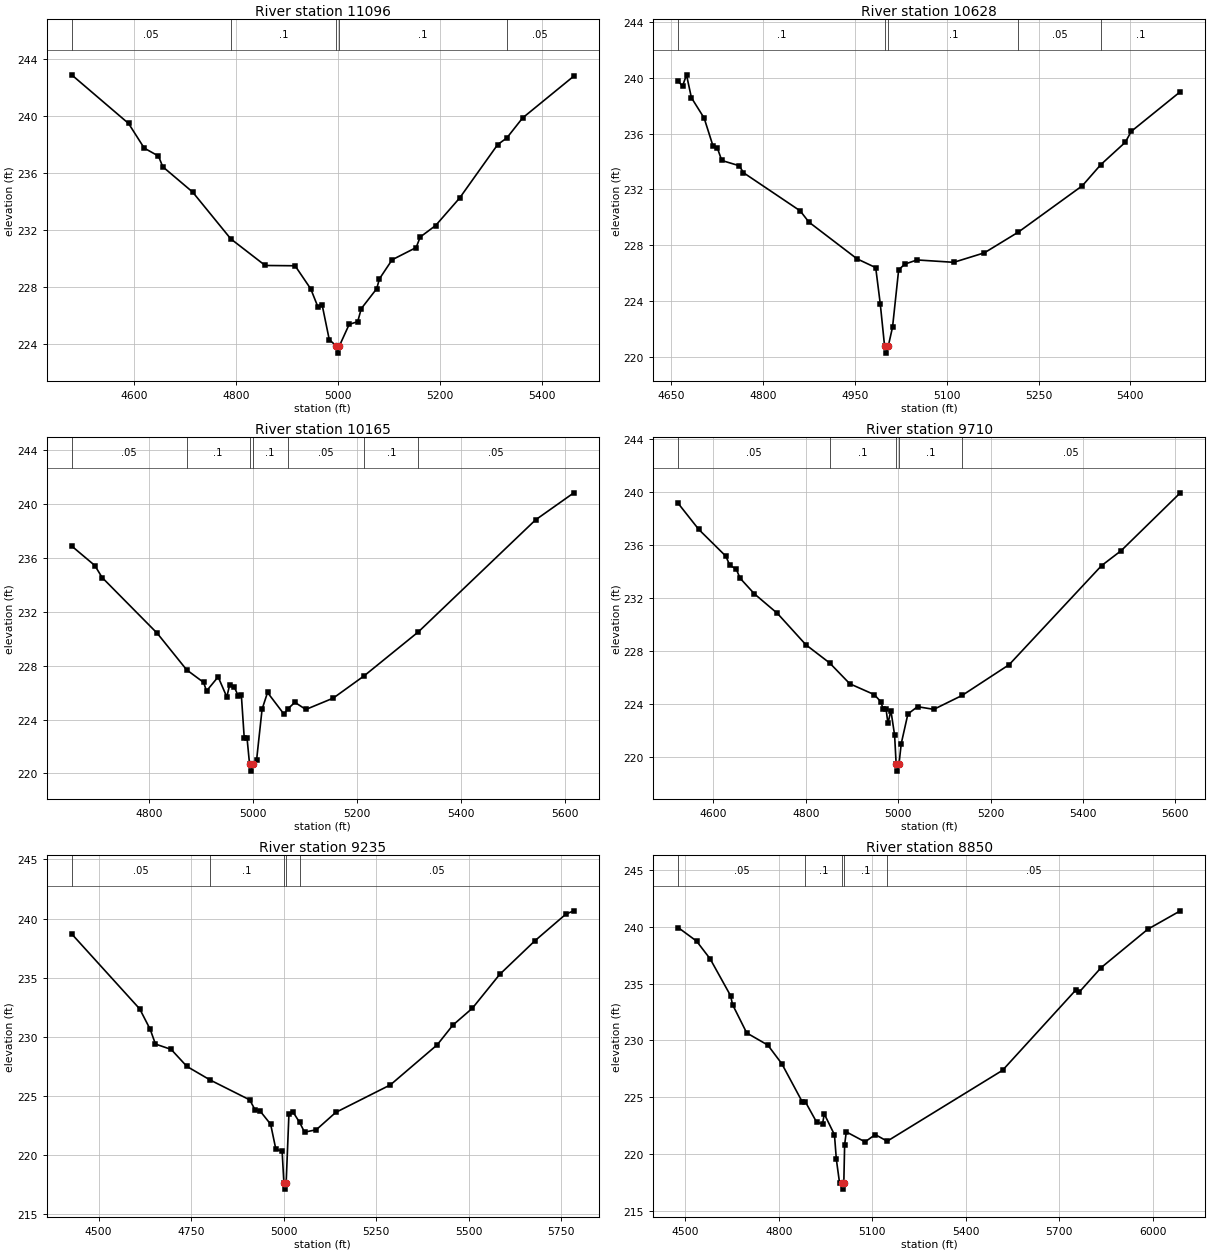
Type RM Length L Ch R = 1 ,11096   ,468,468,468
BEGIN DESCRIPTION:
BEST BRANCH 11.0
END DESCRIPTION:
XS GIS Cut Line= 3
      2269137.72     13391496.86      2268637.72     13391246.85
      2268237.74     13391096.86
#Sta/Elev= 30
  4476.8  242.91  4588.6  239.49  4619.3  237.76  4647.3   237.2  4655.7  236.45
  4714.4  234.67  4789.3  231.38  4856.9  229.51  4915.6  229.49  4946.4  227.86
  4960.4   226.6  4968.7  226.74  4982.7   224.3  4996.5  223.85  4999.2  223.35
  5002.5  223.85  5021.8  225.37  5038.5  225.56  5045.6  226.48  5075.9  227.88
  5081.2  228.57  5106.1  229.91  5153.3  230.77  5161.3  231.51  5191.6  232.32
  5238.7  234.25  5313.5  238.01  5331.3  238.47  5362.4  239.88    5463  242.82
#Mann= 5 ,-1 , 0
  4476.8     .05       0  4789.3      .1       0  4996.5     .07       0
  5002.5      .1       0  5331.3     .05       0
Bank Sta=4996.5,5002.5
XS Rating Curve= 0 ,0
Exp/Cntr=0.3,0.1

Type RM Length L Ch R = 1 ,10628   ,463,463,463
BEGIN DESCRIPTION:
BEST BRANCH 10.0
END DESCRIPTION:
XS GIS Cut Line= 3
      2269187.76     13391146.88      2268937.72     13390946.85
      2268437.72     13390946.85
#Sta/Elev= 30
  4661.4  239.76  4668.6   239.4  4675.1  240.21  4683.1  238.57  4703.9  237.11
  4718.3  235.12  4725.5  234.96  4732.7  234.07  4761.5  233.69  4767.9   233.2
  4860.7  230.46  4875.1  229.65  4953.6  227.02  4984.1  226.39  4991.6  223.78
  4998.6  220.76  5001.4  220.26  5004.6  220.76  5011.6  222.12  5021.6  226.23
  5031.6  226.64  5051.6  226.94  5111.6  226.77  5161.6  227.45  5217.2  228.94
  5321.6  232.26  5351.7  233.77  5391.6  235.37  5401.6  236.16  5481.6     239
#Mann= 5 ,-1 , 0
  4661.4      .1       0  4998.6     .07       0  5004.6      .1       0
  5217.2     .05       0  5351.7      .1       0
Bank Sta=4998.6,5004.6
XS Rating Curve= 0 ,0
Exp/Cntr=0.3,0.1

Type RM Length L Ch R = 1 ,10165   ,455,455,455
BEGIN DESCRIPTION:
BEST BRANCH 9.0
END DESCRIPTION:
XS GIS Cut Line= 3
      2269287.68     13390346.88      2268987.72     13390496.85
      2268387.74     13390696.85
#Sta/Elev= 30
    4650  236.89  4694.7  235.44  4708.7  234.55  4814.9  230.41  4871.7  227.69
  4904.3  226.76  4909.9  226.12  4932.3  227.17    4949  225.68  4954.6  226.59
    4963  226.45  4971.4  225.73    4977  225.84  4982.6  222.63    4988  222.63
  4992.9  220.67  4995.7  220.17  4998.9  220.67  5006.4  220.99    5017  224.77
  5027.5  226.01  5059.2   224.4  5066.3  224.78  5080.2  225.28  5101.3  224.75
    5154  225.59  5213.8  227.25  5318.4  230.52    5544  238.83  5617.8  240.84
#Mann= 7 ,-1 , 0
    4650     .05       0  4871.7      .1       0  4992.9     .07       0
  4998.9      .1       0  5066.3     .05       0  5213.8      .1       0
  5318.4     .05       0
Bank Sta=4992.9,4998.9
XS Rating Curve= 0 ,0
Exp/Cntr=0.3,0.1

Type RM Length L Ch R = 1 ,9710    ,475,475,475
BEGIN DESCRIPTION:
BEST BRANCH 8.0
END DESCRIPTION:
XS GIS Cut Line= 3
      2269187.72     13389896.86      2268787.72     13390096.85
      2268387.73     13390596.84
#Sta/Elev= 30
  4523.5  239.16  4568.2  237.19  4626.9  235.17  4635.3  234.49  4649.3   234.2
  4657.7  233.51  4688.4  232.34  4738.7  230.85  4800.2  228.49  4851.6  227.12
  4895.2  225.55  4948.3  224.73  4962.3   224.2  4967.9  223.61  4973.9  223.61
  4977.9  222.56  4984.3  223.53  4992.3  221.67  4995.7  219.46  4998.5  218.96
  5001.7  219.46  5006.7  221.04  5021.1  223.27  5041.9  223.82  5077.2  223.62
  5138.5  224.67  5240.4  226.99  5440.5  234.46    5483  235.59    5611  239.95
#Mann= 5 ,-1 , 0
  4523.5     .05       0  4851.6      .1       0  4995.7     .07       0
  5001.7      .1       0  5138.5     .05       0
Bank Sta=4995.7,5001.7
XS Rating Curve= 0 ,0
Exp/Cntr=0.3,0.1

Type RM Length L Ch R = 1 ,9235    ,385,385,385
BEGIN DESCRIPTION:
BEST BRANCH 7.0
END DESCRIPTION:
XS GIS Cut Line= 3
      2268887.74     13389396.83      2268487.72     13389796.85
      2268237.72     13390546.87
#Sta/Elev= 30
  4427.3   238.7  4611.2  232.35  4639.5  230.62  4653.6  229.38    4696  228.93
  4738.5  227.49    4802  226.33  4908.2  224.66  4922.3  223.84  4936.4  223.71
  4964.7   222.6  4978.9  220.47  4995.7  220.33  5000.6  217.61  5003.3  217.11
  5006.6  217.61  5014.1  223.44  5024.6  223.66  5042.9  222.76  5056.3  221.93
  5087.9  222.13  5140.6   223.6  5288.2  225.93  5414.7  229.32  5456.8  230.98
  5509.5  232.41  5583.3  235.27  5678.2  238.11  5762.5  240.38  5783.6  240.65
#Mann= 5 ,-1 , 0
  4427.3     .05       0    4802      .1       0  5000.6     .07       0
  5006.6      .1       0  5042.9     .05       0
Bank Sta=5000.6,5006.6
XS Rating Curve= 0 ,0
Exp/Cntr=0.3,0.1

Type RM Length L Ch R = 1 ,8850    ,385,385,385
BEGIN DESCRIPTION:
BEST BRANCH 6.0
END DESCRIPTION:
XS GIS Cut Line= 4
      2268501.14      13389231.8      2268243.74     13389371.53
      2267986.35     13390209.88      2267971.65     13390651.09
#Sta/Elev= 30
  4476.6  239.93  4535.6  238.74  4579.4  237.17  4644.9  233.93  4651.2  233.15
  4696.7  230.65  4764.4  229.58  4809.3  227.94  4874.8  224.59    4885  224.58
  4921.5  222.77  4940.2  222.67  4945.5  223.52  4978.2  221.69  4984.3  219.52
  4994.7  217.42  5002.2   217.4  5004.9   216.9  5008.2   217.4  5010.9  220.82
  5016.2  221.94  5076.4  221.06  5109.1   221.7  5147.4  221.12  5517.5  227.36
    5752  234.41  5763.5  234.24  5833.5  236.39  5983.6  239.78  6087.9   241.4
#Mann= 5 ,-1 , 0
  4476.6     .05       0    4885      .1       0  5002.2     .07       0
  5008.2      .1       0  5147.4     .05       0
Bank Sta=5002.2,5008.2
XS Rating Curve= 0 ,0
Exp/Cntr=0.3,0.1