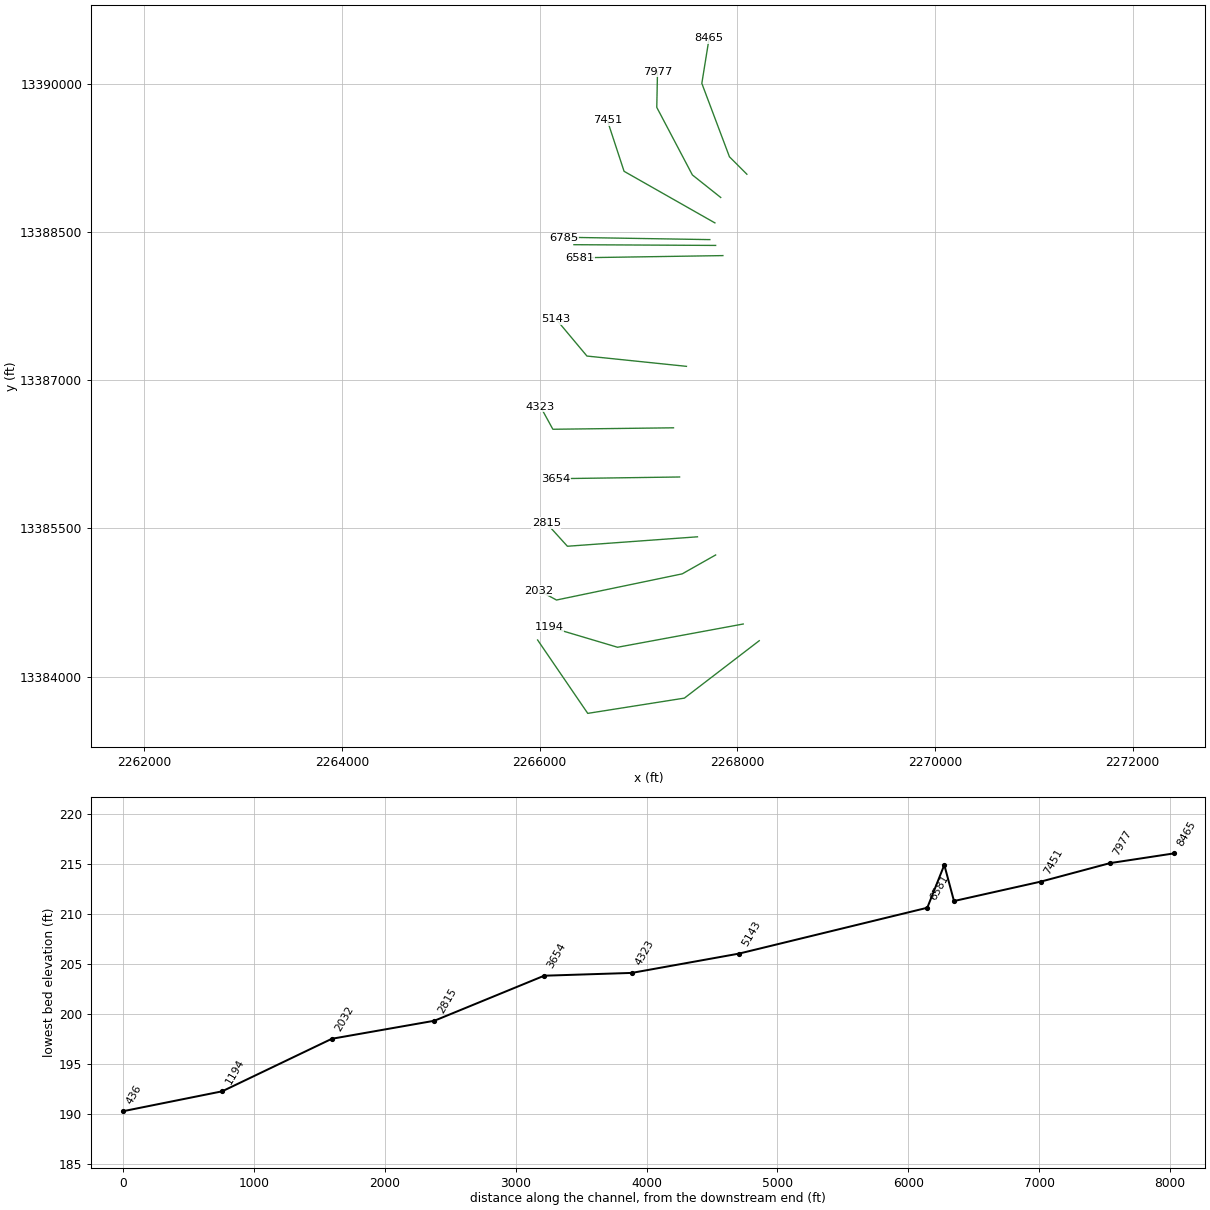
HEC-RAS study BEST BRANCH.prj: BEST BRANCH Base Level Engineering

--- BEST BRANCH.g01 (geometry) --- (continued)

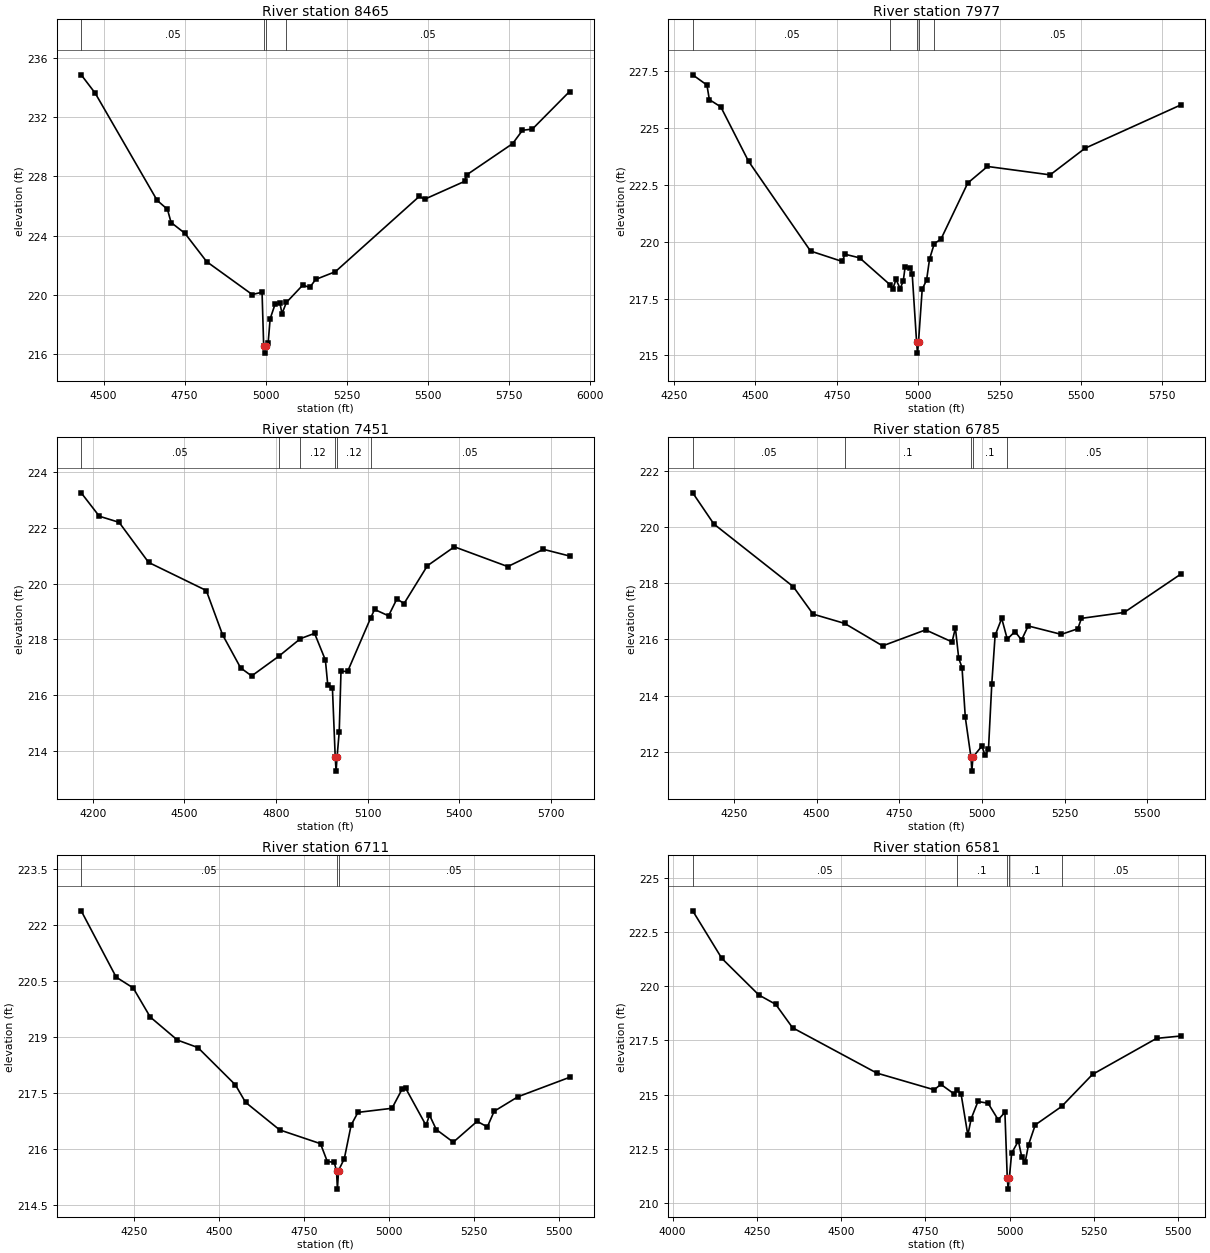
Type RM Length L Ch R = 1 ,8465    ,488,488,488
BEGIN DESCRIPTION:
BEST BRANCH 5.0
END DESCRIPTION:
XS GIS Cut Line= 4
      2268096.64     13389084.75      2267920.17     13389261.22
      2267640.72     13390003.97      2267714.26     13390459.93
#Sta/Elev= 30
  4431.1  234.84  4474.3   233.6  4665.2  226.37  4696.9  225.77  4708.1  224.88
  4750.8  224.15  4817.8  222.24  4958.3  220.02  4988.5  220.18  4993.5  216.57
  4996.3  216.07  4999.5  216.57  5007.2  216.73  5013.4  218.38  5028.6  219.37
  5043.6  219.43    5050  218.74  5063.6  219.49  5114.1  220.66  5135.4   220.5
  5153.8  221.04  5214.3  221.56  5473.1  226.64  5489.6  226.45  5613.2  227.66
    5619  228.09  5760.8   230.2  5791.2   231.1  5821.6  231.18  5936.1  233.71
#Mann= 4 ,-1 , 0
  4431.1     .05       0  4993.5     .07       0  4999.5     .05       0
  5063.6     .05       0
Bank Sta=4993.5,4999.5
XS Rating Curve= 0 ,0
Exp/Cntr=0.3,0.1

Type RM Length L Ch R = 1 ,7977    ,526,526,526
BEGIN DESCRIPTION:
BEST BRANCH 4.0
END DESCRIPTION:
XS GIS Cut Line= 4
      2267831.92      13388849.4      2267545.12     13389077.37
      2267184.78     13389761.29      2267192.13     13390121.61
#Sta/Elev= 30
  4307.4  227.34  4351.1  226.89  4358.5  226.25  4393.7  225.93  4478.8  223.54
  4669.3  219.59    4767  219.13  4774.9  219.45  4820.1  219.29  4913.3  218.11
  4921.8  217.92  4931.9  218.34  4944.5  217.94    4954  218.26  4959.6  218.87
    4976  218.86  4981.6  218.58    4995   215.6  4997.8   215.1    5001   215.6
  5012.3  217.91  5025.7  218.31  5034.9  219.24  5049.5  219.92  5069.8  220.11
  5152.2  222.58  5212.7  223.31  5405.3  222.94  5512.4  224.11  5807.2  226.02
#Mann= 5 ,-1 , 0
  4307.4     .05       0  4913.3     .12       0    4995     .07       0
    5001     .12       0  5049.5     .05       0
Bank Sta=4995,5001
XS Rating Curve= 0 ,0
Exp/Cntr=0.3,0.1

Type RM Length L Ch R = 1 ,7451    ,666,666,666
BEGIN DESCRIPTION:
BEST BRANCH 3.0
END DESCRIPTION:
XS GIS Cut Line= 3
      2267773.11       13388592.      2266853.85     13389114.14
      2266684.69     13389628.96
#Sta/Elev= 30
  4162.3  223.26  4221.5  222.42  4286.4   222.2    4383  220.76  4571.9  219.75
  4625.2  218.16  4684.4  216.97  4720.5  216.68  4809.6  217.39  4880.2  218.02
  4926.6  218.21    4962  217.25  4969.8  216.35    4985  216.25  4994.2  213.76
    4997  213.26  5000.2  213.76  5007.3  214.68  5013.1  216.85  5034.7  216.84
  5110.1  218.76    5123  219.07  5168.8  218.84  5196.2  219.45  5219.5  219.28
    5296  220.64  5384.4  221.32  5559.2  220.61  5675.9  221.23  5761.4  220.99
#Mann= 6 ,-1 , 0
  4162.3     .05       0  4809.6      .1       0  4880.2     .12       0
  4994.2     .07       0  5000.2     .12       0  5110.1     .05       0
Bank Sta=4994.2,5000.2
XS Rating Curve= 0 ,0
Exp/Cntr=0.3,0.1

Type RM Length L Ch R = 1 ,6785    ,74,74,74
BEGIN DESCRIPTION:
Mapping XS 4b3d907e
END DESCRIPTION:
XS GIS Cut Line= 3
      2267721.62     13388422.87      2266361.14     13388444.94
      2266246.39     13388434.31
#Sta/Elev= 30
  4125.7  221.22  4189.6  220.11  4429.6  217.88  4489.6   216.9  4584.9  216.57
  4699.7  215.77  4829.7  216.34  4909.7  215.91  4919.7  216.41  4929.7  215.33
  4939.7     215  4949.7  213.22  4966.7  211.81  4969.5  211.31  4972.7  211.81
  4999.7   212.2  5009.7  211.87  5019.7  212.09  5029.7  214.42  5039.7  216.14
  5059.7  216.75  5076.5  216.01  5099.7  216.28  5119.7  215.98  5139.7  216.48
  5239.7  216.18  5289.8  216.38  5300.6  216.75  5429.8  216.96  5601.6  218.33
#Mann= 5 ,-1 , 0
  4125.7     .05       0  4584.9      .1       0  4966.7     .07       0
  4972.7      .1       0  5076.5     .05       0
Bank Sta=4966.7,4972.7
XS Rating Curve= 0 ,0
Exp/Cntr=0.3,0.1

Type RM Length L Ch R = 1 ,6711    ,130,130,130
BEGIN DESCRIPTION:
Mapping XS fdfb4f5d
END DESCRIPTION:
XS GIS Cut Line= 2
      2267780.46     13388364.04      2266346.38      13388371.4
#Sta/Elev= 30
  4095.6  222.39  4198.3  220.61  4248.3  220.32  4298.3  219.54  4378.3  218.92
  4438.3  218.72  4548.3  217.72  4578.3  217.25  4678.4  216.51  4798.4  216.14
  4818.4  215.66  4838.4  215.64  4845.4  215.42  4848.1  214.92  4851.4  215.42
  4868.4  215.74  4888.4  216.64  4908.4  216.98  5008.4  217.09  5038.4  217.61
  5048.4  217.63  5108.4  216.63  5118.4  216.91  5138.4  216.52  5188.4  216.18
  5258.4  216.74  5288.4  216.59  5308.4  217.01  5378.4   217.4  5529.7  217.92
#Mann= 3 ,-1 , 0
  4095.6     .05       0  4845.4     .04       0  4851.4     .05       0
Bank Sta=4845.4,4851.4
XS Rating Curve= 0 ,0
Exp/Cntr=0.3,0.1

Type RM Length L Ch R = 1 ,6581    ,1438,1438,1438
BEGIN DESCRIPTION:
BEST BRANCH 2.0
END DESCRIPTION:
XS GIS Cut Line= 2
        2267854.     13388261.09      2266405.27     13388239.03
#Sta/Elev= 30
  4059.9  223.47  4146.2  221.28  4256.2  219.59  4306.2  219.16  4356.2  218.08
  4606.2  215.99  4776.3  215.22  4796.3  215.47  4836.3  215.02  4842.7  215.22
  4856.3  215.02  4876.3  213.13  4886.3  213.89  4906.3  214.68  4936.3   214.6
  4966.3  213.84  4986.3  214.18  4993.3  211.14    4996  210.64  4999.3  211.14
  5006.3   212.3  5026.3  212.86  5036.3  212.12  5046.3  211.88  5056.3  212.68
  5076.3   213.6  5154.5  214.45  5246.3  215.93  5436.3  217.59  5508.8   217.7
#Mann= 5 ,-1 , 0
  4059.9     .05       0  4842.7      .1       0  4993.3     .07       0
  4999.3      .1       0  5154.5     .05       0
Bank Sta=4993.3,4999.3
XS Rating Curve= 0 ,0
Exp/Cntr=0.3,0.1

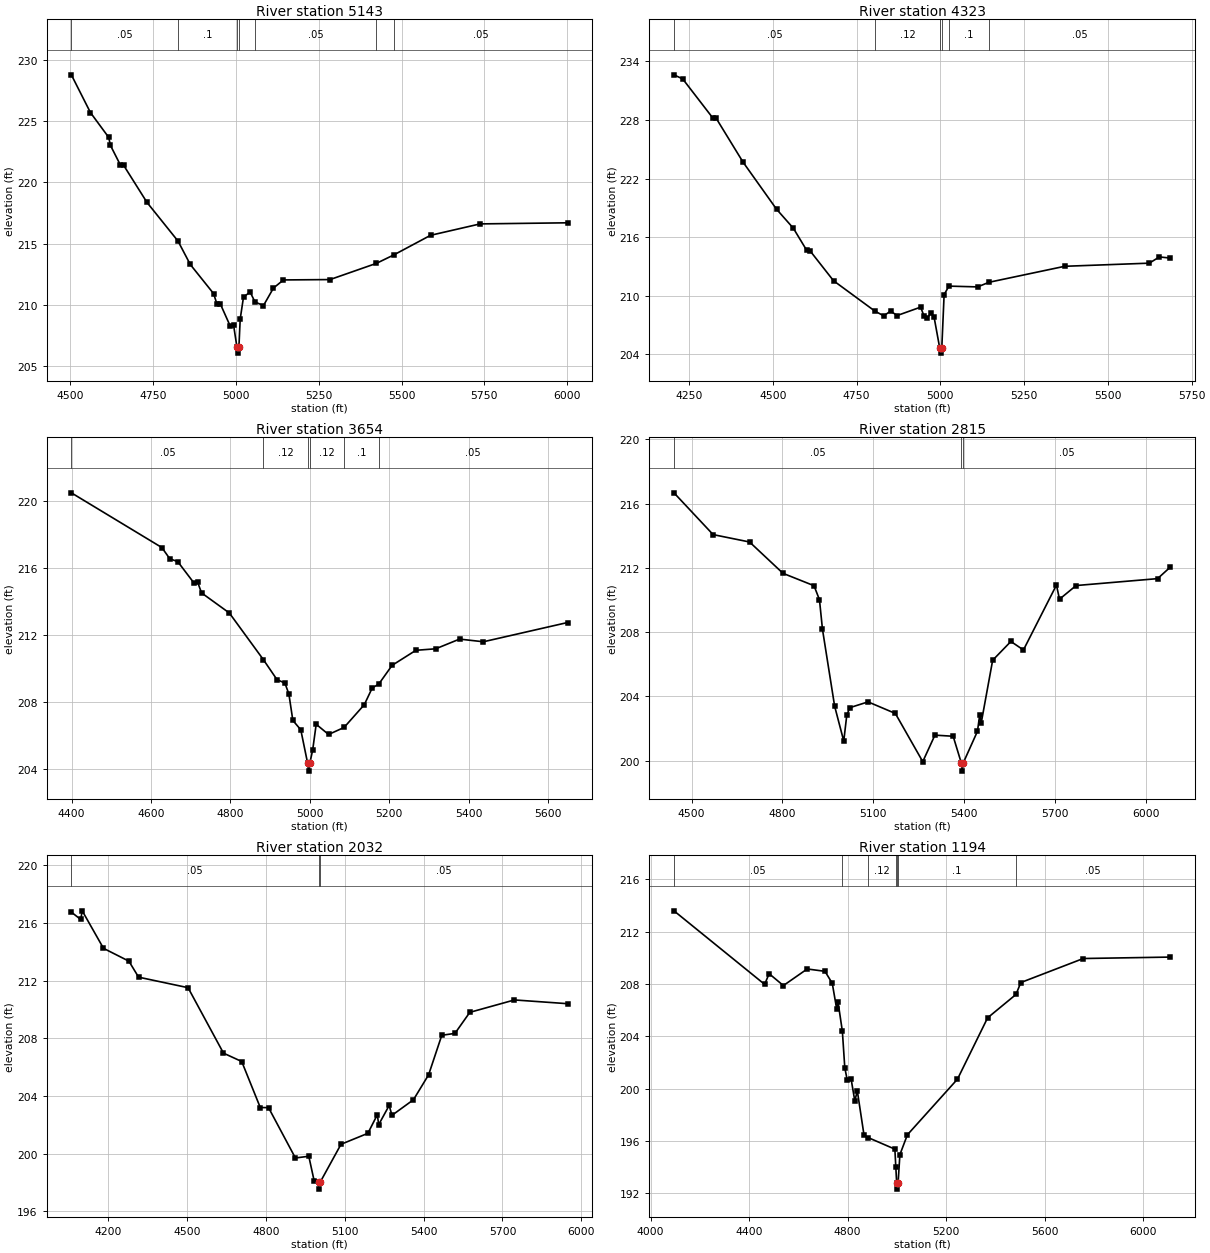
Type RM Length L Ch R = 1 ,5143    ,820,820,820
BEGIN DESCRIPTION:
Mapping XS 224e9544
END DESCRIPTION:
XS GIS Cut Line= 3
      2267485.09     13387140.27      2266478.18     13387244.43
      2266165.67      13387617.7
#Sta/Elev= 30
  4502.6  228.76  4560.3  225.68  4615.4  223.66  4620.6  223.01  4650.8   221.4
  4660.8  221.37  4731.2  218.35  4824.8   215.2  4861.9  213.29  4932.2  210.92
  4942.3  210.08  4952.4  210.09  4982.5  208.27  4992.6  208.36  5002.8  206.56
  5005.5  206.06  5008.8  206.56  5012.7  208.84  5022.7  210.64  5042.8  211.04
  5057.4  210.23    5083  209.94  5113.2  211.37  5143.4  212.03  5284.1  212.06
    5424  213.38  5476.7  214.07  5587.7  215.67  5737.4   216.6  6001.7  216.69
#Mann= 7 ,-1 , 0
  4502.6     .05       0  4824.8      .1       0  5002.8     .07       0
  5008.8      .1       0  5057.4     .05       0    5424      .1       0
  5476.7     .05       0
Bank Sta=5002.8,5008.8
XS Rating Curve= 0 ,0
Exp/Cntr=0.3,0.1

Type RM Length L Ch R = 1 ,4323    ,669,669,669
BEGIN DESCRIPTION:
Mapping XS 3bf5d56d
END DESCRIPTION:
XS GIS Cut Line= 3
      2267353.87     13386518.21      2266133.16      13386503.5
      2266008.14     13386731.48
#Sta/Elev= 30
  4205.1  232.62  4231.2   232.2  4321.3  228.19  4331.3  228.16  4411.3  223.68
  4511.3  218.86  4561.3  216.92  4601.3  214.65  4611.3   214.6  4681.3  211.54
  4805.6  208.41  4831.3  207.95  4851.3  208.43  4871.3  207.98  4941.3  208.84
  4951.3  207.92  4961.3  207.69  4971.3  208.25  4981.3  207.83  4998.3  204.63
  5001.1  204.13  5004.3  204.63  5011.3  210.12  5025.6  210.99  5111.3  210.91
  5144.9  211.38  5371.3  213.02  5623.6  213.34  5653.8  213.98  5685.9  213.86
#Mann= 6 ,-1 , 0
  4205.1     .05       0  4805.6     .12       0  4998.3     .07       0
  5004.3     .12       0  5025.6      .1       0  5144.9     .05       0
Bank Sta=4998.3,5004.3
XS Rating Curve= 0 ,0
Exp/Cntr=0.3,0.1

Type RM Length L Ch R = 1 ,3654    ,839,839,839
BEGIN DESCRIPTION:
Mapping XS 41fd388e
END DESCRIPTION:
XS GIS Cut Line= 2
      2267415.67     13386020.47      2266165.69     13386003.11
#Sta/Elev= 30
  4399.3  220.48  4627.3  217.21  4647.3  216.54  4667.3  216.37  4707.3  215.12
  4717.3  215.15  4727.3   214.5  4797.3   213.3  4882.8  210.52  4917.3  209.32
  4937.3  209.11  4947.3  208.46  4957.3  206.88  4977.3  206.32  4994.3  204.35
  4997.1  203.85  5000.3  204.35  5007.3  205.12  5016.1  206.65  5047.3  206.04
  5086.4  206.46  5137.3  207.82  5157.3  208.82  5173.7  209.05  5207.3  210.17
  5267.3  211.07  5317.3  211.16  5377.3  211.74  5437.3  211.58  5649.4  212.73
#Mann= 6 ,-1 , 0
  4399.3     .05       0  4882.8     .12       0  4994.3     .07       0
  5000.3     .12       0  5086.4      .1       0  5173.7     .05       0
Bank Sta=4994.3,5000.3
XS Rating Curve= 0 ,0
Exp/Cntr=0.3,0.1

Type RM Length L Ch R = 1 ,2815    ,783,783,783
BEGIN DESCRIPTION:
Mapping XS 1aca902a
END DESCRIPTION:
XS GIS Cut Line= 3
      2267596.55     13385415.12      2266280.24     13385319.52
      2266066.95     13385554.87
#Sta/Elev= 30
  4442.1  216.67  4571.3  214.07  4691.6  213.61  4801.9  211.66  4904.2  210.89
  4922.2  210.02  4932.2  208.17  4972.3  203.39  5002.4  201.22  5012.4  202.84
  5022.5   203.3  5082.6  203.66  5172.6  202.94  5263.1  199.94  5303.2  201.59
  5363.4  201.52  5390.4  199.85  5393.2  199.35  5396.4  199.85  5443.6  201.83
    5451  202.85    5456  202.35  5493.7  206.25  5553.9  207.42  5595.3  206.89
  5704.2  210.93  5714.3  210.05  5769.1   210.9    6038  211.33  6079.5  212.04
#Mann= 3 ,-1 , 0
  4442.1     .05       0  5390.4     .03       0  5396.4     .05       0
Bank Sta=5390.4,5396.4
XS Rating Curve= 0 ,0
Exp/Cntr=0.3,0.1

Type RM Length L Ch R = 1 ,2032    ,838,838,838
BEGIN DESCRIPTION:
Mapping XS 56b23e87
END DESCRIPTION:
XS GIS Cut Line= 4
      2267780.45     13385231.28      2267442.16     13385040.07
      2266169.93     13384775.33      2265993.43     13384870.93
#Sta/Elev= 30
  4058.9  216.76  4094.6  216.25  4100.3  216.85  4181.2  214.25  4277.9  213.36
  4314.8  212.25  4503.1  211.52    4638  206.98  4707.4   206.4    4778  203.21
  4809.5   203.2  4911.7  199.71  4962.7  199.83  4983.5  198.09  5000.6  198.05
  5003.3  197.55  5006.6  198.05  5085.3  200.66  5187.5  201.42  5223.6  202.71
  5228.7  202.02  5268.6  203.35  5279.4  202.67  5361.1  203.75  5418.8  205.48
  5468.9  208.22    5519  208.35  5575.6  209.81  5745.5  210.67  5947.7  210.41
#Mann= 3 ,-1 , 0
  4058.9     .05       0  5000.6     .03       0  5006.6     .05       0
Bank Sta=5000.6,5006.6
XS Rating Curve= 0 ,0
Exp/Cntr=0.3,0.1

Type RM Length L Ch R = 1 ,1194    ,758,758,758
BEGIN DESCRIPTION:
Mapping XS 2d857cd2
END DESCRIPTION:
XS GIS Cut Line= 3
      2268059.89     13384532.65      2266787.66     13384297.32
      2266096.39     13384503.23
#Sta/Elev= 30
  4095.1   213.6  4463.4  207.97  4481.5  208.79  4539.5  207.88  4636.3  209.15
  4708.4  208.97    4738  208.05  4756.2  206.06  4761.3  206.63    4779  204.38
  4788.8   201.6    4799  200.62  4814.2  200.76  4829.5  199.05  4839.7  199.82
  4867.1  196.41  4884.2  196.24  4992.2  195.36    4996  194.01  4999.4   192.8
  5002.2   192.3  5005.4   192.8  5012.6  194.94  5043.1  196.46  5246.5  200.72
  5368.8  205.41  5484.1   207.2  5503.6  208.11  5757.2  209.95  6110.2  210.06
#Mann= 7 ,-1 , 0
  4095.1     .05       0    4779      .1       0  4884.2     .12       0
    4996      .1       0  4999.4     .07       0  5005.4      .1       0
  5484.1     .05       0
Bank Sta=4999.4,5005.4
XS Rating Curve= 0 ,0
Exp/Cntr=0.3,0.1

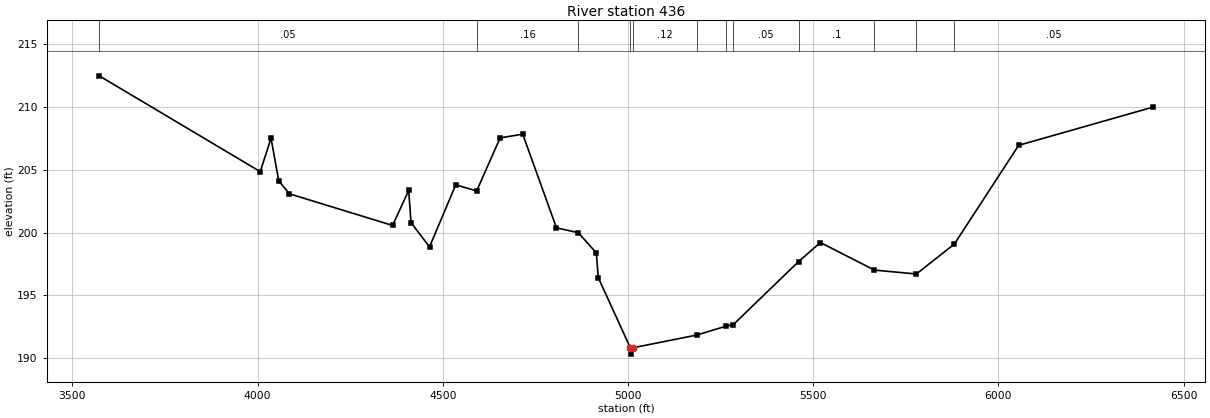
Type RM Length L Ch R = 1 ,436     ,0,0,0
BEGIN DESCRIPTION:
BEST BRANCH 1.0
END DESCRIPTION:
XS GIS Cut Line= 4
      2268221.64     13384363.48      2267464.22     13383782.55
      2266486.15     13383628.11      2265978.71     13384370.89
#Sta/Elev= 30
  3572.6   212.5  4007.4  204.86  4036.4  207.53  4057.3  204.12  4086.3  203.09
  4364.6  200.57  4408.1  203.36  4414.4   200.8  4464.3  198.86  4535.2  203.81
  4591.6  203.32    4655  207.55    4716  207.85  4807.1  200.38  4866.1  199.99
  4914.8  198.38  4919.9  196.41  5006.6  190.81  5009.3  190.31  5012.6  190.81
  5185.7  191.83    5265  192.54  5284.7  192.67  5460.8  197.69  5519.6  199.21
  5665.5  197.01  5778.8   196.7  5881.4  199.09    6055  206.96  6416.9     210
#Mann= 12 ,-1 , 0
  3572.6     .05       0  4591.6     .16       0  4866.1     .12       0
  5006.6     .07       0  5012.6     .12       0  5185.7      .1       0
    5265     .12       0  5284.7     .05       0  5460.8      .1       0
  5665.5     .05       0  5778.8      .1       0  5881.4     .05       0
Bank Sta=5006.6,5012.6
XS Rating Curve= 0 ,0
Exp/Cntr=0.3,0.1

Chan Stop Cuts=-1
Use User Specified Reach Order=0
Composite Channel Slope=5