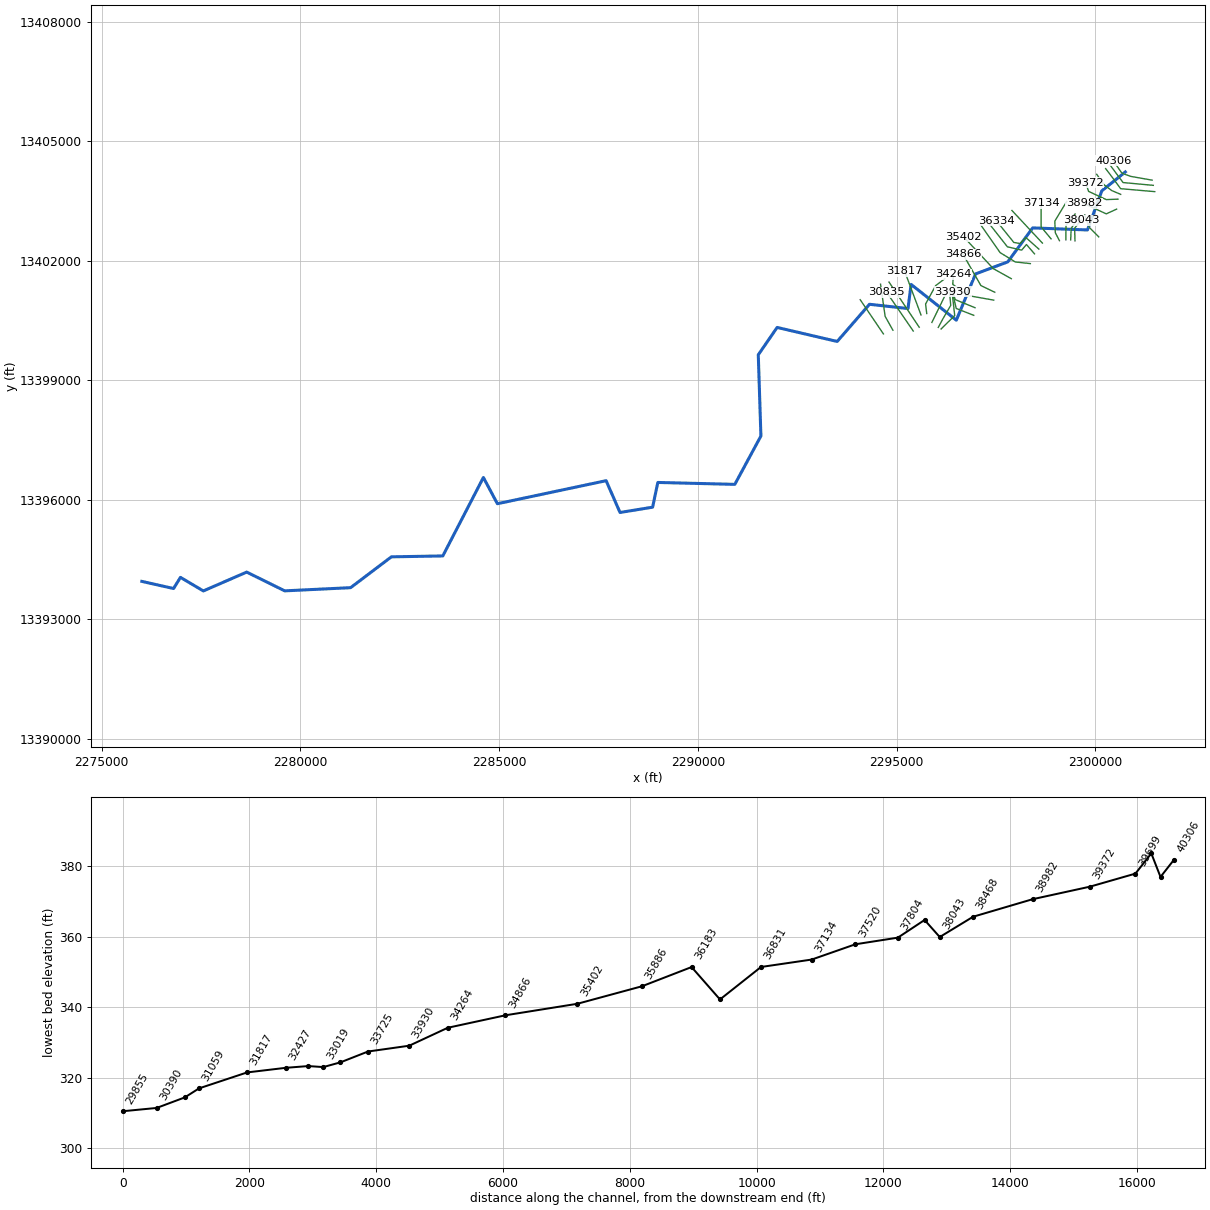
--- EAST FORK SALT CREEK.prj (project) ---

Proj Title=EAST FORK SALT CREEK Base Level Engineering
Current Plan=p01
Default Exp/Contr=0.3,0.1
English Units
Geom File=g01
Flow File=f01
Plan File=p01
Y Axis Title=Elevation
X Axis Title(PF)=Main Channel Distance
X Axis Title(XS)=Station
BEGIN DESCRIPTION:
EAST FORK SALT CREEK
END DESCRIPTION:
DSS Export Rating Curves= 0
DSS Export Rating Curve Sorted= 0
DSS Export Volume Flow Curves= 0
DXF OffsetX= 0
DXF OffsetY= 0
DXF ScaleX= 1
DXF ScaleY= 10

--- EAST FORK SALT CREEK.p01 (plan) ---

Plan Title=Multiple Run
Short Identifier=Multiple
Geom File=g01
Flow File=f01
Subcritical Flow
K Sum by GR= 0
Std Step Tol= 0.01
Critical Tol= 0.01
Num of Std Step Trials= 20
Max Error Tol= 0.3
Flow Tol Ratio= 0.001
Split Flow NTrial= 30
Split Flow Tol= 0.02
Split Flow Ratio= 0.02
Log Output Level= 0
Friction Slope Method= 1
Unsteady Friction Slope Method= 2
Unsteady Bridges Friction Slope Method= 1
Parabolic Critical Depth
Global Vel Dist=  1 , 1 , 1
Global Log Level= 0
CheckData=True
Encroach Param= -1, 0, 0, 0
BEGIN DESCRIPTION:
Multiple Run
END DESCRIPTION:

--- EAST FORK SALT CREEK.f01 (steady flow) ---

Flow Title=Multiple
Program Version=4.10
Number of Profiles= 7
Profile Names=10-year,25-year,50-year,1pct_min,100-year,1pct_plu,500-year
River Rch & RM=EAST FORK SALT C,Reach-1         ,40306
     664     945    1182    1080    1461    1975    2238
River Rch & RM=EAST FORK SALT C,Reach-1         ,33291
    1802    2702    3501    3302    4466    6040    7305
River Rch & RM=EAST FORK SALT C,Reach-1         ,33019
    1802    2702    3501    3302    4466    6040    7305
River Rch & RM=EAST FORK SALT C,Reach-1         ,30835
    1750    2611    3372    3169    4286    5797    6961
River Rch & RM=EAST FORK SALT C,Reach-1         ,27293
    2118    3187    4138    3910    5287    7151    8675
River Rch & RM=EAST FORK SALT C,Reach-1         ,26308
    2118    3187    4138    3910    5287    7151    8675
River Rch & RM=EAST FORK SALT C,Reach-1         ,25131
    2372    3570    4637    4379    5922    8008    9711
River Rch & RM=EAST FORK SALT C,Reach-1         ,15894
    2317    3481    4515    4257    5757    7786    9417
River Rch & RM=EAST FORK SALT C,Reach-1         ,14337
    2257    3389    4394    4145    5605    7580    9179
River Rch & RM=EAST FORK SALT C,Reach-1         ,12187
    2257    3389    4394    4145    5605    7580    9179
River Rch & RM=EAST FORK SALT C,Reach-1         ,10103
    2346    3528    4580    4327    5851    7913    9622
River Rch & RM=EAST FORK SALT C,Reach-1         ,4414
    2276    3412    4421    4169    5638    7624    9240
Boundary for River Rch & Prof#=EAST FORK SALT C,Reach-1         , 1
Up Type= 0
Dn Type= 3
Dn Slope=0.00563
Boundary for River Rch & Prof#=EAST FORK SALT C,Reach-1         , 2
Up Type= 0
Dn Type= 3
Dn Slope=0.00563
Boundary for River Rch & Prof#=EAST FORK SALT C,Reach-1         , 3
Up Type= 0
Dn Type= 3
Dn Slope=0.00563
Boundary for River Rch & Prof#=EAST FORK SALT C,Reach-1         , 4
Up Type= 0
Dn Type= 3
Dn Slope=0.00563
Boundary for River Rch & Prof#=EAST FORK SALT C,Reach-1         , 5
Up Type= 0
Dn Type= 3
Dn Slope=0.00563
Boundary for River Rch & Prof#=EAST FORK SALT C,Reach-1         , 6
Up Type= 0
Dn Type= 3
Dn Slope=0.00563
Boundary for River Rch & Prof#=EAST FORK SALT C,Reach-1         , 7
Up Type= 0
Dn Type= 3
Dn Slope=0.00563
DSS Import GetInterval= 0
DSS Import GetPeak= 0
DSS Import FillOption= 0

--- EAST FORK SALT CREEK.g01 (geometry) ---

Geom Title=Existing Conditions
Program Version=4.10

River Reach=EAST FORK SALT C,Reach-1
Reach XY= 30
      2300757.72     13404226.86      2300165.82       13403753.
      2299804.35     13402770.33      2298425.07     13402821.55
      2297798.99     13401968.44      2296987.25     13401665.81
      2296504.46     13400505.01      2295365.94     13401402.39
      2295287.65     13400796.98      2294318.89     13400904.04
      2293506.16     13399970.41      2291994.79     13400322.58
       2291520.4     13399635.75      2291586.85     13397596.82
      2290930.31     13396382.61      2288992.38     13396430.66
      2288861.49      13395809.9      2288041.07     13395676.63
      2287691.76     13396475.07      2284955.81     13395896.54
      2284602.98     13396555.45      2283582.04     13394585.77
      2282288.49     13394563.14       2281261.9     13393788.83
      2279603.57     13393709.04      2278646.81     13394180.09
      2277555.67       13393707.      2276980.15     13394047.97
      2276807.23     13393767.76      2276007.72     13393946.85

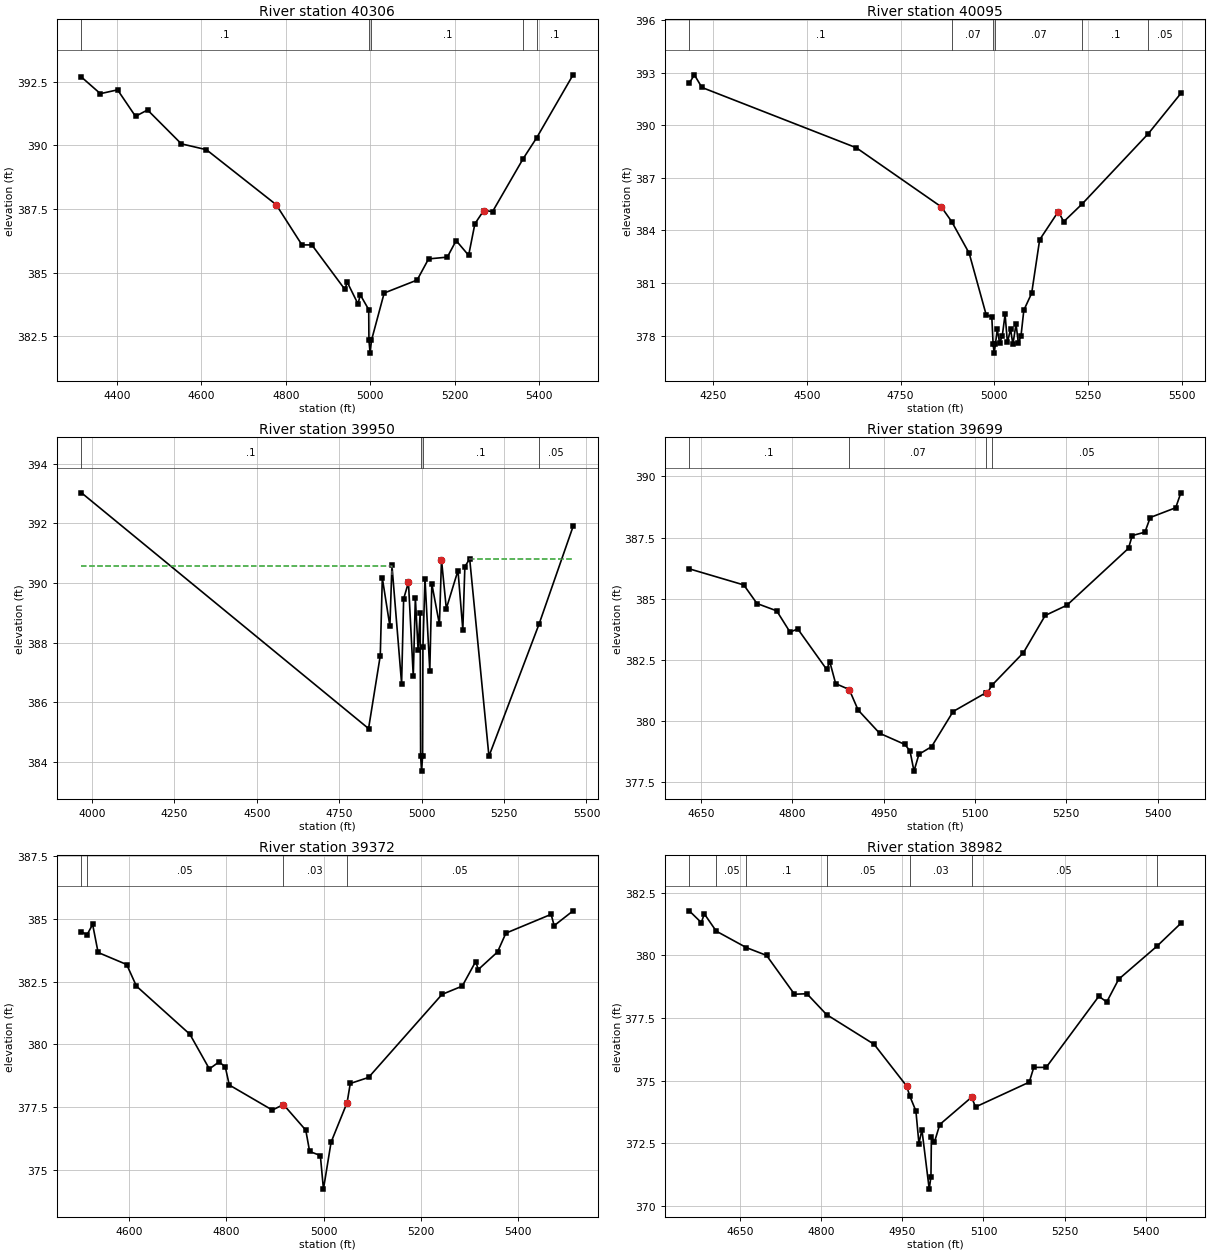
Type RM Length L Ch R = 1 ,40306   ,211,211,211
BEGIN DESCRIPTION:
EAST FORK SALT CREEK 49.0
END DESCRIPTION:
XS GIS Cut Line= 4
      2301431.79     13404020.22      2300896.53     13404114.45
      2300672.62     13404193.37      2300452.56     13404506.96
#Sta/Elev= 30
  4316.4  392.68  4361.1  392.03  4401.8  392.18  4444.3  391.14  4472.8  391.39
  4552.8  390.06  4612.1  389.83  4777.4  387.67  4838.4  386.09  4861.9  386.09
  4940.2  384.34  4945.5  384.63  4971.2  383.77  4976.5  384.13  4996.5  383.55
    4997  382.34  4999.8  381.84    5003  382.34  5033.1   384.2  5111.1  384.71
  5138.2  385.54  5182.6  385.61  5203.5  386.26  5233.1  385.68  5247.9  386.92
  5268.8  387.44  5289.8   387.4  5362.3  389.48  5394.3   390.3  5480.4  392.77
#Mann= 5 ,-1 , 0
  4316.4      .1       0    4997     .07       0    5003      .1       0
  5362.3     .05       0  5394.3      .1       0
Bank Sta=4777.4,5268.8
XS Rating Curve= 0 ,0
Exp/Cntr=0.3,0.1

Type RM Length L Ch R = 1 ,40095   ,145,145,145
BEGIN DESCRIPTION:
Mapping XS d372567d
END DESCRIPTION:
XS GIS Cut Line= 3
       2301461.3     13403890.02      2300700.15     13403960.28
      2300373.47     13404398.92
#Sta/Elev= 30
  4186.4   392.4    4200  392.88  4220.1  392.16  4631.9  388.72  4858.5  385.35
  4886.3  384.51  4933.1   382.7  4978.8  379.16  4993.4  379.09    4997   377.5
  4999.8     377    5003   377.5    5008  378.35  5014.3  377.59  5021.3  377.97
  5028.9  379.21  5035.1  377.61  5043.5  378.37  5049.7   377.5  5058.1  378.66
  5064.3  377.57  5071.2  377.96  5078.9  379.45  5099.8  380.42  5121.1  383.47
  5170.9  385.08  5185.3   384.5  5234.8  385.52  5410.8  389.52  5497.7  391.82
#Mann= 6 ,-1 , 0
  4186.4      .1       0  4886.3     .07       0    4997     .07       0
    5003     .07       0  5234.8      .1       0  5410.8     .05       0
Bank Sta=4858.5,5170.9
XS Rating Curve= 0 ,0
Exp/Cntr=0.3,0.1

Type RM Length L Ch R = 1 ,39950   ,251,251,251
BEGIN DESCRIPTION:
Mapping XS bee222fd
END DESCRIPTION:
XS GIS Cut Line= 4
      2301497.77     13403732.03      2300639.59     13403806.12
      2300386.31     13404147.49      2300262.12     13404310.03
#Sta/Elev= 30
  3968.4  393.03  4839.1  385.11  4874.6  387.56  4880.8  390.17  4903.8  388.55
    4910  390.59  4939.3  386.62  4945.5  389.47  4960.1  390.02  4974.7  386.87
    4981  389.51  4989.3  387.75  4995.6  388.99    4997  384.18  4999.8  383.68
    5003  384.18    5004  387.84  5010.2  390.15  5024.8  387.06    5031  389.97
    5054  388.61  5060.3  390.78  5074.9  389.14  5110.3  390.42    5125  388.43
  5131.2  390.55  5145.8  390.81  5204.2  384.18  5356.2  388.62  5459.4   391.9
#Mann= 4 ,-1 , 0
  3968.4      .1       0    4997     .07       0    5003      .1       0
  5356.2     .05       0
#XS Ineff= 2 , 0
       0 4909.04  390.58 5144.81       0  390.81
Permanent Ineff=
       T       T
Bank Sta=4960.1,5060.3
XS Rating Curve= 0 ,0
Exp/Cntr=0.3,0.1

Type RM Length L Ch R = 1 ,39699   ,718,718,718
BEGIN DESCRIPTION:
Mapping XS 8da5ba07
END DESCRIPTION:
XS GIS Cut Line= 4
      2300640.25     13403663.81      2300414.52     13403759.31
      2300219.21     13403906.88       2300036.9     13404167.33
#Sta/Elev= 30
  4630.5  386.22  4720.1  385.56  4741.8   384.8  4774.2   384.5  4796.1  383.63
  4808.8  383.76  4856.1  382.11  4861.6   382.4  4871.1  381.52  4893.4  381.28
    4908  380.44  4943.3  379.49    4985  379.03  4993.3  378.76  4999.8  377.94
  5007.9  378.63  5028.7  378.94  5064.1  380.38  5118.2  381.15  5120.4  381.15
  5128.1  381.46  5179.7  382.79  5215.4  384.31  5251.1  384.73  5352.3  387.06
  5358.4  387.58  5379.3  387.72    5388  388.32  5429.9  388.72  5438.3  389.33
#Mann= 4 ,-1 , 0
  4630.5      .1       0  4893.4     .07       0  5118.2      .1       0
  5128.1     .05       0
Bank Sta=4893.4,5120.4
XS Rating Curve= 0 ,0
Exp/Cntr=0.3,0.1

Type RM Length L Ch R = 1 ,39372   ,904,904,904
BEGIN DESCRIPTION:
EAST FORK SALT CREEK 48.0
END DESCRIPTION:
XS GIS Cut Line= 4
      2300570.65     13403542.99      2300277.69     13403532.14
      2299832.82      13403738.3      2299757.46     13403953.61
#Sta/Elev= 30
  4501.9  384.49  4513.2  384.36  4524.8  384.78  4536.1  383.66  4594.9  383.18
  4614.9  382.32    4725   380.4    4765  379.02    4785   379.3  4797.8   379.1
    4806  378.38  4894.6  377.38  4917.5   377.6  4963.4  376.58  4971.4  375.73
  4993.4  375.57  4999.8  374.23  5015.5   376.1  5048.5  377.68    5055  378.44
  5092.6  378.68  5243.8  381.99  5285.4  382.32  5313.1   383.3  5318.4  382.98
    5358  383.68  5375.2  384.43  5468.3  385.18  5474.6  384.73  5513.5  385.32
#Mann= 4 ,-1 , 0
  4501.9      .1       0  4513.2     .05       0  4917.5     .03       0
  5048.5     .05       0
Bank Sta=4917.5,5048.5
XS Rating Curve= 0 ,0
Exp/Cntr=0.3,0.1

Type RM Length L Ch R = 1 ,38982   ,939,939,939
BEGIN DESCRIPTION:
EAST FORK SALT CREEK 47.0
END DESCRIPTION:
XS GIS Cut Line= 3
      2300538.11     13403293.42      2300277.69     13403174.06
      2299713.45     13403434.48
#Sta/Elev= 30
  4556.6  381.78  4578.9  381.31  4584.4  381.66  4606.4  380.97  4662.3  380.31
  4699.4     380  4750.9  378.45  4773.9  378.47  4810.1  377.64  4898.1  376.45
  4957.9  374.79  4964.2  374.37  4975.2  373.79  4980.8  372.49  4986.3  373.04
  4999.8  370.67    5003  371.17  5003.8  372.75  5009.3  372.54  5019.3  373.25
  5078.1  374.34  5085.3  373.95  5184.5  374.94  5192.9  375.53  5215.8  375.53
  5313.1  378.37  5327.6  378.14  5349.7  379.05    5420  380.36  5464.5  381.28
#Mann= 7 ,-1 , 0
  4556.6      .1       0  4606.4     .05       0  4662.3      .1       0
  4810.1     .05       0  4964.2     .03       0  5078.1     .05       0
    5420      .1       0
Bank Sta=4957.9,5078.1
XS Rating Curve= 0 ,0
Exp/Cntr=0.3,0.1

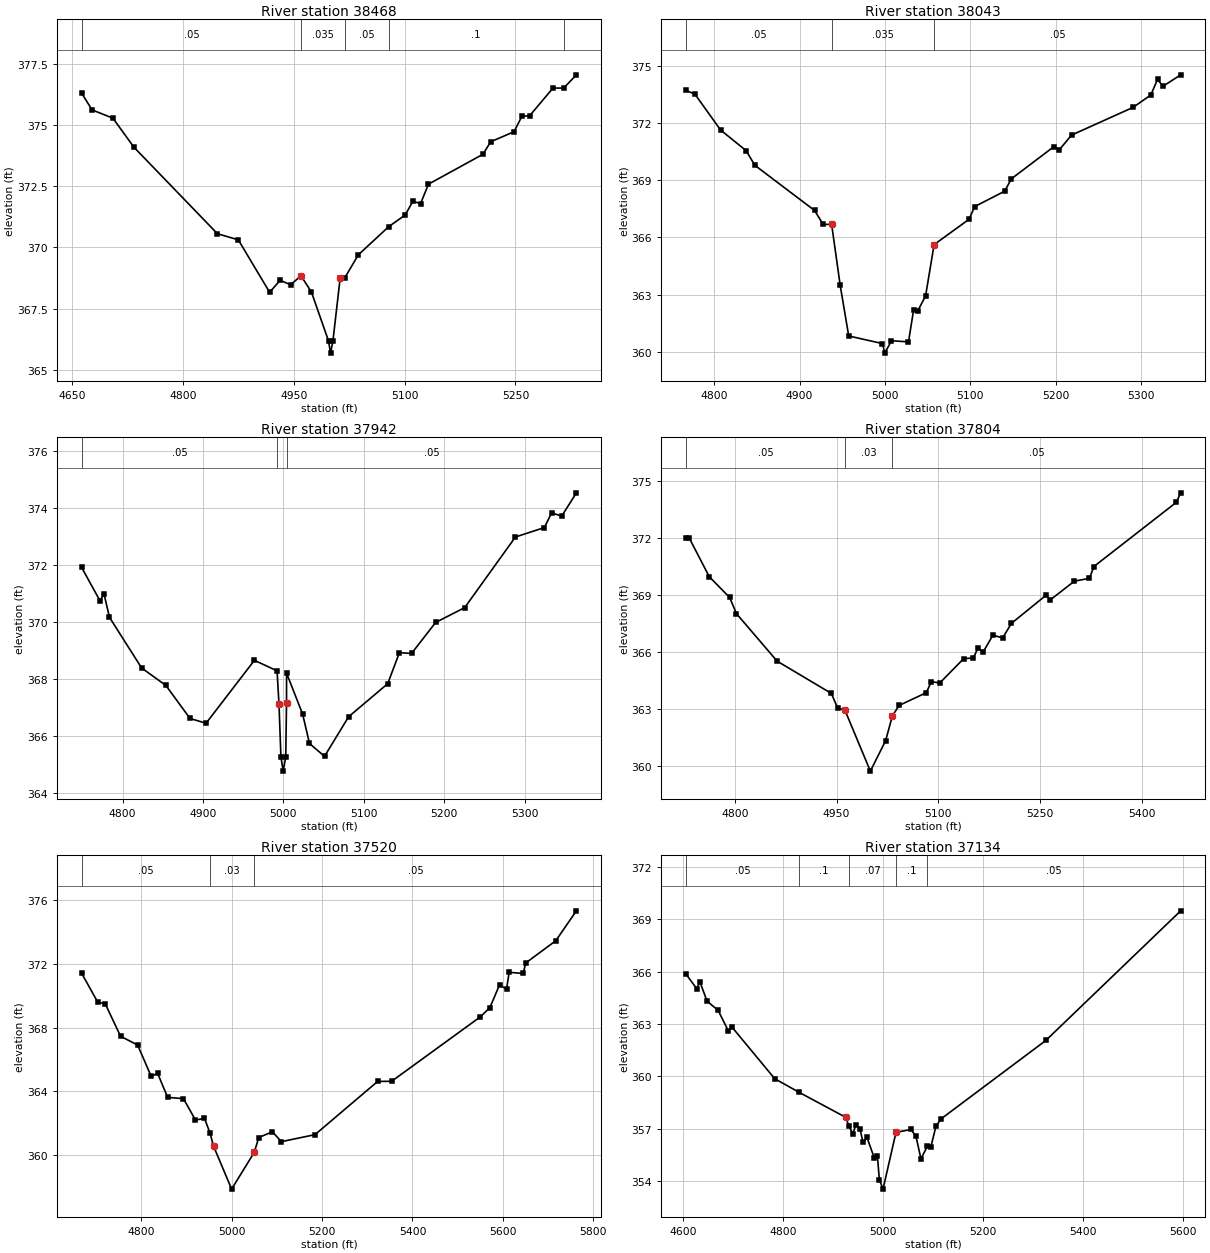
Type RM Length L Ch R = 1 ,38468   ,526,526,526
BEGIN DESCRIPTION:
EAST FORK SALT CREEK 46.0
END DESCRIPTION:
XS GIS Cut Line= 3
       2300087.7     13402596.87      2299837.72     13402846.85
      2299737.71      13403146.9
#Sta/Elev= 30
  4662.8  376.29  4676.9  375.61  4705.2  375.27  4733.5  374.09  4846.6  370.56
  4874.9  370.31  4917.3  368.17  4931.5  368.66  4945.6  368.48  4959.8  368.84
  4973.9  368.18    4997  366.19  4999.8  365.69    5003  366.19  5012.8  368.76
    5019  368.76  5037.4   369.7  5078.6  370.85  5100.7  371.32  5111.2  371.88
  5121.7  371.79  5132.3  372.58  5206.1   373.8  5216.6  374.31  5248.2  374.72
  5258.8  375.35  5269.3  375.37  5300.9   376.5  5315.4   376.5  5332.6  377.04
#Mann= 5 ,-1 , 0
  4662.8     .05       0  4959.8    .035       0    5019     .05       0
  5078.6      .1       0  5315.4     .05       0
Bank Sta=4959.8,5012.8
XS Rating Curve= 0 ,0
Exp/Cntr=0.3,0.1

Type RM Length L Ch R = 1 ,38043   ,239,239,239
BEGIN DESCRIPTION:
Mapping XS 12f678e1
END DESCRIPTION:
XS GIS Cut Line= 3
      2299490.04     13402496.33      2299481.36     13402813.13
      2299646.33     13403017.16
#Sta/Elev= 30
  4766.9   373.7  4777.4  373.51  4807.4  371.63  4837.5  370.54  4847.5  369.78
  4917.5  367.41  4927.5  366.68  4937.5  366.68  4947.5  363.49  4957.5  360.83
    4997  360.43  4999.8  359.93  5007.5  360.58  5027.5  360.52  5033.4  362.17
  5038.4  362.15  5047.5  362.93  5057.5  365.62  5098.5  366.95  5104.9  367.61
  5140.1  368.42    5148  369.07  5197.6  370.75  5204.3   370.6  5218.4  371.36
  5290.3  372.81  5311.2  373.46  5319.1  374.28  5325.5  373.92  5346.2  374.52
#Mann= 3 , 0 , 0
  4766.9     .05       0  4937.5    .035       0  5057.5     .05       0
Bank Sta=4937.5,5057.5
XS Rating Curve= 0 ,0
Exp/Cntr=0.3,0.1

Type RM Length L Ch R = 1 ,37942   ,422,422,422
BEGIN DESCRIPTION:
EAST FORK SALT CREEK 45.0
END DESCRIPTION:
XS GIS Cut Line= 3
      2299381.54      13402522.3      2299394.56     13402808.79
      2299576.73     13403082.05
#Sta/Elev= 30
  4749.2  371.92    4772  370.75    4777  370.99  4783.8  370.17  4823.8  368.39
  4853.9  367.78  4883.9  366.62  4903.9  366.45    4964  368.66  4992.2  368.29
  4994.6  367.11    4997  365.27  4999.8  364.77    5003  365.27 5003.94  367.17
    5004  368.21    5024  366.77  5032.5  365.74  5051.2  365.29  5081.2  366.68
  5129.8  367.84  5144.3  368.93  5159.4   368.9  5189.4  369.99  5225.5  370.51
  5288.6  372.99  5324.6  373.32  5333.6  373.84  5346.1  373.72  5364.4  374.54
#Mann= 3 ,-1 , 0
  4749.2     .05       0  4992.2    .035       0    5004     .05       0
Bank Sta=4994.6,5003.94
XS Rating Curve= 0 ,0
Exp/Cntr=0.3,0.1

Type RM Length L Ch R = 1 ,37804   ,670,670,670
BEGIN DESCRIPTION:
EAST FORK SALT CREEK 44.0
END DESCRIPTION:
XS GIS Cut Line= 3
      2299260.01     13402522.36      2299264.35     13402886.92
      2299492.97     13403171.61
#Sta/Elev= 30
  4727.8  372.03  4732.5  372.03  4762.3  369.98  4792.3  368.89  4802.3  368.04
  4862.3  365.54  4942.3  363.84  4951.4  363.08  4962.3  362.96  4999.8  359.75
  5022.3  361.35  5032.3  362.66  5042.3  363.21  5082.3  363.88  5089.8  364.46
  5102.2  364.39  5137.4  365.67  5151.8  365.71  5158.2  366.21  5166.2  366.02
  5180.6  366.91  5194.9  366.76  5207.9  367.53    5259  369.01  5265.4  368.77
  5300.7  369.75    5323   369.9  5329.5  370.52  5451.1   373.9  5457.5   374.4
#Mann= 3 , 0 , 0
  4727.8     .05       0  4962.3     .03       0  5032.3     .05       0
Bank Sta=4962.3,5032.3
XS Rating Curve= 0 ,0
Exp/Cntr=0.3,0.1

Type RM Length L Ch R = 1 ,37520   ,689,689,689
BEGIN DESCRIPTION:
Mapping XS bb0ba339
END DESCRIPTION:
XS GIS Cut Line= 4
      2299099.42     13402500.62      2298995.25     13402700.28
      2298982.23     13402991.08      2299281.73     13403485.91
#Sta/Elev= 30
    4668  371.42  4703.7   369.6  4720.1  369.51    4754  367.47    4792  366.91
  4821.7  364.96  4836.2  365.13  4858.3  363.63  4893.2  363.55  4919.8  362.21
  4939.8  362.31  4952.3  361.37  4959.8  360.57  4999.8  357.87  5049.9  360.18
  5059.9  361.11    5090  361.47    5110  360.85  5184.3  361.29  5322.9  364.63
  5353.9  364.64  5549.9  368.68  5571.2  369.26  5592.6  370.69  5608.1  370.42
  5613.9  371.48  5644.9  371.41  5650.7  372.07    5717  373.46  5762.7  375.34
#Mann= 3 ,-1 , 0
    4668     .05       0  4952.3     .03       0  5049.9     .05       0
Bank Sta=4959.8,5049.9
XS Rating Curve= 0 ,0
Exp/Cntr=0.3,0.1

Type RM Length L Ch R = 1 ,37134   ,800,800,800
BEGIN DESCRIPTION:
EAST FORK SALT CREEK 43.0
END DESCRIPTION:
XS GIS Cut Line= 3
      2298887.71     13402546.87      2298637.72     13402846.85
      2298637.72     13403446.86
#Sta/Elev= 30
  4605.2  365.86  4626.7  365.02  4633.2  365.41  4647.5   364.3  4669.6  363.78
  4690.4  362.58    4697  362.83  4782.9  359.86    4831  359.09  4924.8  357.65
  4931.3  357.17  4939.1  356.69  4945.6  357.23  4953.4     357  4959.9  356.21
  4967.7  356.49    4982  355.34  4988.5  355.45  4992.4  354.08  4999.8  353.53
  5025.7  356.78  5055.7  356.95  5065.7  356.56  5075.7  355.27  5088.5  355.98
  5095.7  355.97  5105.7  357.13  5115.7  357.55  5325.7  362.05  5595.7  369.48
#Mann= 5 ,-1 , 0
  4605.2     .05       0    4831      .1       0  4931.3     .07       0
  5025.7      .1       0  5088.5     .05       0
Bank Sta=4924.8,5025.7
XS Rating Curve= 0 ,0
Exp/Cntr=0.3,0.1

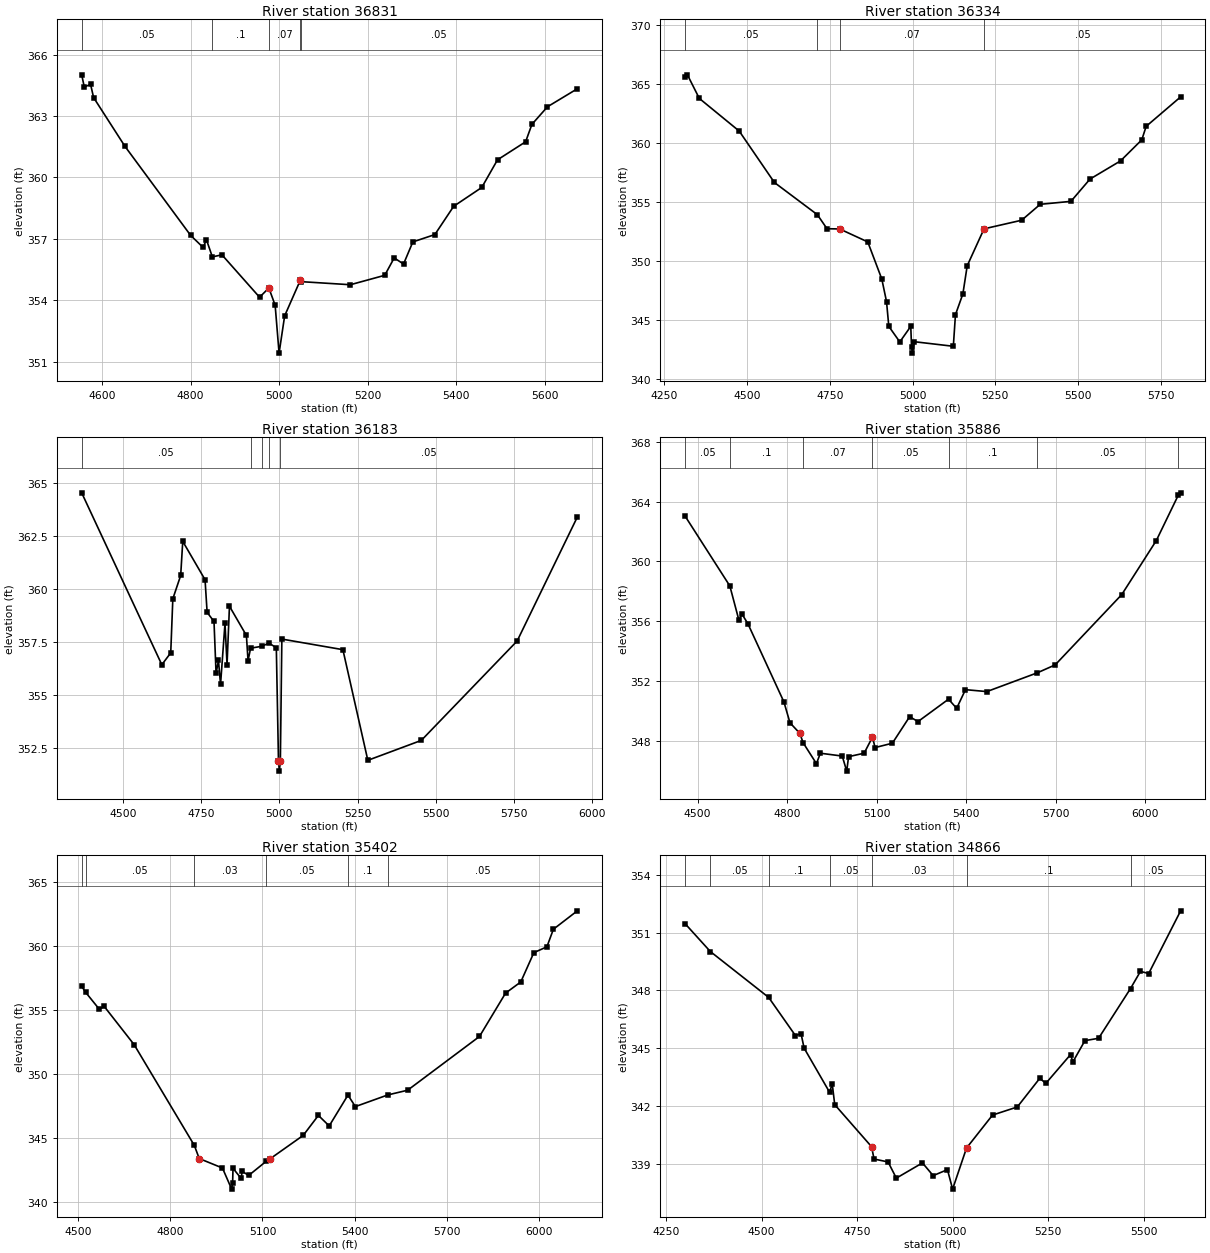
Type RM Length L Ch R = 1 ,36831   ,647,647,647
BEGIN DESCRIPTION:
Mapping XS 7c235d9e
END DESCRIPTION:
XS GIS Cut Line= 2
      2298669.71     13402440.76      2297904.08     13403258.47
#Sta/Elev= 30
  4553.7  365.01  4559.6  364.41  4573.7  364.55  4580.6   363.9  4651.4  361.52
  4799.9  357.17  4828.2  356.58  4835.6  356.96    4849  356.12  4870.7  356.22
  4955.7  354.15  4976.7   354.6  4990.9  353.76  4999.8  351.42  5012.4  353.24
  5047.6  354.97  5049.9  354.91  5160.9  354.76  5238.6  355.22    5260  356.07
  5281.1  355.77  5302.1  356.85  5351.9  357.21  5394.4  358.59  5457.9  359.51
  5493.5  360.86    5557  361.74  5571.2  362.59  5606.4  363.45  5673.9  364.33
#Mann= 5 ,-1 , 0
  4553.7     .05       0    4849      .1       0  4976.7     .07       0
  5047.6      .1       0  5049.9     .05       0
Bank Sta=4976.7,5047.6
XS Rating Curve= 0 ,0
Exp/Cntr=0.3,0.1

Type RM Length L Ch R = 1 ,36334   ,448,448,448
BEGIN DESCRIPTION:
EAST FORK SALT CREEK 42.0
END DESCRIPTION:
XS GIS Cut Line= 5
      2298581.16     13402289.72      2298258.27     13402576.15
      2298107.23     13402430.32      2297950.98     13402456.36
      2297513.46     13402998.05
#Sta/Elev= 30
    4313   365.6  4320.3   365.8  4356.2   363.8  4476.7  361.03  4582.9  356.67
  4712.6  353.94  4741.7  352.75  4779.9  352.73  4864.8  351.63  4907.2  348.48
  4921.4  346.57  4928.3  344.47  4961.5  343.15  4994.6  344.47    4997   342.7
  4999.8   342.2  5004.8  343.17  5123.1  342.78  5129.5  345.46  5151.9  347.22
    5165  349.61  5215.8  352.74  5329.4  353.47  5385.4  354.82  5478.1  355.07
  5535.7  356.96  5627.8   358.5  5692.1  360.29  5705.2  361.43  5809.3  363.93
#Mann= 4 ,-1 , 0
    4313     .05       0  4712.6      .1       0  4779.9     .07       0
  5215.8     .05       0
Bank Sta=4779.9,5215.8
XS Rating Curve= 0 ,0
Exp/Cntr=0.3,0.1

Type RM Length L Ch R = 1 ,36183   ,782,782,782
BEGIN DESCRIPTION:
EAST FORK SALT CREEK 41.0
END DESCRIPTION:
XS GIS Cut Line= 5
      2298471.84     13402169.87      2298268.69     13402404.28
       2298148.9     13402263.65      2297789.52     13402346.98
      2297343.26      13402912.6
#Sta/Elev= 30
    4368  364.53  4624.1  356.42  4652.6  356.98  4659.3  359.53  4684.4  360.63
    4691  362.24  4762.3  360.43  4768.9  358.89  4790.9  358.46  4797.5  356.01
  4805.2  356.62  4811.8  355.49    4826  358.37  4832.6  356.43  4840.3  359.18
  4894.5   357.8  4899.7  356.61  4907.9   357.2  4943.5  357.29  4966.8  357.44
  4990.1  357.22    4997   351.9  4999.8   351.4    5003   351.9  5007.8  357.63
  5202.9  357.13  5282.6  351.91  5453.6  352.85  5759.9  357.54  5952.3  363.39
#Mann= 5 ,-1 , 0
    4368     .05       0  4907.9      .1       0  4943.5     .05       0
  4966.8     .03       0    5003     .05       0
Bank Sta=4997,5003
XS Rating Curve= 0 ,0
Exp/Cntr=0.3,0.1

Type RM Length L Ch R = 1 ,35886   ,1020,1020,1020
BEGIN DESCRIPTION:
EAST FORK SALT CREEK 40.0
END DESCRIPTION:
XS GIS Cut Line= 4
      2298367.61     13401925.11      2297987.44     13401966.78
      2297605.75     13402201.57      2297128.65     13402882.61
#Sta/Elev= 30
  4457.5  363.05  4607.9  358.36  4638.5  356.05  4648.5  356.48  4668.6  355.82
  4789.4  350.58  4809.5  349.19  4842.7  348.48  4853.4  347.86  4898.3  346.45
  4911.4  347.15  4984.8  346.96  4999.8  345.95  5006.1  346.92  5058.2  347.15
  5086.2  348.23  5094.9  347.53  5152.9  347.82  5210.9   349.6  5238.8  349.27
  5341.2  350.77  5368.5  350.16  5398.1  351.41  5469.6  351.28  5639.2  352.54
  5698.9  353.07  5922.1  357.78    6038   361.4  6111.9  364.45  6119.6   364.6
#Mann= 7 ,-1 , 0
  4457.5     .05       0  4607.9      .1       0  4853.4     .07       0
  5086.2     .05       0  5341.2      .1       0  5639.2     .05       0
  6111.9      .1       0
Bank Sta=4842.7,5086.2
XS Rating Curve= 0 ,0
Exp/Cntr=0.3,0.1

Type RM Length L Ch R = 1 ,35402   ,1135,1135,1135
BEGIN DESCRIPTION:
EAST FORK SALT CREEK 39.0
END DESCRIPTION:
XS GIS Cut Line= 3
      2297887.75     13401546.84      2297437.72     13401796.85
      2296687.72     13402596.86
#Sta/Elev= 30
  4512.3  356.82  4525.5  356.34  4569.5  355.03  4585.5  355.25  4682.8  352.26
  4878.4  344.39  4894.4  343.36  4969.9  342.62  4999.8  340.97    5003  341.47
  5004.2   342.6  5030.5  341.81  5034.2  342.36  5055.2  342.04  5111.9  343.14
    5126  343.36  5232.5  345.17  5281.8  346.73    5317  345.91    5378  348.32
    5402  347.42  5507.2  348.33    5572   348.7  5805.5   352.9  5890.4  356.29
  5939.8  357.16  5982.3  359.45  6024.8  359.91  6045.8  361.28  6123.7  362.72
#Mann= 6 ,-1 , 0
  4512.3      .1       0  4525.5     .05       0  4878.4     .03       0
  5111.9     .05       0    5378      .1       0  5507.2     .05       0
Bank Sta=4894.4,5126
XS Rating Curve= 0 ,0
Exp/Cntr=0.3,0.1

Type RM Length L Ch R = 1 ,34866   ,909,909,909
BEGIN DESCRIPTION:
EAST FORK SALT CREEK 38.0
END DESCRIPTION:
XS GIS Cut Line= 3
      2297471.79     13401206.37      2297122.86     13401373.03
      2296670.56     13402163.25
#Sta/Elev= 30
  4299.4  351.47  4365.7  350.02  4518.4  347.64  4588.5  345.66  4603.1  345.76
  4611.2  345.01  4677.9  342.72  4684.7  343.17  4691.3  342.08  4787.7   339.9
  4794.2  339.26  4830.9  339.11  4852.5  338.27  4920.9  339.06  4948.9   338.4
  4986.3  338.71  4999.8   337.7  5036.2  339.83  5104.3  341.54  5169.1  341.96
  5228.1  343.45  5243.6  343.18  5308.7  344.68  5314.4  344.29  5346.1   345.4
  5381.8  345.52  5465.4   348.1  5491.4  348.99    5513  348.88  5596.6  352.13
#Mann= 7 ,-1 , 0
  4299.4      .1       0  4365.7     .05       0  4518.4      .1       0
  4677.9     .05       0  4787.7     .03       0  5036.2      .1       0
  5465.4     .05       0
Bank Sta=4787.7,5036.2
XS Rating Curve= 0 ,0
Exp/Cntr=0.3,0.1

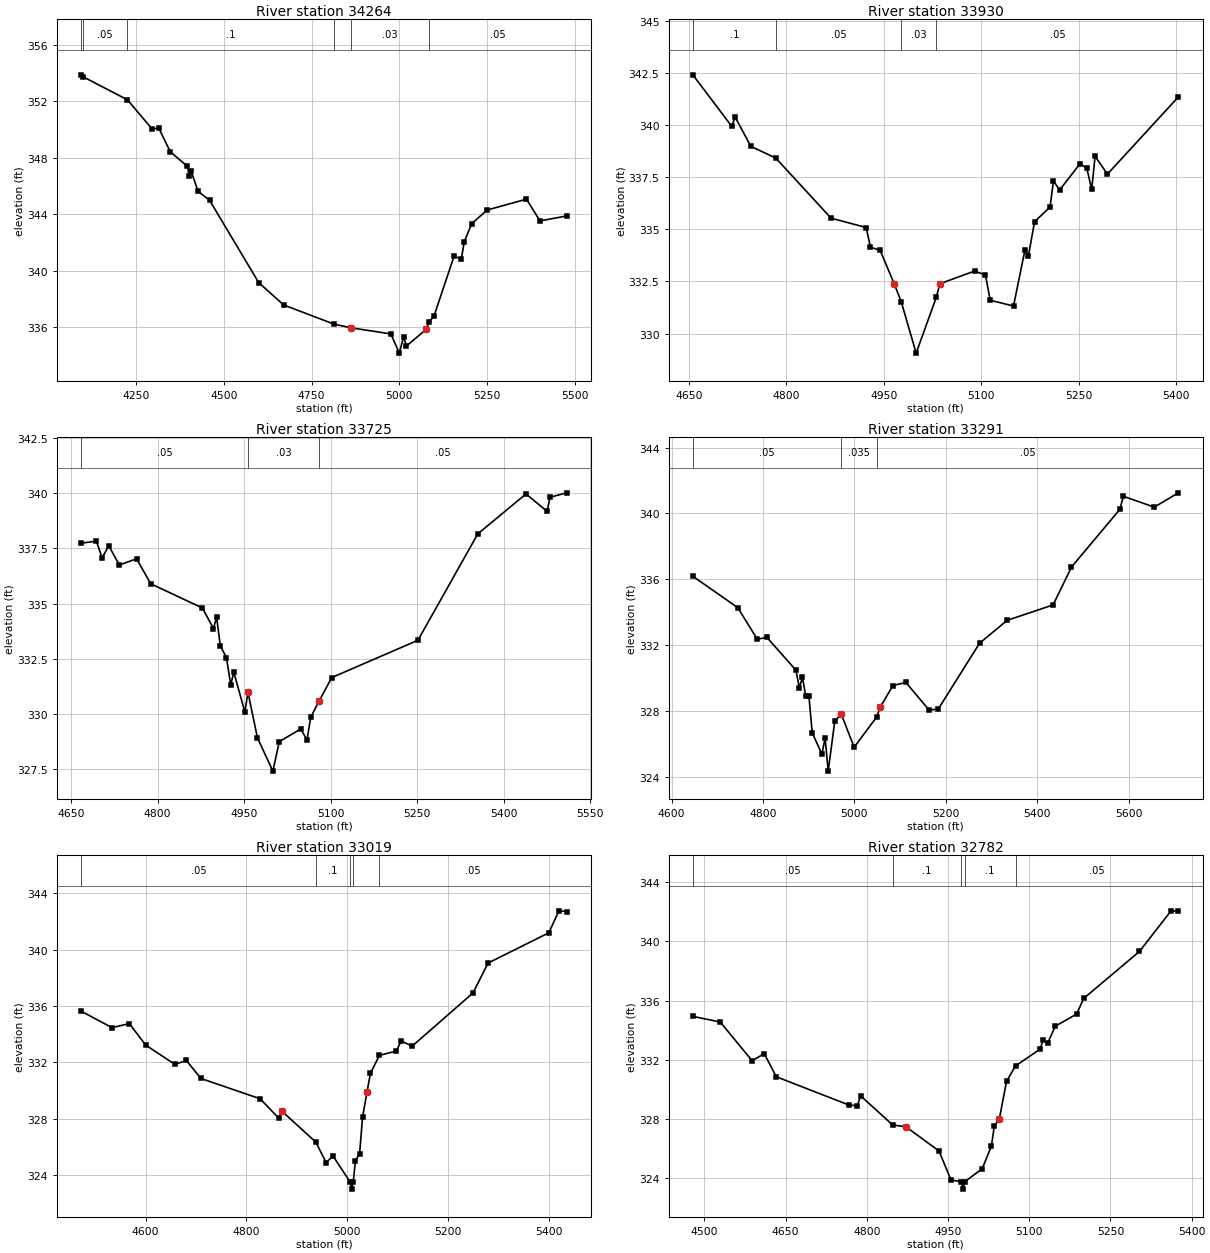
Type RM Length L Ch R = 1 ,34264   ,609,609,609
BEGIN DESCRIPTION:
Mapping XS e550dad6
END DESCRIPTION:
XS GIS Cut Line= 4
      2297445.74     13401008.45      2296794.73     13401123.03
      2296414.52     13401404.28      2296430.07     13401653.05
#Sta/Elev= 30
  4093.7  353.86  4098.4  353.73  4225.6  352.09  4294.8  350.05  4315.1  350.07
  4347.4  348.42  4396.3  347.38  4401.6  346.67  4406.7  347.05  4426.8  345.61
  4459.5  344.98  4599.4  339.15  4670.5  337.57  4814.2  336.21  4862.9  335.95
  4976.2  335.52  4999.8  334.16  5012.2  335.31  5020.1  334.66  5076.4  335.84
  5084.8  336.35  5099.3  336.82  5155.8  341.01  5176.6  340.83    5185  342.03
  5205.9  343.32  5250.3  344.29  5362.3  345.06  5400.6  343.52  5476.9  343.87
#Mann= 6 ,-1 , 0
  4093.7      .1       0  4098.4     .05       0  4225.6      .1       0
  4814.2     .05       0  4862.9     .03       0  5084.8     .05       0
Bank Sta=4862.9,5076.4
XS Rating Curve= 0 ,0
Exp/Cntr=0.3,0.1

Type RM Length L Ch R = 1 ,33930   ,650,650,650
BEGIN DESCRIPTION:
Mapping XS e878f321
END DESCRIPTION:
XS GIS Cut Line= 3
      2296974.64     13400817.81      2296476.72     13401021.51
       2296412.4     13401220.92
#Sta/Elev= 30
    4656  342.42  4715.8  339.95  4721.2  340.39  4745.2  338.99  4783.8  338.42
  4868.8  335.54  4922.8  335.09  4929.5  334.15  4944.4  333.99    4966  332.39
  4976.8  331.53  4999.8  329.06  5030.8  331.74  5036.3  332.39  5089.7     333
  5106.5  332.81  5113.8   331.6  5149.7  331.32  5167.2     334  5172.6  333.73
  5182.1  335.37  5205.9  336.07  5211.2  337.33  5220.6  336.89  5252.1  338.15
  5262.6  337.93    5270  336.92  5275.3  338.51  5294.2  337.65  5403.5  341.36
#Mann= 4 ,-1 , 0
    4656      .1       0  4783.8     .05       0  4976.8     .03       0
  5030.8     .05       0
Bank Sta=4966,5036.3
XS Rating Curve= 0 ,0
Exp/Cntr=0.3,0.1

Type RM Length L Ch R = 1 ,33725   ,434,434,434
BEGIN DESCRIPTION:
Mapping XS 25ce39fa
END DESCRIPTION:
XS GIS Cut Line= 3
      2296942.28     13400627.06      2296502.59     13400798.41
      2296415.28     13401157.34
#Sta/Elev= 30
  4667.7  337.74  4694.1  337.83  4703.9  337.07  4715.5  337.62  4733.8  336.75
  4763.7  337.03  4788.2   335.9  4877.8   334.8  4896.9  333.87  4902.3  334.39
  4908.7   333.1  4919.4  332.55  4926.8  331.33  4932.2  331.89  4951.3  330.09
  4956.7  330.98  4973.1  328.92  4999.8  327.41    5011  328.75  5048.2  329.32
    5059  328.82  5065.4  329.85  5080.4  330.61  5101.9  331.65  5251.2  333.34
  5354.9  338.16  5438.4  339.97    5475  339.18  5480.1  339.82    5509  340.02
#Mann= 3 , 0 , 0
  4667.7     .05       0  4956.7     .03       0  5080.4     .05       0
Bank Sta=4956.7,5080.4
XS Rating Curve= 0 ,0
Exp/Cntr=0.3,0.1

Type RM Length L Ch R = 1 ,33291   ,272,272,272
BEGIN DESCRIPTION:
EAST FORK SALT CREEK 37.0
END DESCRIPTION:
XS GIS Cut Line= 3
      2296121.04     13400284.29      2296463.79     13400620.57
      2296399.13      13401199.3
#Sta/Elev= 30
  4646.6  336.18    4745  334.27  4787.5  332.36  4808.8  332.46  4872.3  330.47
  4879.5  329.41  4886.5  330.03  4893.6  328.91  4900.6   328.9  4907.8  326.68
  4928.9  325.37  4936.1  326.34  4942.8  324.34  4957.2  327.38  4971.4   327.8
  4999.6  325.79  5049.1  327.64  5056.2  328.21  5084.5  329.54  5112.8  329.73
  5163.3  328.06  5183.4   328.1    5274  332.11  5334.3   333.5    5435  334.44
  5475.2  336.74  5580.9  340.24  5588.8  341.04  5656.3  340.38  5709.1  341.25
#Mann= 3 ,-1 , 0
  4646.6     .05       0  4971.4    .035       0  5049.1     .05       0
Bank Sta=4971.4,5056.2
XS Rating Curve= 0 ,0
Exp/Cntr=0.3,0.1

Type RM Length L Ch R = 1 ,33019   ,237,237,237
BEGIN DESCRIPTION:
EAST FORK SALT CREEK 36.0
END DESCRIPTION:
XS GIS Cut Line= 4
      2296049.92      13400323.1      2296163.09     13400533.27
      2296363.55     13400876.01      2296334.48     13401202.25
#Sta/Elev= 30
  4472.1  335.63  4533.2  334.46  4567.6  334.75  4600.1  333.22  4658.1  331.85
  4680.8  332.13  4709.6  330.85    4827  329.41  4864.2  328.03  4869.9  328.54
  4937.6  326.33  4958.2  324.87  4971.6  325.35  5005.8  323.49  5008.5  322.99
  5011.8  323.49  5016.2     325  5024.5  325.52  5030.3  328.09  5039.3  329.92
    5046  331.22  5063.7  332.49  5097.3   332.8    5107  333.51  5128.8  333.15
  5249.3  336.92  5279.4  339.05  5399.9   341.2  5419.9  342.76  5435.4  342.71
#Mann= 5 ,-1 , 0
  4472.1     .05       0  4937.6      .1       0  5005.8     .07       0
  5011.8      .1       0  5063.7     .05       0
Bank Sta=4869.9,5039.3
XS Rating Curve= 0 ,0
Exp/Cntr=0.3,0.1

Type RM Length L Ch R = 1 ,32782   ,355,355,355
BEGIN DESCRIPTION:
EAST FORK SALT CREEK 35.0
END DESCRIPTION:
XS GIS Cut Line= 3
      2295889.46     13400448.47      2296221.46     13401126.91
       2296293.2     13401248.86
#Sta/Elev= 30
  4478.7  334.93  4529.3  334.55  4588.2  331.94  4610.5  332.42  4632.8  330.86
  4766.4  328.96  4782.5   328.9  4788.6  329.57  4847.7  327.61  4872.5  327.48
  4933.4  325.85  4955.6  323.89  4974.9  323.78  4977.6  323.28  4980.9  323.78
  5013.1  324.65  5030.1  326.18  5035.6  327.55  5044.7  327.99  5058.1  330.55
  5074.7  331.59  5120.1  332.72  5125.7  333.33  5133.8  333.11  5148.2  334.27
  5187.6  335.09  5200.6  336.14  5303.6  339.31  5361.6  342.03  5375.5  342.05
#Mann= 5 ,-1 , 0
  4478.7     .05       0  4847.7      .1       0  4974.9     .07       0
  4980.9      .1       0  5074.7     .05       0
Bank Sta=4872.5,5044.7
XS Rating Curve= 0 ,0
Exp/Cntr=0.3,0.1

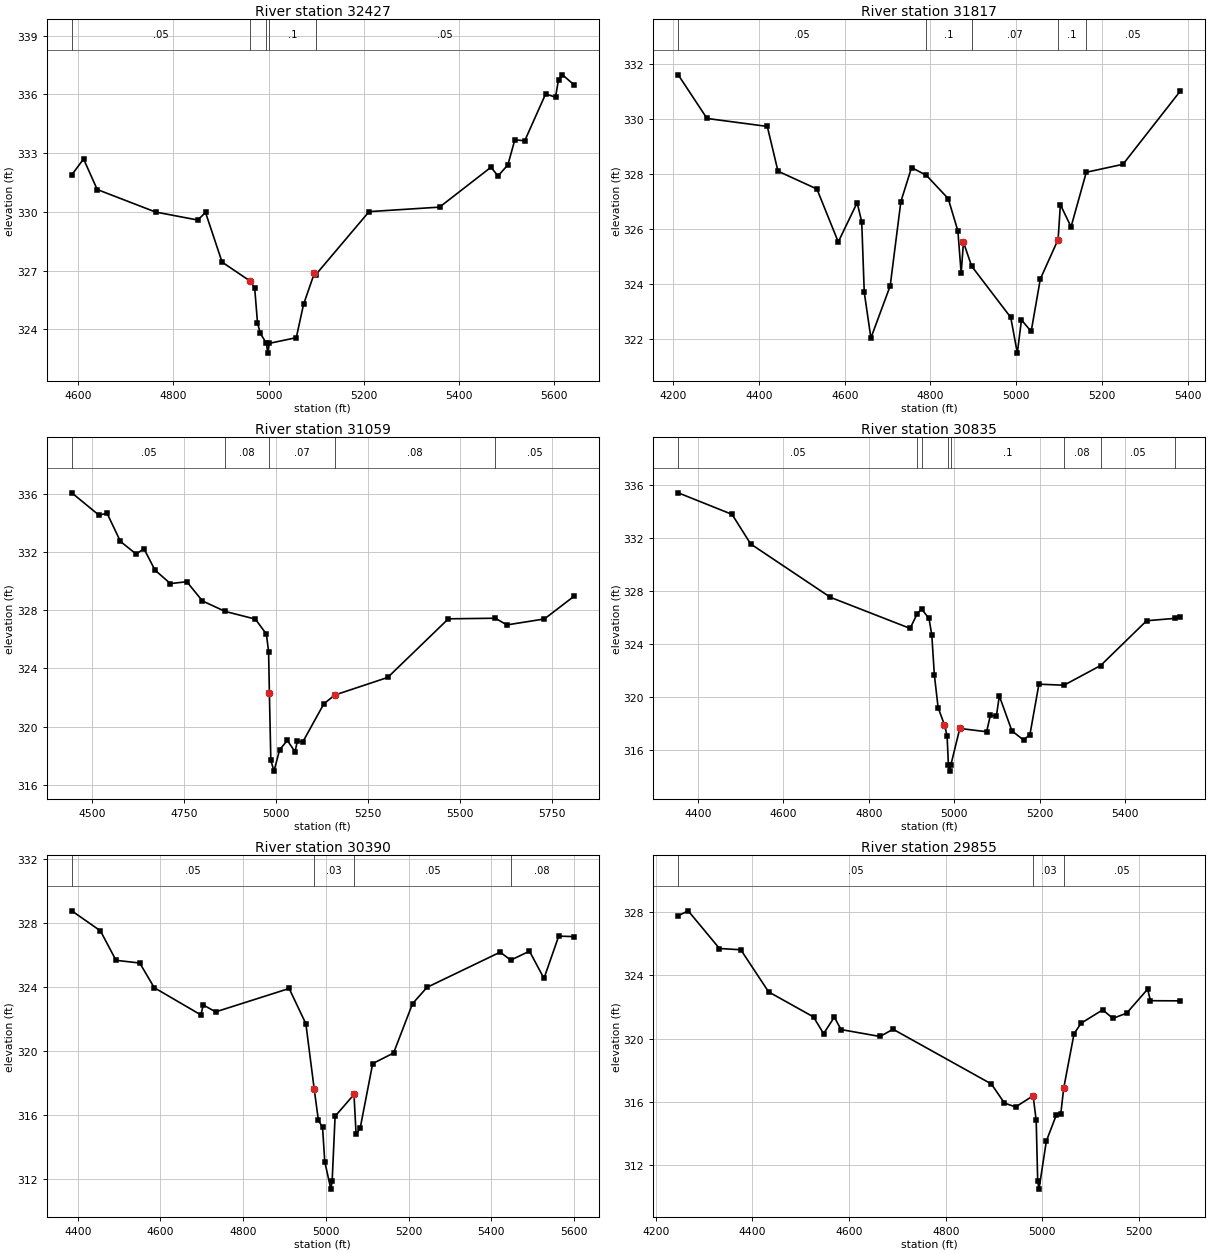
Type RM Length L Ch R = 1 ,32427   ,610,610,610
BEGIN DESCRIPTION:
EAST FORK SALT CREEK 34.0
END DESCRIPTION:
XS GIS Cut Line= 4
      2295759.55     13400672.26      2295730.69     13400910.39
      2295983.29     13401372.29       2296213.5     13401544.95
#Sta/Elev= 30
  4586.9  331.89  4611.7   332.7  4640.3  331.14  4762.8  329.99  4851.5  329.58
  4867.7  329.97  4902.5  327.43  4960.9  326.47  4970.9  326.12  4976.8  324.34
  4982.5   323.8  4995.6  323.28  4998.3  322.78  5001.6  323.28  5058.3  323.57
  5073.5  325.27  5096.3  326.87  5098.9  326.78  5211.1  330.01  5359.1  330.24
  5467.1  332.28  5481.7  331.83  5502.5   332.4  5517.1  333.68  5537.9  333.63
  5581.7  336.02  5602.5  335.86  5608.8  336.75  5617.1     337    5641   336.5
#Mann= 5 ,-1 , 0
  4586.9     .05       0  4960.9      .1       0  4995.6     .07       0
  5001.6      .1       0  5098.9     .05       0
Bank Sta=4960.9,5096.3
XS Rating Curve= 0 ,0
Exp/Cntr=0.3,0.1

Type RM Length L Ch R = 1 ,31817   ,758,758,758
BEGIN DESCRIPTION:
EAST FORK SALT CREEK 33.0
END DESCRIPTION:
XS GIS Cut Line= 2
       2295615.2     13400636.17      2295204.07     13401732.52
#Sta/Elev= 30
  4211.7  331.61  4278.8  330.02  4419.4  329.73  4444.3   328.1  4535.1  327.45
  4584.9  325.52  4628.9  326.95  4639.6  326.26  4645.5  323.69    4661  322.02
    4706  323.92  4730.9  326.99  4755.8  328.23  4790.3  327.95  4841.3   327.1
  4863.9  325.92  4871.5  324.38  4876.9  325.51  4895.9  324.64  4987.2  322.77
  5002.5  321.47  5012.1  322.68  5034.8  322.26  5056.1  324.17  5097.6  325.61
  5102.9  326.88  5127.8  326.07  5163.3  328.06  5248.9  328.35  5382.6  331.02
#Mann= 5 ,-1 , 0
  4211.7     .05       0  4790.3      .1       0  4895.9     .07       0
  5097.6      .1       0  5163.3     .05       0
Bank Sta=4876.9,5097.6
XS Rating Curve= 0 ,0
Exp/Cntr=0.3,0.1

Type RM Length L Ch R = 1 ,31059   ,224,224,224
BEGIN DESCRIPTION:
Mapping XS 90b29d90
END DESCRIPTION:
XS GIS Cut Line= 2
      2295570.73     13400326.81      2294810.44     13401462.03
#Sta/Elev= 30
  4444.4  336.07  4517.7  334.55  4540.7  334.65  4576.8  332.73  4619.7  331.86
  4640.8  332.23  4670.8  330.76  4712.8  329.83  4757.4  329.96  4799.9  328.64
  4861.5  327.92    4944  327.39    4974  326.36    4980  325.16 4982.17  322.31
  4986.1  317.69  4994.7  316.94    5010  318.41    5031  319.05    5052  318.27
  5058.3     319  5073.1  318.95  5130.5  321.57  5160.1  322.17  5304.2  323.38
  5469.3  327.41  5597.2  327.45  5628.4  326.99  5730.5   327.4  5810.7  328.95
#Mann= 5 ,-1 , 0
  4444.4     .05       0  4861.5     .08       0 4982.17     .07       0
  5160.1     .08       0  5597.2     .05       0
Bank Sta=4982.17,5160.1
XS Rating Curve= 0 ,0
Exp/Cntr=0.3,0.1

Type RM Length L Ch R = 1 ,30835   ,445,445,445
BEGIN DESCRIPTION:
EAST FORK SALT CREEK 32.0
END DESCRIPTION:
XS GIS Cut Line= 2
      2295419.67     13400233.08      2294752.99     13401201.84
#Sta/Elev= 30
  4353.6  335.44  4479.6  333.81  4523.3  331.57  4710.2  327.53  4896.7  325.18
  4913.3  326.29  4923.4  326.65  4940.9  325.94  4947.5  324.69  4953.5  321.66
  4962.3  319.19  4977.2  317.87  4983.3  317.05  4986.4  314.88  4989.2  314.38
  4992.4  314.88  5013.1  317.61    5076  317.36  5084.8  318.62  5098.7  318.52
  5105.7  320.07  5135.1  317.43  5162.5  316.73  5177.4  317.15  5198.4  320.96
  5257.1  320.88  5342.9  322.37  5450.7  325.76  5516.7  325.94  5529.6  326.03
#Mann= 8 ,-1 , 0
  4353.6     .05       0  4913.3     .08       0  4923.4      .1       0
  4986.4     .07       0  4992.4      .1       0  5257.1     .08       0
  5342.9     .05       0  5516.7     .08       0
Bank Sta=4977.2,5013.1
XS Rating Curve= 0 ,0
Exp/Cntr=0.3,0.1

Type RM Length L Ch R = 1 ,30390   ,535,535,535
BEGIN DESCRIPTION:
EAST FORK SALT CREEK 31.0
END DESCRIPTION:
XS GIS Cut Line= 3
      2294907.93      13400253.6      2294713.05     13400600.05
      2294597.58     13401408.34
#Sta/Elev= 30
  4385.6  328.76  4454.9  327.51  4492.5  325.67    4550   325.5    4585  323.96
  4697.8  322.26  4703.5  322.88  4733.5  322.45  4911.2  323.91  4951.6  321.71
  4971.8  317.63  4981.9  315.68    4992  315.24  4997.3   313.1    5012  311.38
  5015.2  311.88  5022.3  315.93    5068  317.29  5073.1   314.8  5082.9  315.18
  5113.2  319.22  5163.7  319.88  5209.5  322.96  5244.5  323.98  5421.6  326.18
    5447  325.68  5492.3  326.24  5527.4  324.54    5563  327.18  5599.6  327.15
#Mann= 4 ,-1 , 0
  4385.6     .05       0  4971.8     .03       0    5068     .05       0
    5447     .08       0
Bank Sta=4971.8,5068
XS Rating Curve= 0 ,0
Exp/Cntr=0.3,0.1

Type RM Length L Ch R = 1 ,29855   ,331,331,331
BEGIN DESCRIPTION:
EAST FORK SALT CREEK 30.0
END DESCRIPTION:
XS GIS Cut Line= 2
      2294669.73     13400159.82      2294085.15     13401018.65
#Sta/Elev= 30
  4246.5  327.79  4267.1   328.1  4331.8  325.71    4376  325.63  4433.5  322.96
  4526.4  321.37  4547.3  320.31  4569.5  321.36  4583.3  320.57    4664  320.13
    4691  320.59  4894.4  317.12  4921.4  315.91  4944.5  315.66  4980.8  316.37
  4987.2  314.81  4990.3  310.95    4993  310.45  5008.2   313.5  5029.2  315.18
  5038.1  315.24  5044.1  316.85  5065.5   320.3    5080  320.97  5124.8  321.82
  5145.8  321.28  5174.4  321.61  5217.7  323.13  5223.7   322.4  5285.4  322.39
#Mann= 3 , 0 , 0
  4246.5     .05       0  4980.8     .03       0  5044.1     .05       0
Bank Sta=4980.8,5044.1
XS Rating Curve= 0 ,0
Exp/Cntr=0.3,0.1