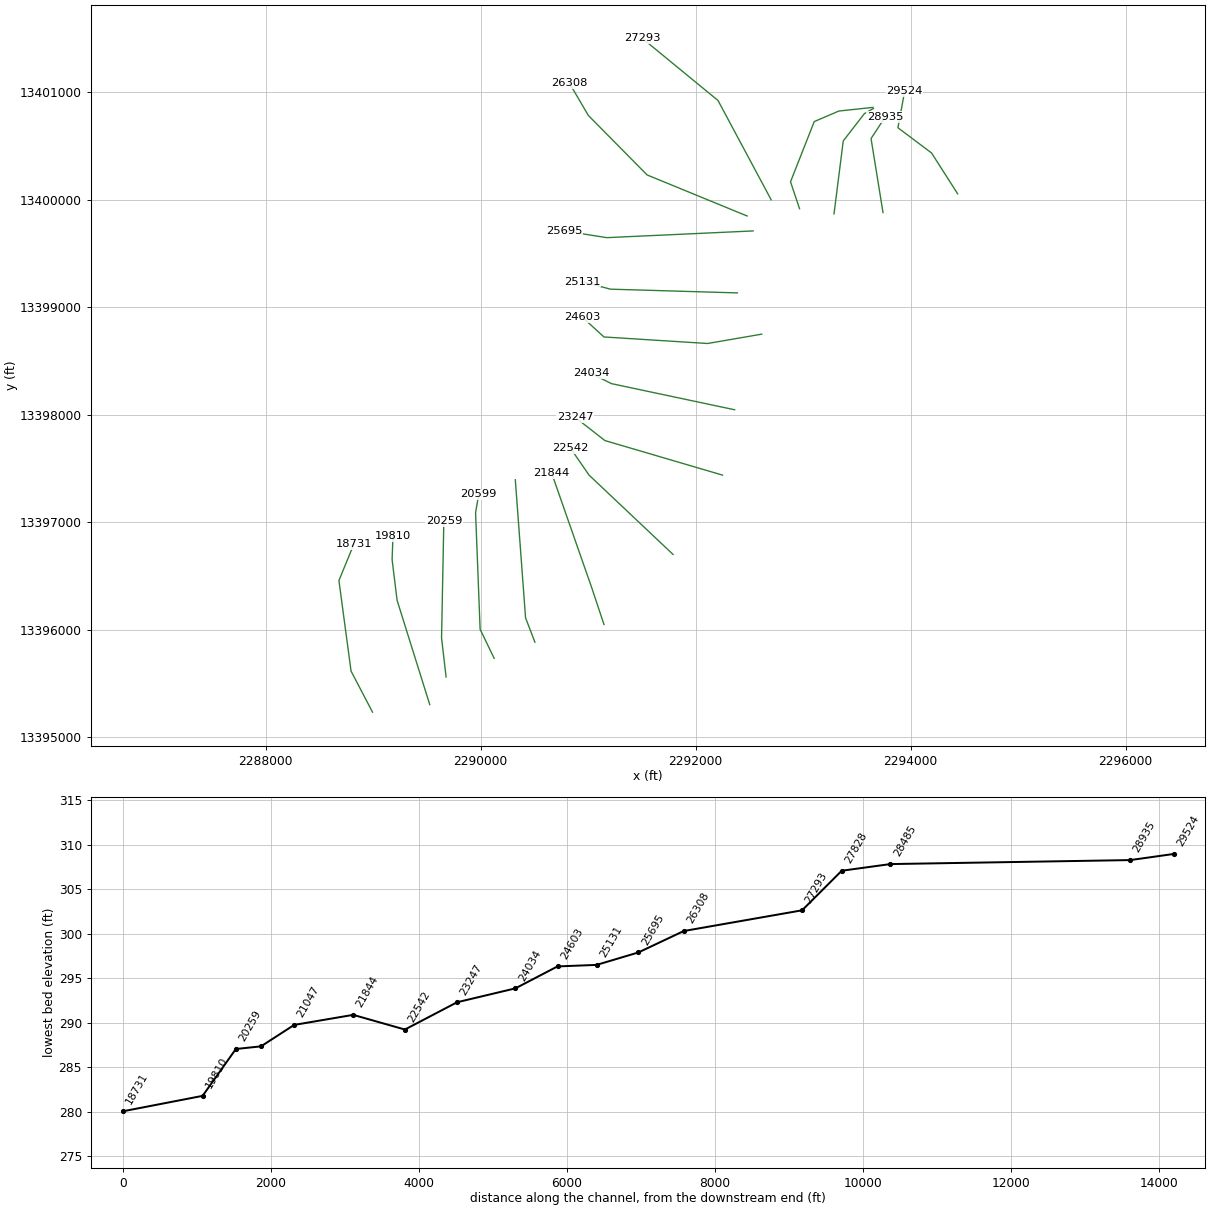
HEC-RAS study EAST FORK SALT CREEK.prj: EAST FORK SALT CREEK Base Level Engineering

--- EAST FORK SALT CREEK.g01 (geometry) --- (continued)

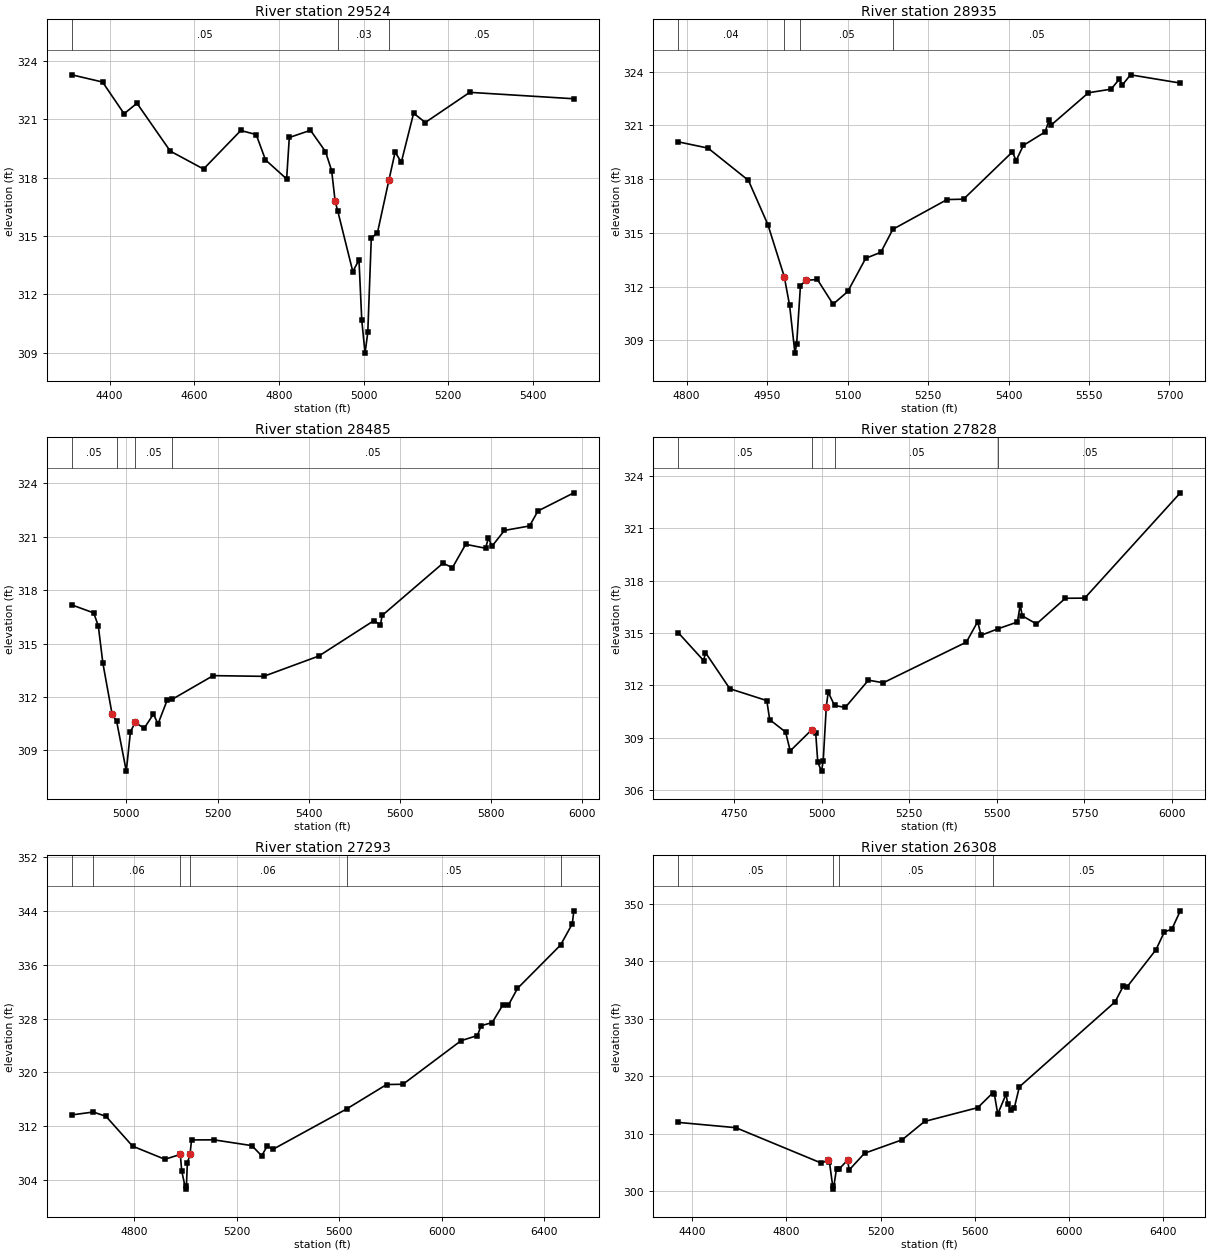
Type RM Length L Ch R = 1 ,29524   ,589,589,589
BEGIN DESCRIPTION:
Mapping XS 658cc9ae
END DESCRIPTION:
XS GIS Cut Line= 4
      2294437.89     13400055.58      2294194.83     13400435.79
      2293882.33     13400670.16      2293944.83     13401008.66
#Sta/Elev= 30
  4310.7  323.28  4383.4  322.91  4434.3  321.28  4464.7  321.82  4543.4  319.36
    4622  318.44    4710  320.42  4746.4  320.21  4768.3  318.91  4818.3  317.93
  4824.6  320.06  4874.6  320.43    4910  319.34  4924.6  318.36  4932.9  316.78
  4939.2  316.27  4974.6  313.17  4989.2  313.77  4995.8  310.67  5003.5  308.98
    5010  310.04  5018.3  314.89  5032.9  315.17    5060  317.88  5074.6  319.31
  5089.2  318.79  5118.3  321.31  5145.8  320.83  5250.9  322.38  5496.8  322.05
#Mann= 3 ,-1 , 0
  4310.7     .05       0  4939.2     .03       0    5060     .05       0
Bank Sta=4932.9,5060
XS Rating Curve= 0 ,0
Exp/Cntr=0.3,0.1

Type RM Length L Ch R = 1 ,28935   ,3240,3240,3240
BEGIN DESCRIPTION:
EAST FORK SALT CREEK 29.0
END DESCRIPTION:
XS GIS Cut Line= 3
      2293743.45     13399881.93      2293632.33     13400569.47
       2293763.5     13400769.67
#Sta/Elev= 30
  4784.4  320.08    4840  319.73  4915.2  317.93  4951.5  315.46    4982  312.56
    4992  310.95  5001.9  308.29  5005.1  308.79  5012.2  312.06  5022.4  312.35
  5043.7   312.4    5073  311.02  5100.4  311.73  5133.8  313.58  5162.1  313.92
  5184.4   315.2  5285.5  316.86  5316.1  316.88  5407.3  319.52  5414.1  319.03
  5427.6  319.88  5468.1  320.63  5475.8   321.3  5479.6  321.02    5549  322.82
  5591.2  323.02  5606.3  323.57  5612.3  323.26  5627.4  323.82  5720.2  323.36
#Mann= 4 ,-1 , 0
  4784.4     .04       0    4982     .03       0  5012.2     .05       0
  5184.4     .05       0
Bank Sta=4982,5022.4
XS Rating Curve= 0 ,0
Exp/Cntr=0.3,0.1

Type RM Length L Ch R = 1 ,28485   ,657,657,657
BEGIN DESCRIPTION:
EAST FORK SALT CREEK 28.0
END DESCRIPTION:
XS GIS Cut Line= 4
      2293287.92     13399869.14      2293373.75      13400547.6
      2293569.94     13400801.01      2293654.21     13400849.16
#Sta/Elev= 30
  4880.2  317.17  4928.3  316.72  4938.4  315.99  4948.5  313.89  4968.6  311.05
  4978.7  310.63  4999.8  307.84  5008.9  310.04    5019  310.57  5039.2  310.25
  5059.3  311.04  5069.4  310.49  5089.6  311.83  5101.1  311.88  5190.4   313.2
  5301.2  313.16  5422.2   314.3  5543.2  316.29  5557.1  316.04  5561.2  316.58
  5694.5  319.51  5715.3  319.26  5744.3  320.57  5787.8  320.35  5794.1  320.91
  5802.2  320.47  5829.4  321.35  5884.5   321.6  5902.8  322.44  5981.6  323.46
#Mann= 4 ,-1 , 0
  4880.2     .05       0  4978.7     .03       0    5019     .05       0
  5101.1     .05       0
Bank Sta=4968.6,5019
XS Rating Curve= 0 ,0
Exp/Cntr=0.3,0.1

Type RM Length L Ch R = 1 ,27828   ,535,535,535
BEGIN DESCRIPTION:
Mapping XS c876d36d
END DESCRIPTION:
XS GIS Cut Line= 5
      2292967.13     13399917.26      2292883.27     13400167.48
      2293103.99     13400727.44      2293332.88     13400825.53
      2293648.88     13400859.27
#Sta/Elev= 30
  4590.9  315.02  4663.4  313.42  4668.6  313.88  4738.1  311.81  4843.6  311.13
  4851.8  310.04  4897.1  309.33  4910.5  308.25  4972.4  309.47  4983.1  309.29
  4989.1  307.59  4999.8  307.09  5004.6  307.69  5013.4  310.79  5018.8  311.61
  5036.9  310.85  5067.6  310.74  5133.6   312.3  5175.9  312.15  5413.1  314.48
  5445.3  315.65    5455  314.87  5504.3  315.25  5558.7  315.63  5566.8  316.63
  5572.2  315.99  5613.1  315.52  5695.5  316.99  5750.8     317  6023.5  323.03
#Mann= 4 ,-1 , 0
  4590.9     .05       0  4972.4     .03       0  5036.9     .05       0
  5504.3     .05       0
Bank Sta=4972.4,5013.4
XS Rating Curve= 0 ,0
Exp/Cntr=0.3,0.1

Type RM Length L Ch R = 1 ,27293   ,1598,1598,1598
BEGIN DESCRIPTION:
EAST FORK SALT CREEK 27.0
END DESCRIPTION:
XS GIS Cut Line= 3
      2292703.45     13399999.85      2292208.87     13400923.63
      2291503.73     13401502.25
#Sta/Elev= 30
  4555.4  313.68  4639.4  314.11  4688.9  313.47  4792.9  309.03  4918.9  307.08
    4979   307.8  4984.7  305.34  4999.8  302.64    5003  303.14  5006.6  306.53
  5017.1   307.8  5022.9  309.96  5110.6  309.97  5258.5  309.11  5296.7   307.6
  5318.7  309.06  5340.6  308.56  5628.1  314.56  5784.5   318.2  5848.4  318.24
  6075.1  324.72    6139  325.49  6153.3  326.95  6196.4  327.41  6238.6  330.06
  6260.3  330.04  6295.4   332.5  6463.6  338.95  6509.3  342.11  6515.4  344.04
#Mann= 6 ,-1 , 0
  4555.4     .05       0  4639.4     .06       0    4979     .03       0
  5017.1     .06       0  5628.1     .05       0  6463.6     .08       0
Bank Sta=4979,5017.1
XS Rating Curve= 0 ,0
Exp/Cntr=0.3,0.1

Type RM Length L Ch R = 1 ,26308   ,613,613,613
BEGIN DESCRIPTION:
EAST FORK SALT CREEK 26.0
END DESCRIPTION:
XS GIS Cut Line= 4
      2292479.73     13399849.35      2291549.18      13400231.3
      2291003.23     13400783.91      2290826.13     13401086.02
#Sta/Elev= 30
  4340.7  311.94  4585.2  311.02  4947.9  304.86  4977.3  305.32  4982.7  305.12
    4997  300.81  4999.8  300.31  5013.1  303.88  5023.9   303.8    5060  305.37
  5067.1  303.66    5132  306.56  5292.1  308.91  5386.9   312.1  5613.2  314.51
  5676.9  317.08  5683.9  316.81    5698   313.4  5733.4  316.85  5740.5  315.09
  5754.6  314.16  5768.7  314.53    5790  318.14  6196.4  332.94  6231.1  335.67
  6245.8  335.47  6370.2  342.03    6406  345.15  6437.4  345.59  6473.6  348.81
#Mann= 4 ,-1 , 0
  4340.7     .05       0    4997     .03       0  5023.9     .05       0
  5676.9     .05       0
Bank Sta=4977.3,5060
XS Rating Curve= 0 ,0
Exp/Cntr=0.3,0.1

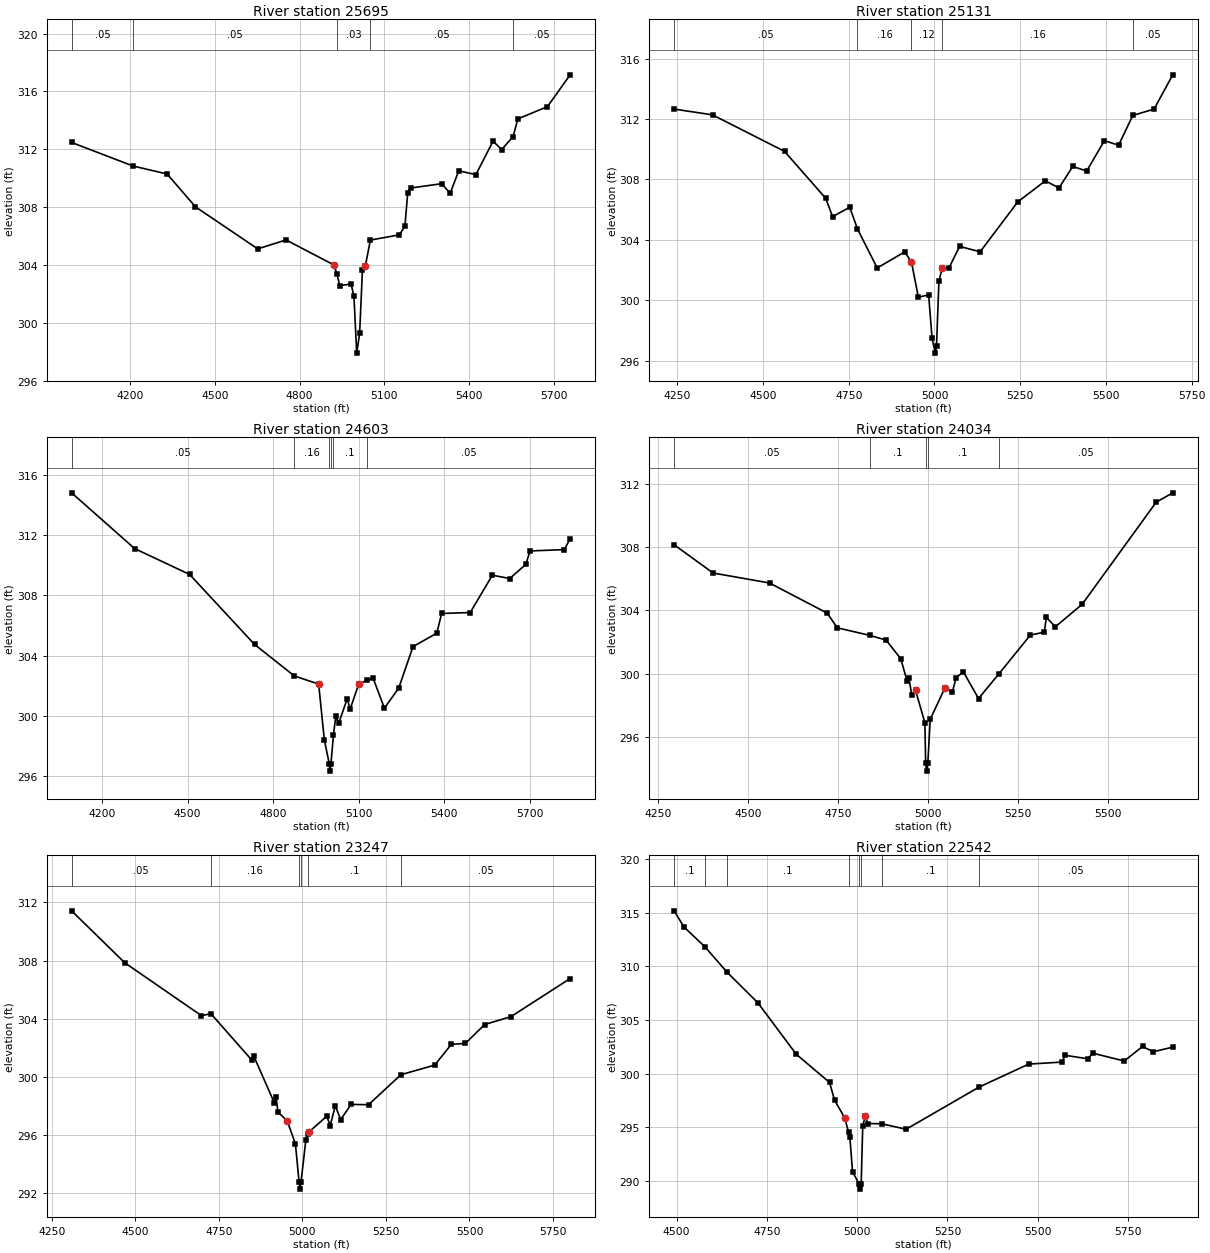
Type RM Length L Ch R = 1 ,25695   ,564,564,564
BEGIN DESCRIPTION:
EAST FORK SALT CREEK 25.0
END DESCRIPTION:
XS GIS Cut Line= 3
      2292535.31     13399710.46      2291174.18     13399647.96
      2290778.35     13399710.46
#Sta/Elev= 30
  3993.9  312.47  4211.7  310.84  4331.8  310.29    4432  308.02  4652.2  305.11
  4752.3  305.73  4922.5  303.99  4932.5  303.35  4942.5  302.57  4982.5  302.68
  4992.5  301.82  5002.3   297.9  5012.6  299.26  5022.6  303.66  5032.6   303.9
  5050.6  305.72  5152.7  306.08  5172.7  306.67  5182.7  308.99  5192.8  309.32
  5302.9  309.62  5332.9  308.95    5363  310.51  5423.8  310.25  5484.5  312.56
  5514.9  311.98  5555.4  312.88  5572.2   314.1  5676.8  314.95  5757.2  317.15
#Mann= 5 ,-1 , 0
  3993.9     .05       0  4211.7     .05       0  4932.5     .03       0
  5050.6     .05       0  5555.4     .05       0
Bank Sta=4922.5,5032.6
XS Rating Curve= 0 ,0
Exp/Cntr=0.3,0.1

Type RM Length L Ch R = 1 ,25131   ,528,528,528
BEGIN DESCRIPTION:
EAST FORK SALT CREEK 24.0
END DESCRIPTION:
XS GIS Cut Line= 3
      2292389.42     13399134.07       2291208.9      13399168.8
      2290945.01     13399238.24
#Sta/Elev= 30
    4241  312.66  4352.7  312.28  4562.8  309.86  4682.9  306.75  4702.9  305.54
  4752.9  306.16  4775.5  304.72    4833  302.14    4913   303.2    4933  302.53
    4953   300.2    4983  300.36    4993  297.47  5002.8   296.5    5006     297
    5013  301.28    5023  302.16    5043  302.17  5073.1  303.57  5133.1  303.21
  5243.1  306.52  5323.2  307.91  5363.2  307.44  5403.2  308.86  5443.9  308.56
  5495.6  310.57    5537  310.27  5578.4  312.24  5640.4  312.66  5694.9  314.93
#Mann= 5 ,-1 , 0
    4241     .05       0  4775.5     .16       0    4933     .12       0
    5023     .16       0  5578.4     .05       0
Bank Sta=4933,5023
XS Rating Curve= 0 ,0
Exp/Cntr=0.3,0.1

Type RM Length L Ch R = 1 ,24603   ,569,569,569
BEGIN DESCRIPTION:
EAST FORK SALT CREEK 23.0
END DESCRIPTION:
XS GIS Cut Line= 4
       2292615.2      13398750.4      2292111.68     13398663.59
      2291148.14     13398724.35      2290948.45     13398906.67
#Sta/Elev= 30
  4093.9  314.81  4314.6  311.11  4507.4  309.39  4735.1  304.74  4874.4  302.65
  4959.5  302.11  4979.5   298.4  4996.6  296.83  4999.3  296.33  5002.6  296.83
  5011.3  298.72  5019.6  299.99  5029.6   299.5  5059.7  301.14  5069.7  300.44
  5099.8   302.1  5128.7  302.36  5149.9  302.52    5190  300.51  5240.1  301.85
  5290.2   304.6  5373.5  305.49  5390.4   306.8  5490.6  306.86    5568  309.34
  5628.9  309.12  5685.6  310.06  5699.8  310.95  5820.1  311.04  5840.7  311.77
#Mann= 6 ,-1 , 0
  4093.9     .05       0  4874.4     .16       0  4996.6     .07       0
  5002.6     .16       0  5011.3      .1       0  5128.7     .05       0
Bank Sta=4959.5,5099.8
XS Rating Curve= 0 ,0
Exp/Cntr=0.3,0.1

Type RM Length L Ch R = 1 ,24034   ,787,787,787
BEGIN DESCRIPTION:
EAST FORK SALT CREEK 22.0
END DESCRIPTION:
XS GIS Cut Line= 3
      2292363.44     13398047.26      2291217.58     13398290.32
      2291026.58     13398385.82
#Sta/Elev= 30
  4294.4  308.14  4402.5  306.36  4559.2  305.73  4719.4  303.83  4747.6   302.9
    4837  302.43  4882.9  302.13  4923.8  300.95  4941.1  299.56  4946.2  299.74
  4954.5  298.64  4964.7  298.96  4990.7  296.92  4992.9  294.36  4995.6  293.86
  4998.9  294.36  5005.6  297.13  5046.5  299.12  5066.9  298.83  5077.2  299.74
  5097.6  300.13  5139.7  298.44  5195.7  299.98  5283.5  302.44  5322.5  302.63
  5328.1  303.56  5353.2  302.97  5427.4  304.38  5633.3  310.83  5679.3  311.42
#Mann= 5 ,-1 , 0
  4294.4     .05       0    4837      .1       0  4992.9     .07       0
  4998.9      .1       0  5195.7     .05       0
Bank Sta=4964.7,5046.5
XS Rating Curve= 0 ,0
Exp/Cntr=0.3,0.1

Type RM Length L Ch R = 1 ,23247   ,705,705,705
BEGIN DESCRIPTION:
EAST FORK SALT CREEK 21.0
END DESCRIPTION:
XS GIS Cut Line= 3
      2292250.57     13397439.63      2291156.82     13397760.81
      2290879.07      13397977.8
#Sta/Elev= 30
  4309.1  311.42  4468.4  307.85  4697.7  304.22  4726.2  304.35  4849.1  301.15
  4854.3  301.45  4915.9  298.23  4921.1  298.62    4927  297.59  4954.5  296.99
  4979.1  295.41    4990   292.8  4992.8   292.3    4996   292.8  5010.4   295.7
  5017.7  296.09  5020.8  296.25  5072.9  297.31  5083.3  296.67  5098.4  298.02
  5114.6  297.08  5145.9  298.12    5198   298.1  5294.9  300.16    5396  300.82
    5446  302.25  5487.8  302.31  5545.6  303.61  5624.3  304.15  5801.5  306.77
#Mann= 6 ,-1 , 0
  4309.1     .05       0  4726.2     .16       0    4990     .07       0
    4996     .16       0  5017.7      .1       0  5294.9     .05       0
Bank Sta=4954.5,5020.8
XS Rating Curve= 0 ,0
Exp/Cntr=0.3,0.1

Type RM Length L Ch R = 1 ,22542   ,698,698,698
BEGIN DESCRIPTION:
EAST FORK SALT CREEK 20.0
END DESCRIPTION:
XS GIS Cut Line= 3
      2291790.47      13396701.8      2291009.25     13397439.63
      2290835.62     13397691.39
#Sta/Elev= 30
  4493.6  315.16  4520.4  313.66  4578.4  311.82  4639.7  309.45  4725.5  306.58
  4831.5   301.8  4923.8  299.17  4937.5  297.53  4965.8  295.86  4976.4  294.52
    4980  294.09  4987.3  290.86  5005.3  289.73  5008.1  289.23  5011.3  289.73
  5015.6   295.1  5022.5  296.02  5029.7  295.34  5068.2  295.32  5135.7  294.81
  5337.8  298.74  5475.2  300.88  5568.2  301.07  5575.3   301.7  5638.1  301.38
    5653  301.89  5739.6  301.17  5790.3  302.52  5819.9  302.03    5874  302.46
#Mann= 8 ,-1 , 0
  4493.6      .1       0  4578.4     .05       0  4639.7      .1       0
  4976.4     .12       0  5005.3     .07       0  5011.3     .12       0
  5068.2      .1       0  5337.8     .05       0
Bank Sta=4965.8,5022.5
XS Rating Curve= 0 ,0
Exp/Cntr=0.3,0.1

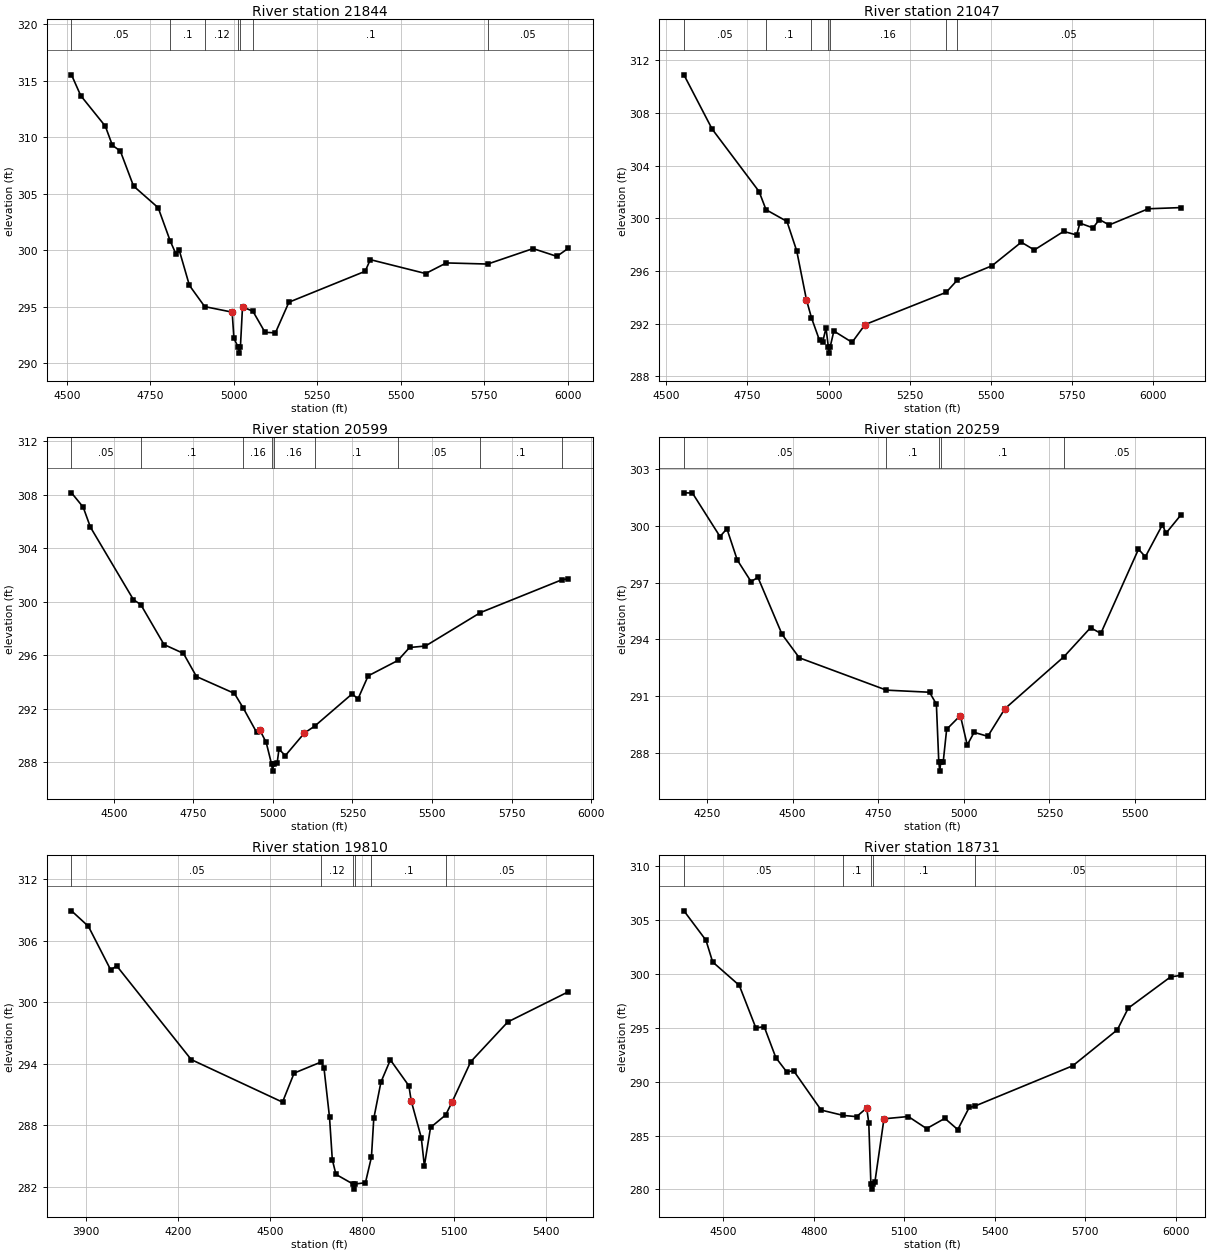
Type RM Length L Ch R = 1 ,21844   ,797,797,797
BEGIN DESCRIPTION:
EAST FORK SALT CREEK 19.0
END DESCRIPTION:
XS GIS Cut Line= 3
      2291148.14     13396050.71      2291035.29     13396389.28
      2290662.37     13397455.99
#Sta/Elev= 30
    4514  315.53  4541.6  313.69  4615.3  310.98  4636.4  309.29  4660.2  308.78
  4699.7  305.68  4773.5  303.76  4809.7   300.8  4826.2   299.7  4836.7  299.98
    4867  296.88  4912.8     295    4995  294.51  5000.3  292.18  5013.6  291.38
  5016.4  290.88  5019.6  291.38    5026  294.98  5057.1  294.59  5093.4  292.72
  5124.5  292.68  5164.9  295.39  5393.2  298.13  5408.6  299.16  5574.2  297.93
  5636.3  298.87  5759.9  298.77  5895.9  300.14  5967.1  299.45  6000.9  300.16
#Mann= 7 ,-1 , 0
    4514     .05       0  4809.7      .1       0  4912.8     .12       0
  5013.6     .07       0  5019.6     .12       0  5057.1      .1       0
  5759.9     .05       0
Bank Sta=4995,5026
XS Rating Curve= 0 ,0
Exp/Cntr=0.3,0.1

Type RM Length L Ch R = 1 ,21047   ,448,448,448
BEGIN DESCRIPTION:
EAST FORK SALT CREEK 18.0
END DESCRIPTION:
XS GIS Cut Line= 3
      2290505.79     13395885.78      2290418.97      13396111.5
      2290323.48     13397396.21
#Sta/Elev= 30
  4554.5   310.9  4641.3  306.78    4786  302.03  4807.4  300.65  4871.9  299.76
    4902  297.52  4932.1  293.79  4947.5  292.43  4972.2  290.72  4982.2  290.62
  4992.2  291.66  4999.3  290.25    5002  289.75  5005.3  290.25  5016.4  291.43
  5072.5  290.57  5112.6  291.92  5362.4  294.37  5396.7   295.3  5503.6  296.39
  5593.9  298.18    5634  297.59  5724.3     299  5764.4  298.73  5774.4  299.63
  5814.5  299.27  5834.6   299.9  5864.6  299.49    5985  300.72  6084.6  300.81
#Mann= 7 ,-1 , 0
  4554.5     .05       0  4807.4      .1       0  4947.5     .16       0
  4999.3     .07       0  5005.3     .16       0  5362.4      .1       0
  5396.7     .05       0
Bank Sta=4932.1,5112.6
XS Rating Curve= 0 ,0
Exp/Cntr=0.3,0.1

Type RM Length L Ch R = 1 ,20599   ,340,340,340
BEGIN DESCRIPTION:
EAST FORK SALT CREEK 17.0
END DESCRIPTION:
XS GIS Cut Line= 4
      2290126.97     13395735.25      2289996.16     13396005.31
      2289953.96     13397089.89      2289983.42     13397262.42
#Sta/Elev= 30
  4367.2  308.14  4403.9  307.07  4426.5  305.58  4561.9  300.15  4584.8  299.79
  4657.9   296.8  4718.9  296.14  4759.8  294.41    4879  293.15    4907  292.05
    4949  290.23    4959  290.41    4979  289.48  4996.1  287.84  4998.8  287.34
  5002.1  287.84  5013.5  287.97  5019.1  288.98  5039.1   288.5  5099.1  290.19
  5131.2   290.7  5249.3  293.12  5267.2  292.73  5299.3  294.46  5392.6  295.61
  5429.4  296.58  5479.4  296.69  5652.1  299.19  5907.8  301.64  5927.7  301.72
#Mann= 9 ,-1 , 0
  4367.2     .05       0  4584.8      .1       0    4907     .16       0
  4996.1     .07       0  5002.1     .16       0  5131.2      .1       0
  5392.6     .05       0  5652.1      .1       0  5907.8     .05       0
Bank Sta=4959,5099.1
XS Rating Curve= 0 ,0
Exp/Cntr=0.3,0.1

Type RM Length L Ch R = 1 ,20259   ,449,449,449
BEGIN DESCRIPTION:
EAST FORK SALT CREEK 16.0
END DESCRIPTION:
XS GIS Cut Line= 3
      2289679.64     13395562.23      2289637.45     13395925.13
      2289658.55     13397009.68
#Sta/Elev= 30
  4182.7  301.75  4207.5  301.74    4288  299.44  4308.2  299.85  4338.4   298.2
  4378.6  297.06  4398.8  297.28  4469.2  294.27  4519.6  293.03  4774.1  291.32
  4899.8  291.21  4919.8  290.58  4926.8  287.54  4929.6  287.04  4932.8  287.54
  4939.8  287.54  4949.8  289.25  4989.8  289.98  5009.9  288.42  5029.9  289.09
  5069.9  288.88  5119.9  290.34  5292.4  293.09  5369.9  294.62  5399.9  294.32
  5509.9  298.77    5530  298.37    5580  300.07    5590  299.61  5632.8  300.56
#Mann= 5 ,-1 , 0
  4182.7     .05       0  4774.1      .1       0  4926.8     .07       0
  4932.8      .1       0  5292.4     .05       0
Bank Sta=4989.8,5119.9
XS Rating Curve= 0 ,0
Exp/Cntr=0.3,0.1

Type RM Length L Ch R = 1 ,19810   ,1079,1079,1079
BEGIN DESCRIPTION:
EAST FORK SALT CREEK 15.0
END DESCRIPTION:
XS GIS Cut Line= 4
      2289527.72     13395304.78      2289223.87      13396275.4
      2289177.45     13396655.21      2289185.84     13396873.25
#Sta/Elev= 30
  3853.5   308.9  3908.5  307.39  3981.4  303.13  4000.6  303.54  4243.5   294.4
  4540.9  290.25  4578.7  293.08  4667.2  294.17  4675.9   293.6    4694  288.78
  4703.1  284.65  4714.9  283.21  4770.3  282.27    4773  281.77  4776.3  282.27
    4811  282.39  4830.6   284.9  4838.2  288.66  4861.6  292.21  4892.2  294.37
  4952.6  291.84  4960.1  290.38  4992.9  286.79    5003  284.04  5023.1  287.78
  5072.5     289  5093.7  290.29  5154.1  294.19  5274.9  298.07  5471.4     301
#Mann= 6 ,-1 , 0
  3853.5     .05       0  4667.2     .12       0  4770.3     .07       0
  4776.3     .12       0  4830.6      .1       0  5072.5     .05       0
Bank Sta=4960.1,5093.7
XS Rating Curve= 0 ,0
Exp/Cntr=0.3,0.1

Type RM Length L Ch R = 1 ,18731   ,583,583,583
BEGIN DESCRIPTION:
EAST FORK SALT CREEK 14.0
END DESCRIPTION:
XS GIS Cut Line= 4
      2288995.37     13395234.75      2288795.71     13395616.71
      2288682.86     13396458.73      2288821.76      13396797.3
#Sta/Elev= 30
  4369.8  305.83  4442.9   303.1    4465  301.09  4553.3  298.92  4608.2  294.98
  4635.9  295.09  4674.5  292.22  4710.7  290.89  4733.3  291.01  4824.7  287.36
  4898.4  286.86  4942.2  286.75  4975.7  287.55  4982.6  286.18  4989.6  280.53
  4992.4  280.03  4995.6  280.53  5002.7  280.65    5033  286.55  5113.7  286.76
  5174.3  285.64  5234.8  286.59  5277.6  285.55  5315.5   287.6  5333.7  287.72
  5659.1  291.47  5806.6   294.8  5842.9  296.81  5983.4  299.71  6016.3  299.84
#Mann= 5 ,-1 , 0
  4369.8     .05       0  4898.4      .1       0  4989.6     .07       0
  4995.6      .1       0  5333.7     .05       0
Bank Sta=4975.7,5033
XS Rating Curve= 0 ,0
Exp/Cntr=0.3,0.1