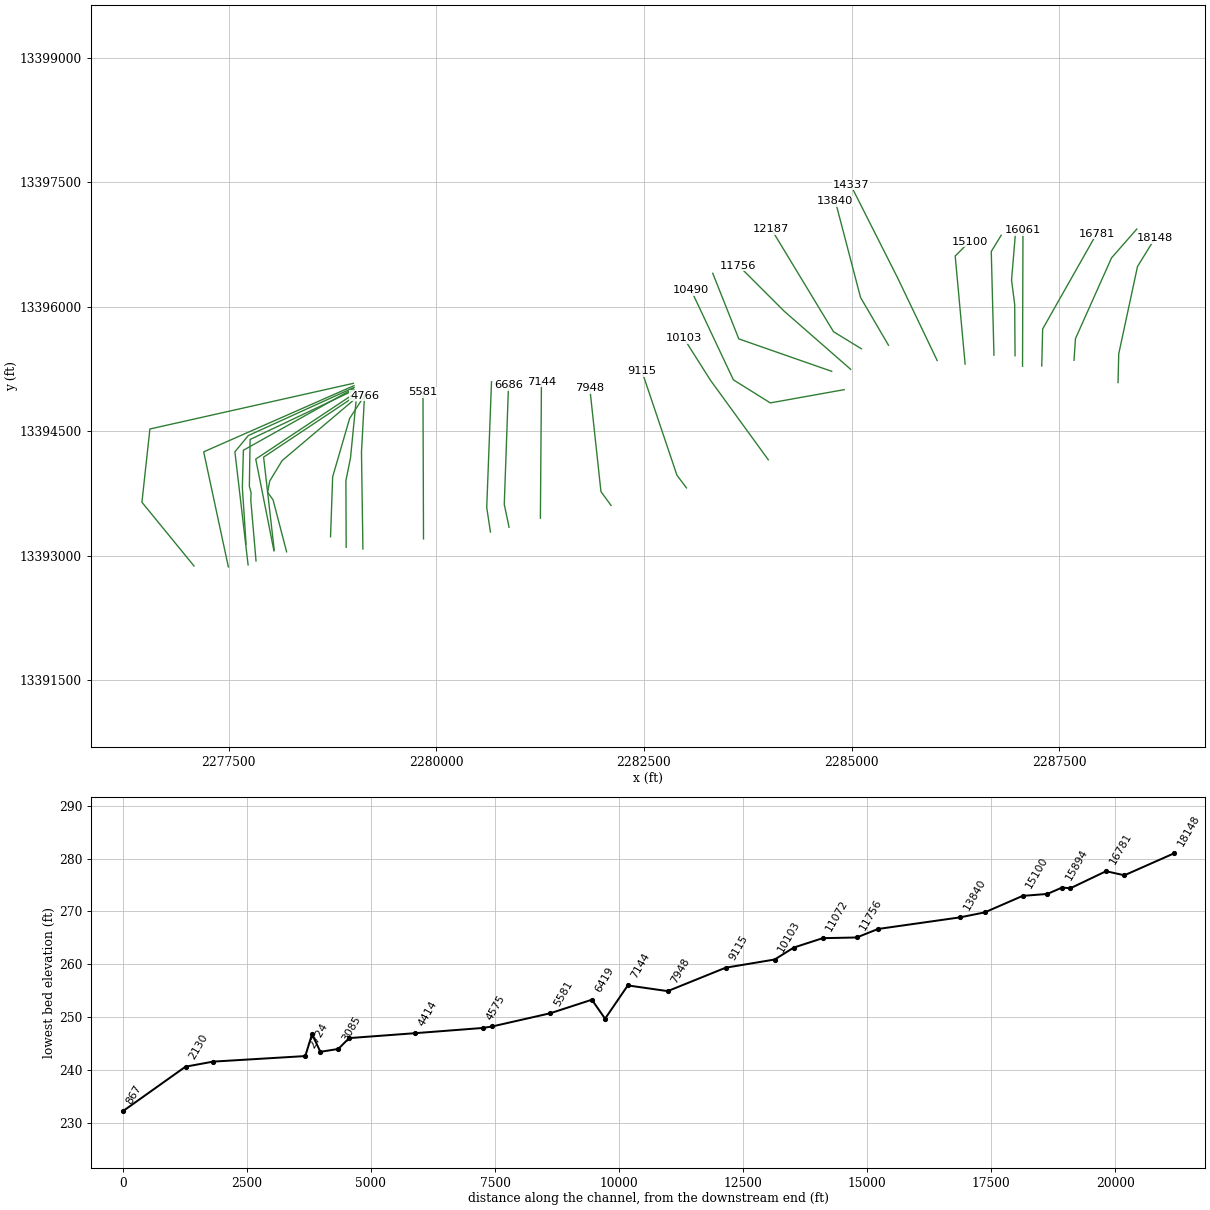
HEC-RAS study EAST FORK SALT CREEK.prj: EAST FORK SALT CREEK Base Level Engineering

--- EAST FORK SALT CREEK.g01 (geometry) --- (continued)

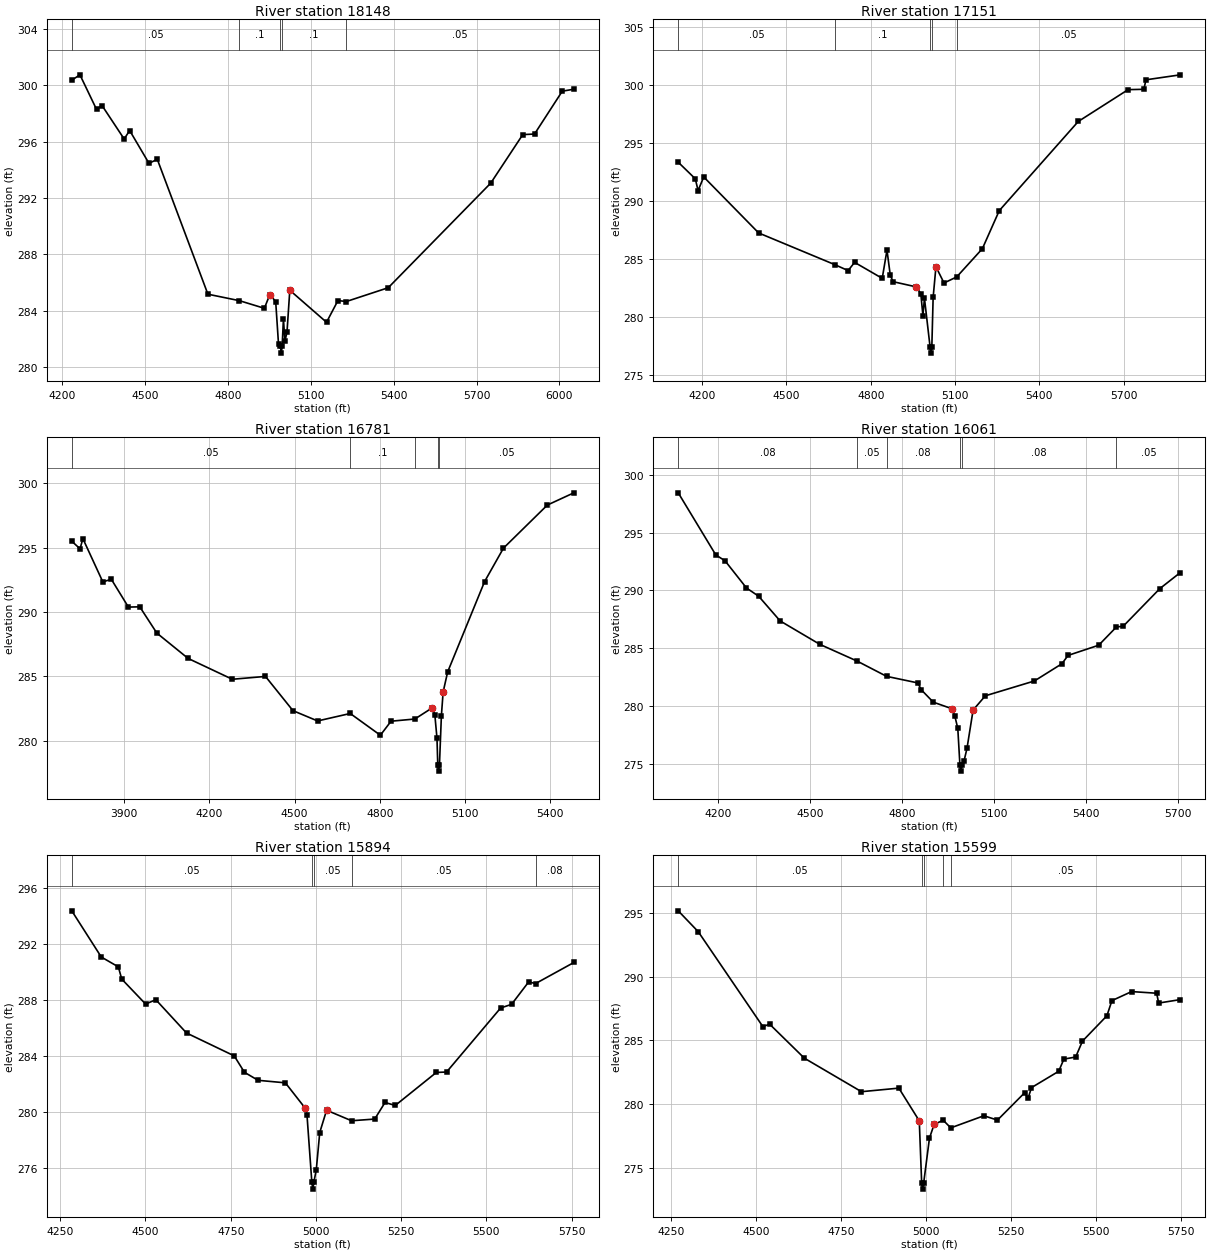
Type RM Length L Ch R = 1 ,18148   ,997,997,997
BEGIN DESCRIPTION:
EAST FORK SALT CREEK 13.0
END DESCRIPTION:
XS GIS Cut Line= 4
      2288205.43     13395087.24      2288214.11     13395434.42
       2288439.8     13396484.77      2288647.71     13396822.61
#Sta/Elev= 30
  4234.1  300.35  4263.7  300.73  4323.7  298.28  4343.8  298.55  4423.8  296.18
  4443.8  296.78  4513.8  294.45  4543.8  294.74  4727.1  285.17  4841.3  284.71
  4931.6  284.17  4951.3  285.14  4972.6  284.65  4982.8  281.64    4990  281.49
  4992.8  280.99    4996  281.49  5000.7  283.43  5005.8  281.83  5013.5  282.47
  5023.7  285.45  5156.7  283.18  5198.1  284.72  5228.3  284.65  5380.3  285.63
  5751.5  293.05  5867.4  296.49    5910  296.53  6010.5  299.57  6052.4  299.71
#Mann= 5 ,-1 , 0
  4234.1     .05       0  4841.3      .1       0    4990     .07       0
    4996      .1       0  5228.3     .05       0
Bank Sta=4951.3,5023.7
XS Rating Curve= 0 ,0
Exp/Cntr=0.3,0.1

Type RM Length L Ch R = 1 ,17151   ,370,370,370
BEGIN DESCRIPTION:
EAST FORK SALT CREEK 12.0
END DESCRIPTION:
XS GIS Cut Line= 4
      2287675.91     13395356.31      2287693.27     13395616.71
       2288127.3     13396588.93      2288431.15     13396936.19
#Sta/Elev= 30
  4114.7  293.34  4175.4  291.91  4185.4  290.89  4205.4  292.07    4401  287.23
  4671.3   284.5  4719.3  283.98  4742.5  284.69  4840.8  283.31  4857.7  285.75
  4869.5  283.57  4879.6  283.02  4962.4  282.57  4978.2  281.98  4985.6  280.09
  4991.1  281.58  5011.3  277.35    5014  276.85  5017.3  277.35    5022  281.66
    5032  284.31  5060.7  282.91  5105.8  283.43  5197.2  285.87  5257.4  289.16
  5538.5  296.86    5716  299.61    5772  299.64  5779.6  300.46  5901.8  300.89
#Mann= 5 ,-1 , 0
  4114.7     .05       0  4671.3      .1       0  5011.3     .07       0
  5017.3      .1       0  5105.8     .05       0
Bank Sta=4962.4,5032
XS Rating Curve= 0 ,0
Exp/Cntr=0.3,0.1

Type RM Length L Ch R = 1 ,16781   ,720,720,720
BEGIN DESCRIPTION:
EAST FORK SALT CREEK 11.0
END DESCRIPTION:
XS GIS Cut Line= 3
      2287287.41     13395287.73      2287298.26     13395732.64
      2287949.01      13396882.3
#Sta/Elev= 30
  3716.4  295.49  3745.5   294.9  3755.5  295.69  3825.6  292.33  3855.6  292.53
  3915.6  290.37  3955.6  290.39  4015.6  288.35  4125.6  286.38  4281.2  284.76
  4397.8  284.98  4494.5  282.32  4581.1  281.52  4695.9   282.1  4801.9  280.41
  4839.5   281.5  4923.2  281.67  4985.2  282.55  4993.6  281.97  5001.1  280.17
  5003.8  278.12  5006.6  277.62  5009.8  278.12  5016.6  281.94  5022.7  283.77
  5038.6  285.33  5168.5  292.35  5234.9  294.95  5389.3   298.3  5482.5  299.25
#Mann= 5 ,-1 , 0
  3716.4     .05       0  4695.9      .1       0  4923.2     .05       0
  5003.8     .03       0  5009.8     .05       0
Bank Sta=4985.2,5022.7
XS Rating Curve= 0 ,0
Exp/Cntr=0.3,0.1

Type RM Length L Ch R = 1 ,16061   ,167,167,167
BEGIN DESCRIPTION:
Mapping XS 6d620c51
END DESCRIPTION:
XS GIS Cut Line= 2
      2287056.24     13395284.14      2287061.45     13396923.33
#Sta/Elev= 30
  4069.4  298.44  4192.1  293.07  4222.1  292.57  4292.1  290.22  4332.1   289.5
  4402.1  287.37  4532.1  285.34  4653.4   283.9  4749.7  282.58  4852.1  282.01
  4862.1  281.44  4902.1  280.35  4962.1  279.79  4972.1  279.18  4982.1  278.09
  4989.1  274.89  4991.9  274.39  4995.1  274.89  5002.1  275.23  5012.1  276.35
  5032.1  279.67  5072.1   280.9  5232.1  282.18  5322.1  283.67  5342.1  284.39
  5442.1  285.27  5500.1  286.85  5522.1  286.91  5642.1  290.17  5708.6  291.55
#Mann= 6 ,-1 , 0
  4069.4     .08       0  4653.4     .05       0  4749.7     .08       0
  4989.1     .07       0  4995.1     .08       0  5500.1     .05       0
Bank Sta=4962.1,5032.1
XS Rating Curve= 0 ,0
Exp/Cntr=0.3,0.1

Type RM Length L Ch R = 1 ,15894   ,295,295,295
BEGIN DESCRIPTION:
EAST FORK SALT CREEK 10.0
END DESCRIPTION:
XS GIS Cut Line= 4
      2286966.09      13395410.3      2286961.87     13396026.41
      2286923.89     13396321.82      2286970.32     13396878.92
#Sta/Elev= 30
  4283.7  294.35  4370.3  291.06  4420.3  290.36  4430.3  289.49  4500.3  287.71
  4530.3  288.02  4620.3  285.65  4760.3  284.02  4790.3  282.85  4830.3  282.28
  4910.4   282.1  4968.7  280.29  4973.7  279.84    4988  275.03  4990.8  274.53
    4994  275.03  5001.1  275.92  5011.2  278.56  5031.3  280.15  5104.5   279.4
  5172.5  279.52  5202.7   280.7  5232.8  280.49  5353.2  282.84  5383.3  282.87
  5541.9  287.43    5574  287.69  5624.2  289.29  5644.4  289.17  5756.7  290.67
#Mann= 5 ,-1 , 0
  4283.7     .05       0    4988     .07       0    4994     .05       0
  5104.5     .05       0  5644.4     .08       0
Bank Sta=4968.7,5031.3
XS Rating Curve= 0 ,0
Exp/Cntr=0.3,0.1

Type RM Length L Ch R = 1 ,15599   ,499,499,499
BEGIN DESCRIPTION:
EAST FORK SALT CREEK 9.0
END DESCRIPTION:
XS GIS Cut Line= 3
      2286712.32     13395417.94      2286679.77      13396665.8
      2286799.14     13396861.13
#Sta/Elev= 30
  4270.7  295.17  4329.6  293.53  4519.7  286.08  4539.7  286.27  4641.8   283.6
  4809.8  280.97  4919.8  281.25  4979.9  278.68  4986.9  273.82  4989.6  273.32
  4992.9  273.82  5009.9  277.33  5023.6   278.4  5050.2  278.73  5072.6  278.13
  5169.9  279.08  5209.9  278.74    5290  280.89    5300  280.45    5310  281.29
    5390  282.57  5405.4  283.53    5440  283.69    5460  284.94  5531.9  286.93
  5546.7  288.12  5604.7  288.83  5678.2   288.7  5684.3  287.93  5747.9   288.2
#Mann= 5 ,-1 , 0
  4270.7     .05       0  4986.9     .03       0  4992.9     .05       0
  5050.2      .1       0  5072.6     .05       0
Bank Sta=4979.9,5023.6
XS Rating Curve= 0 ,0
Exp/Cntr=0.3,0.1

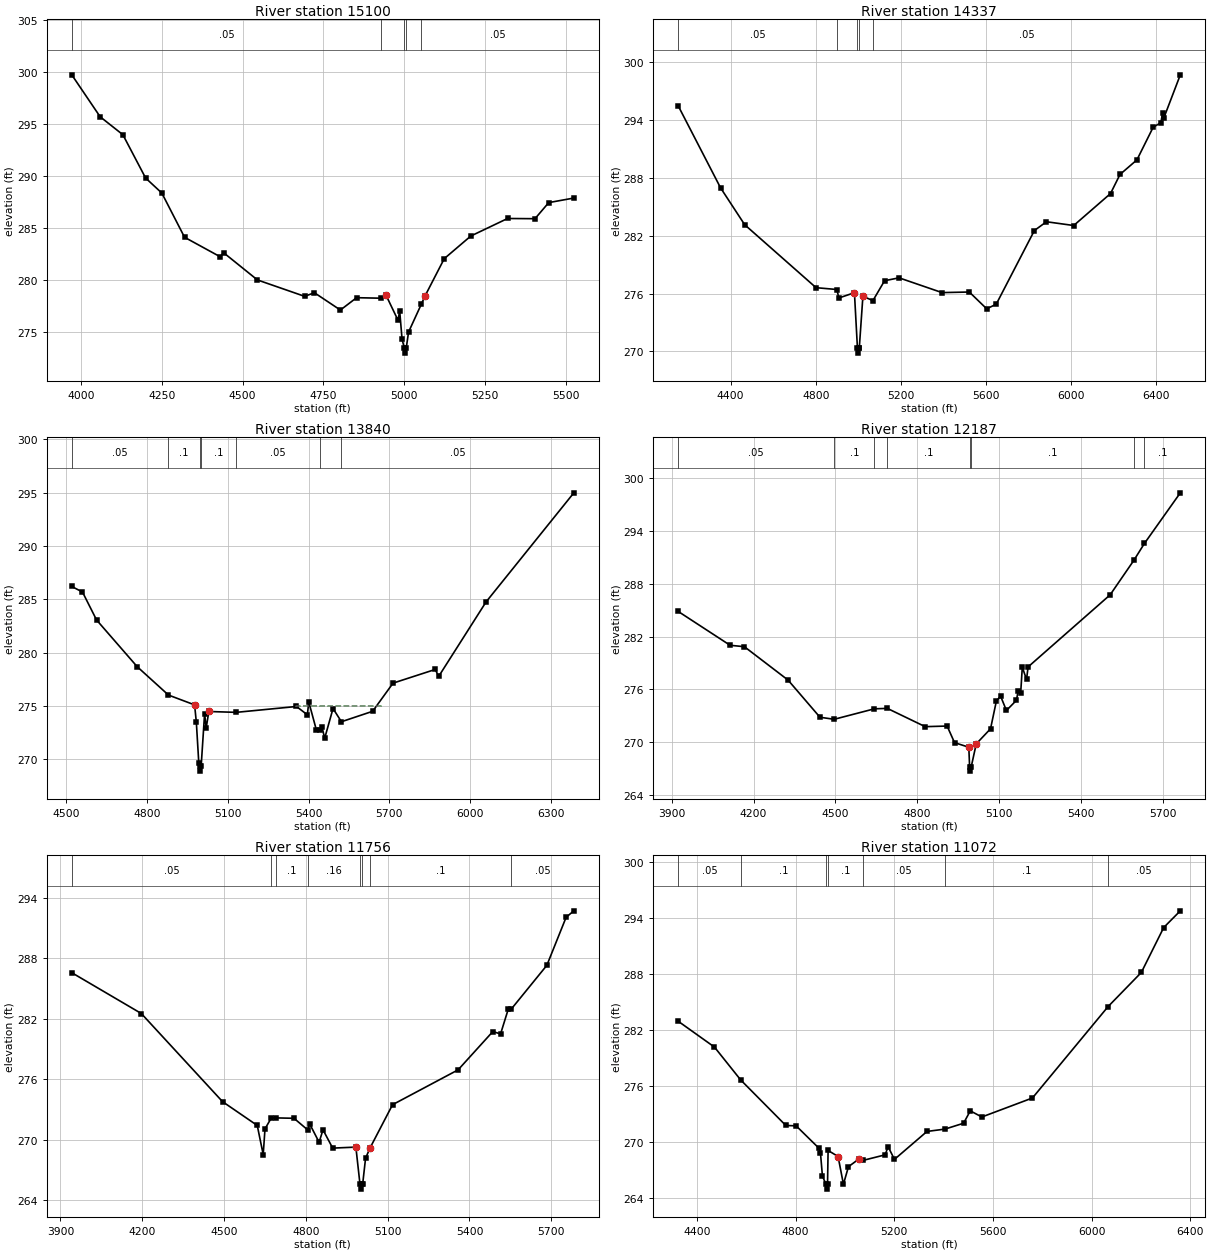
Type RM Length L Ch R = 1 ,15100   ,763,763,763
BEGIN DESCRIPTION:
EAST FORK SALT CREEK 8.0
END DESCRIPTION:
XS GIS Cut Line= 3
       2286365.1     13395309.44      2286245.74     13396611.54
      2286419.36     13396785.17
#Sta/Elev= 30
  3971.7  299.76  4059.5  295.72  4129.8  293.99  4200.1  289.82  4250.3  288.37
  4320.6  284.11    4431  282.23  4441.1  282.63    4546     280  4692.1  278.42
  4722.2  278.77  4802.6   277.1  4852.8  278.29  4929.3  278.24  4943.2  278.57
    4981  276.11    4986  277.04  4993.4  274.29  5000.4  273.45  5003.2  272.95
  5006.4  273.45  5013.5  274.98  5053.1  277.67  5063.7  278.41  5123.9  282.05
    5206  284.23  5319.8  285.92  5404.6   285.9  5447.1  287.45  5524.8  287.89
#Mann= 5 ,-1 , 0
  3971.7     .05       0  4929.3      .1       0  5000.4     .07       0
  5006.4      .1       0  5053.1     .05       0
Bank Sta=4943.2,5063.7
XS Rating Curve= 0 ,0
Exp/Cntr=0.3,0.1

Type RM Length L Ch R = 1 ,14337   ,497,497,497
BEGIN DESCRIPTION:
EAST FORK SALT CREEK 7.0
END DESCRIPTION:
XS GIS Cut Line= 3
      2286028.74     13395352.83       2285551.3     13396351.13
      2284987.05     13397468.77
#Sta/Elev= 30
  4153.7  295.44  4352.6  286.95    4466  283.13  4801.1  276.61  4899.2  276.42
  4907.9  275.54  4981.4  276.09  4995.6  270.33  4998.3  269.83  5001.6  270.33
  5004.1  270.33  5021.2  275.72  5068.3  275.27    5123  277.33    5191  277.63
  5392.9   276.1  5521.1  276.16  5602.8  274.42  5647.6   274.9  5826.8  282.53
  5883.4  283.44  6011.6  283.05  6184.4  286.36    6229  288.34  6308.5  289.85
    6385  293.24  6420.5  293.69  6429.6  294.71  6435.2  294.21  6512.3  298.66
#Mann= 5 ,-1 , 0
  4153.7     .05       0  4899.2      .1       0  4995.6     .07       0
  5001.6      .1       0  5068.3     .05       0
#XS Ineff= 1 ,-1
  5191.5 5739.76   277.6
Permanent Ineff=
       F
Bank Sta=4981.4,5021.2
XS Rating Curve= 0 ,0
Exp/Cntr=0.3,0.1

Type RM Length L Ch R = 1 ,13840   ,1653,1653,1653
BEGIN DESCRIPTION:
EAST FORK SALT CREEK 6.0
END DESCRIPTION:
XS GIS Cut Line= 3
      2285442.77     13395537.35      2285106.42     13396112.41
      2284802.86     13397272.45
#Sta/Elev= 30
  4520.2   286.2    4560  285.68  4612.3  283.06  4763.3  278.68  4879.5  276.02
  4976.5   275.1    4983  273.47  4992.2  269.62    4995  269.39  4997.8  268.89
    5001  269.39  5013.7  274.29  5019.5  272.93  5029.4  274.48    5131   274.4
  5355.1  274.95  5395.5  274.17  5400.7  275.38  5428.7  272.77  5441.2  272.73
  5449.4  273.06  5459.8  271.97  5490.8  274.76    5522  273.52  5638.1   274.5
  5713.8  277.14  5870.3  278.42  5883.6  277.78  6059.3  284.75  6385.5  294.98
#Mann= 7 ,-1 , 0
  4520.2     .05       0  4879.5      .1       0    4995     .07       0
    5001      .1       0    5131     .05       0  5441.2      .1       0
    5522     .05       0
#XS Ineff= 1 ,-1
 5354.55 5672.73  275.03
Permanent Ineff=
       F
Bank Sta=4976.5,5029.4
XS Rating Curve= 0 ,0
Exp/Cntr=0.3,0.1

Type RM Length L Ch R = 1 ,12187   ,431,431,431
BEGIN DESCRIPTION:
EAST FORK SALT CREEK 5.0
END DESCRIPTION:
XS GIS Cut Line= 3
       2285117.3      13395493.9       2284780.9     13395700.09
      2284032.45     13396936.66
#Sta/Elev= 30
  3924.1  284.86  4114.3  281.01  4166.5  280.85  4326.6  277.05  4443.5  272.82
  4495.7  272.59  4642.8  273.78  4690.3  273.83  4829.2  271.75  4909.5  271.82
  4936.7  269.93    4989  269.41  4991.9  267.19  4994.6  266.69  4997.9  267.19
  5016.2  269.79  5068.6  271.51  5089.9  274.65  5105.4  275.23  5126.8  273.59
  5163.6  274.75  5169.5  275.78  5179.1  275.57    5185  278.52  5200.5  277.12
  5206.3  278.55  5506.9  286.75  5594.1  290.69  5632.6   292.6  5764.1  298.36
#Mann= 8 ,-1 , 0
  3924.1     .05       0  4495.7      .1       0  4642.8     .05       0
  4690.3      .1       0  4991.9     .07       0  4997.9      .1       0
  5594.1     .05       0  5632.6      .1       0
Bank Sta=4989,5016.2
XS Rating Curve= 0 ,0
Exp/Cntr=0.3,0.1

Type RM Length L Ch R = 1 ,11756   ,684,684,684
BEGIN DESCRIPTION:
EAST FORK SALT CREEK 4.0
END DESCRIPTION:
XS GIS Cut Line= 3
      2284987.74     13395246.84      2284187.72     13395946.85
      2283637.69     13396496.89
#Sta/Elev= 30
  3941.7  286.56  4196.6  282.51  4494.6  273.76  4621.8   271.4  4643.6  268.51
  4650.2  271.06  4673.4  272.15    4690  272.15  4756.5  272.11  4807.5  270.94
  4813.5  271.58  4848.6  269.73  4862.8  270.97  4898.4  269.15  4983.4  269.25
  4998.4  265.58  5001.2  265.08  5004.4  265.58  5008.3  265.58  5018.9  268.14
    5035  269.15  5117.9  273.46  5358.3  276.92  5485.6  280.72  5513.9  280.48
  5542.1  282.94  5552.9  282.94  5683.6  287.29  5754.3  292.06  5782.6   292.7
#Mann= 8 ,-1 , 0
  3941.7     .05       0  4673.4     .16       0    4690      .1       0
  4807.5     .16       0  4998.4     .07       0  5004.4     .16       0
    5035      .1       0  5552.9     .05       0
Bank Sta=4983.4,5035
XS Rating Curve= 0 ,0
Exp/Cntr=0.3,0.1

Type RM Length L Ch R = 1 ,11072   ,582,582,582
BEGIN DESCRIPTION:
EAST FORK SALT CREEK 3.0
END DESCRIPTION:
XS GIS Cut Line= 3
      2284759.19     13395222.66      2283641.57     13395613.28
      2283327.62     13396403.59
#Sta/Elev= 30
  4324.7  282.96  4471.5  280.19  4577.6  276.67  4760.6  271.78  4802.4  271.74
  4895.6  269.32  4900.9  268.86  4908.9  266.36  4923.6  265.45  4926.4  264.95
  4929.6  265.45  4931.9   269.1  4972.4  268.45    4994  265.47  5014.4  267.36
  5057.2  268.19  5074.4  268.04  5163.1  268.63    5175  269.51  5200.7  268.14
  5332.6  271.14  5405.3  271.39  5480.9  272.02    5508  273.35  5554.9  272.69
  5759.9  274.73  6066.5  284.54  6201.1   288.2  6291.8  293.02    6359  294.81
#Mann= 7 ,-1 , 0
  4324.7     .05       0  4577.6      .1       0  4923.6     .07       0
  4929.6      .1       0  5074.4     .05       0  5405.3      .1       0
  6066.5     .05       0
Bank Sta=4972.4,5057.2
XS Rating Curve= 0 ,0
Exp/Cntr=0.3,0.1

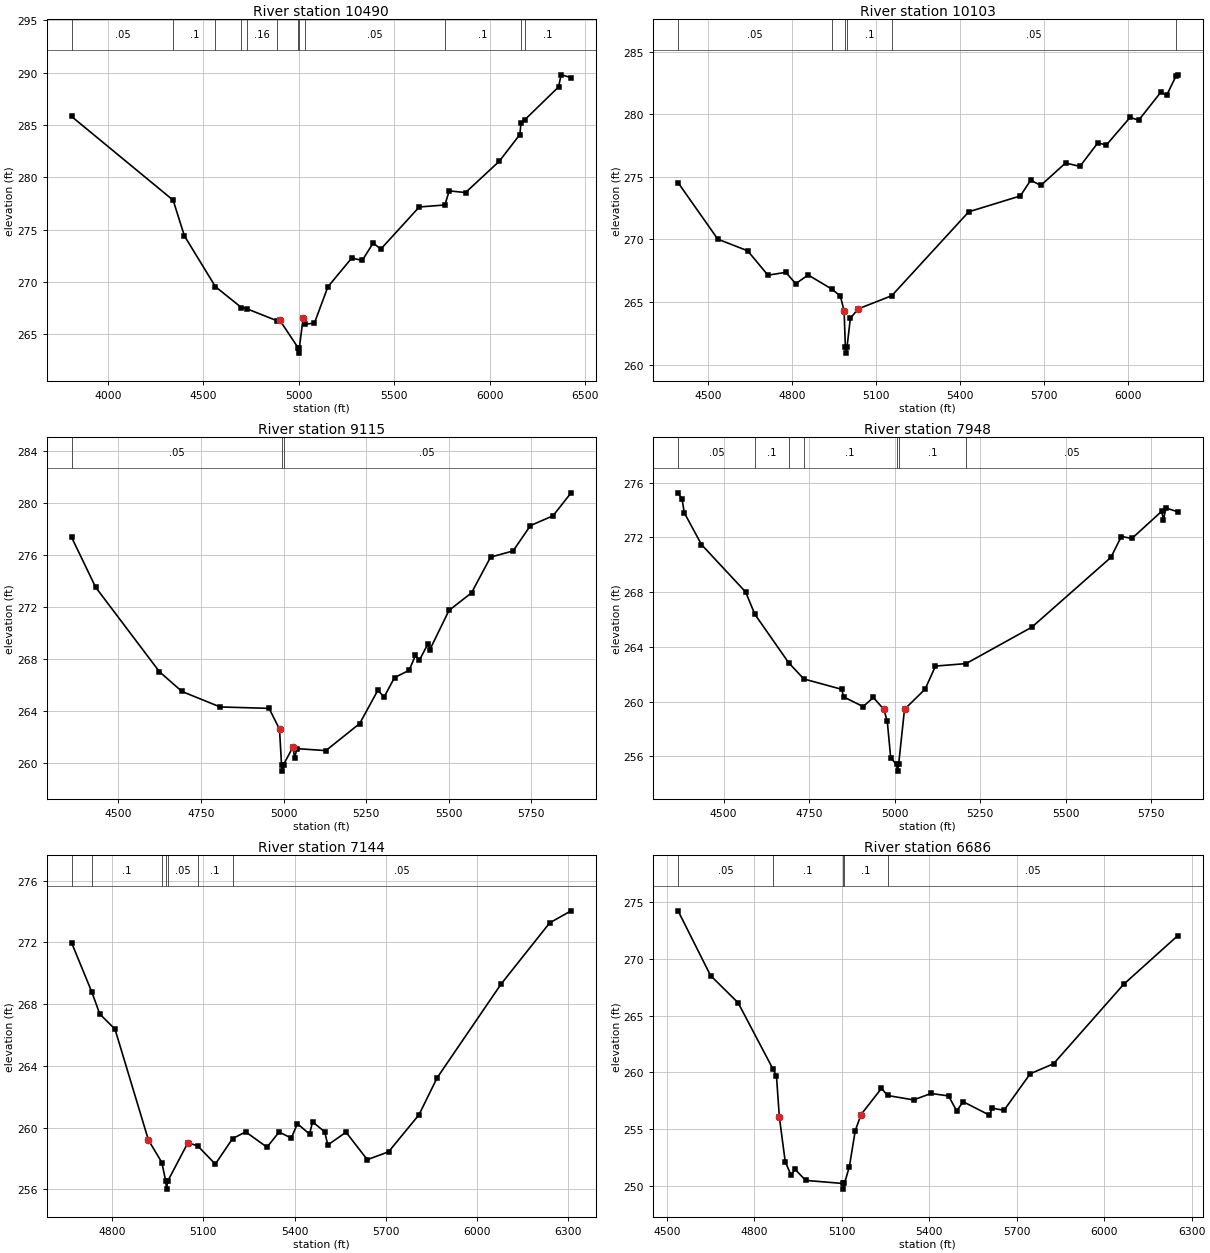
Type RM Length L Ch R = 1 ,10490   ,387,387,387
BEGIN DESCRIPTION:
Mapping XS 44c00b69
END DESCRIPTION:
XS GIS Cut Line= 4
      2284909.56       13395002.      2284020.65     13394842.28
      2283576.21     13395120.06      2283069.28      13396196.4
#Sta/Elev= 30
    3809  285.82  4341.3  277.81  4400.2   274.4  4562.7  269.54    4699  267.54
  4730.6   267.4  4884.9  266.28  4899.2  266.35  4996.4  263.68  4999.2  263.18
  5002.4  263.68  5022.2  266.51  5034.6  265.96  5081.2  266.04  5151.9  269.52
  5276.9  272.27  5332.2  272.05  5389.1  273.71  5429.2  273.13  5630.6  277.16
  5764.7  277.35  5787.6   278.7  5873.2  278.54  6050.7  281.55  6157.7  284.09
  6163.3  285.16  6182.4  285.48  6360.2  288.64  6373.9   289.8    6426  289.54
#Mann= 12 ,-1 , 0
    3809     .05       0  4341.3      .1       0  4562.7     .16       0
    4699      .1       0  4730.6     .16       0  4884.9      .1       0
  4996.4     .07       0  5002.4      .1       0  5034.6     .05       0
  5764.7      .1       0  6163.3     .05       0  6182.4      .1       0
Bank Sta=4899.2,5022.2
XS Rating Curve= 0 ,0
Exp/Cntr=0.3,0.1

Type RM Length L Ch R = 1 ,10103   ,988,988,988
BEGIN DESCRIPTION:
EAST FORK SALT CREEK 2.0
END DESCRIPTION:
XS GIS Cut Line= 3
      2283996.37     13394157.29      2283299.43     13395116.37
      2282979.71     13395621.54
#Sta/Elev= 30
  4393.3  274.54  4535.3  270.02  4641.9  269.09  4714.2  267.14  4777.9  267.37
  4813.5  266.46  4857.6  267.16  4941.5  266.04  4972.7  265.48  4986.1  264.28
  4990.6  261.41  4993.3  260.91  4996.6  261.41  5008.3  263.68  5035.6  264.44
  5156.2   265.5  5431.1  272.21  5615.5  273.48  5651.9  274.73  5688.4  274.32
  5776.5  276.11    5828  275.84  5891.8  277.72  5922.4  277.55  6007.1  279.76
  6037.6  279.53  6116.4  281.76  6137.6  281.53  6170.2  283.03  6176.7  283.16
#Mann= 6 ,-1 , 0
  4393.3     .05       0  4941.5      .1       0  4990.6     .07       0
  4996.6      .1       0  5156.2     .05       0  6170.2      .1       0
Bank Sta=4986.1,5035.6
XS Rating Curve= 0 ,0
Exp/Cntr=0.3,0.1

Type RM Length L Ch R = 1 ,9115    ,1167,1167,1167
BEGIN DESCRIPTION:
Mapping XS dec490b3
END DESCRIPTION:
XS GIS Cut Line= 3
      2283011.68     13393818.39      2282896.61     13393971.83
      2282475.13     13395223.47
#Sta/Elev= 30
  4357.8  277.37  4430.9  273.51    4624  267.01  4692.2  265.49  4807.7   264.3
  4955.9  264.19  4987.5  262.59  4993.6  259.86  4996.4  259.36  4999.6  259.86
  5028.1  261.21  5033.4  260.39  5040.3  261.09  5127.9  260.94  5230.2  263.02
  5285.4  265.59  5304.1  265.06  5335.7  266.56  5379.9  267.12    5399  268.26
  5411.3  267.92  5437.6  269.18  5442.8  268.71  5500.6  271.73  5568.8  273.08
  5626.5  275.83  5694.8  276.31  5747.2  278.26  5815.5  279.01  5870.3  280.78
#Mann= 3 ,-1 , 0
  4357.8     .05       0  4993.6     .03       0  4999.6     .05       0
Bank Sta=4987.5,5028.1
XS Rating Curve= 0 ,0
Exp/Cntr=0.3,0.1

Type RM Length L Ch R = 1 ,7948    ,804,804,804
BEGIN DESCRIPTION:
Mapping XS 8d5f6e8a
END DESCRIPTION:
XS GIS Cut Line= 3
      2282103.74     13393607.37      2281982.25     13393773.61
      2281847.97      13395020.5
#Sta/Elev= 30
  4367.1  275.25  4378.9  274.77  4385.4  273.79  4435.6  271.47  4564.6  268.01
  4591.6  266.38  4690.5  262.84  4734.7  261.66  4845.8   260.9  4850.8  260.35
  4908.2  259.64  4937.8  260.31  4968.5  259.44  4978.6  258.56  4988.6  255.88
  5005.8  255.43  5008.5  254.93  5011.8  255.43  5028.9  259.44  5089.2  260.92
  5119.4   262.6  5208.6  262.78    5401  265.44  5632.3  270.54  5662.5  272.06
  5693.5  271.92  5780.5   273.9  5785.5   273.3  5793.3  274.14  5827.1  273.87
#Mann= 7 ,-1 , 0
  4367.1     .05       0  4591.6      .1       0  4690.5     .05       0
  4734.7      .1       0  5005.8     .07       0  5011.8      .1       0
  5208.6     .05       0
Bank Sta=4968.5,5028.9
XS Rating Curve= 0 ,0
Exp/Cntr=0.3,0.1

Type RM Length L Ch R = 1 ,7144    ,458,458,458
BEGIN DESCRIPTION:
Mapping XS 6025f47c
END DESCRIPTION:
XS GIS Cut Line= 2
      2281253.32     13393453.87      2281266.11     13395097.22
#Sta/Elev= 30
  4666.2  271.99  4733.1  268.78  4759.2  267.36  4809.2  266.38  4919.2  259.19
  4963.5  257.73  4976.2  256.51  4978.9  256.01  4982.2  256.51  5049.2  259.02
  5081.6  258.81  5139.2  257.63  5196.2  259.29  5239.2  259.72  5309.2  258.73
  5349.2  259.71  5389.2  259.32  5409.2  260.25  5449.2  259.58  5459.2  260.37
  5499.2  259.72  5509.2  258.87  5569.2   259.7  5639.2  257.92  5709.2  258.43
  5809.2  260.83    5869  263.23  6079.2   269.3  6239.2  273.27  6309.6  274.05
#Mann= 7 ,-1 , 0
  4666.2     .05       0  4733.1      .1       0  4963.5     .05       0
  4976.2    .035       0  4982.2     .05       0  5081.6      .1       0
  5196.2     .05       0
Bank Sta=4919.2,5049.2
XS Rating Curve= 0 ,0
Exp/Cntr=0.3,0.1

Type RM Length L Ch R = 1 ,6686    ,267,267,267
BEGIN DESCRIPTION:
Mapping XS 64251079
END DESCRIPTION:
XS GIS Cut Line= 3
      2280876.07     13393345.22      2280818.53     13393620.15
      2280869.67     13395052.15
#Sta/Elev= 30
  4538.2  274.26  4649.7  268.55  4744.2  266.15  4863.1  260.34  4875.8   259.7
  4885.8  256.04  4905.8  252.14  4925.9  250.93  4938.8  251.48  4975.9  250.48
    5103  250.21  5105.7  249.71    5109  250.21    5126   251.7    5146  254.86
    5166  256.29  5236.1   258.6  5256.9  257.97  5346.1  257.58  5406.2  258.15
  5466.2  257.93  5494.1  256.61  5516.2  257.42  5606.3  256.24  5616.3  256.85
  5656.3  256.66  5746.4  259.89  5826.4  260.77  6066.6  267.77    6252  272.06
#Mann= 5 ,-1 , 0
  4538.2     .05       0  4863.1      .1       0    5103     .07       0
    5109      .1       0  5256.9     .05       0
Bank Sta=4885.8,5166
XS Rating Curve= 0 ,0
Exp/Cntr=0.3,0.1

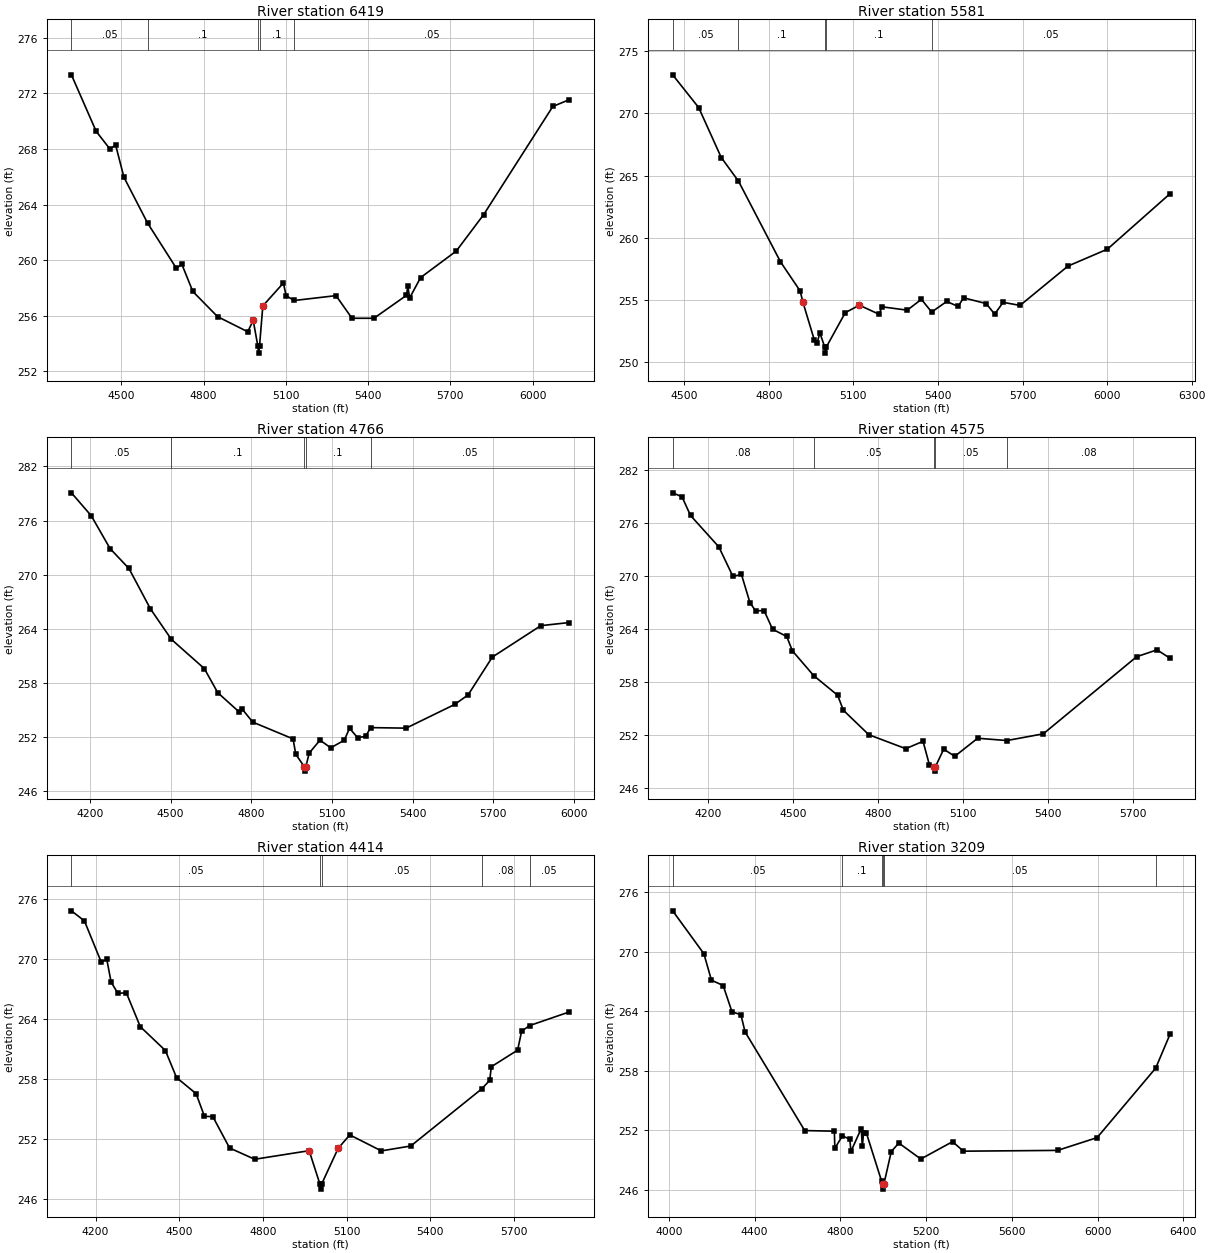
Type RM Length L Ch R = 1 ,6419    ,838,838,838
BEGIN DESCRIPTION:
Mapping XS 97335565
END DESCRIPTION:
XS GIS Cut Line= 3
      2280652.28     13393287.63      2280607.52     13393581.79
      2280665.07     13395097.15
#Sta/Elev= 30
  4318.2  273.34  4408.5  269.27    4459  267.99  4479.3   268.3  4509.6  265.97
  4595.8  262.67  4700.9  259.41  4720.9   259.7  4760.9  257.74    4851  255.93
  4961.1  254.84  4981.1  255.66  4998.1   253.8  5000.8   253.3  5004.1   253.8
  5016.2   256.7  5091.2  258.35  5101.2  257.43    5131  257.09  5283.1  257.44
  5341.3  255.81  5421.4  255.81  5539.9  257.46  5544.9  258.13  5551.5  257.27
  5591.5  258.74  5721.6  260.65  5821.7  263.28  6073.6  271.06  6132.2  271.54
#Mann= 5 ,-1 , 0
  4318.2     .05       0  4595.8      .1       0  4998.1     .07       0
  5004.1      .1       0    5131     .05       0
Bank Sta=4981.1,5016.2
XS Rating Curve= 0 ,0
Exp/Cntr=0.3,0.1

Type RM Length L Ch R = 1 ,5581    ,1167,1167,1167
BEGIN DESCRIPTION:
Mapping XS 87c9ea8d
END DESCRIPTION:
XS GIS Cut Line= 2
      2279846.62     13393204.54      2279840.23     13394969.33
#Sta/Elev= 30
  4458.8  273.09  4551.1  270.46  4631.1  266.45  4692.3  264.55  4841.1  258.08
  4911.1  255.73  4921.1  254.81  4961.1  251.81  4971.1  251.57  4981.1  252.36
  4998.1  251.24  5000.9  250.74  5004.1  251.24  5071.1  253.99  5121.1  254.59
  5191.1  253.86  5201.1  254.46  5291.1  254.19  5341.1  255.06  5377.6  254.04
  5431.1  254.89  5471.1  254.49  5491.1  255.18  5571.1  254.72  5601.1  253.87
  5631.1  254.82  5691.1  254.57  5861.1  257.73  6001.1  259.09  6223.6  263.55
#Mann= 5 ,-1 , 0
  4458.8     .05       0  4692.3      .1       0  4998.1     .07       0
  5004.1      .1       0  5377.6     .05       0
Bank Sta=4921.1,5121.1
XS Rating Curve= 0 ,0
Exp/Cntr=0.3,0.1

Type RM Length L Ch R = 1 ,4766    ,191,191,191
BEGIN DESCRIPTION:
Mapping XS fa6b17
END DESCRIPTION:
XS GIS Cut Line= 3
      2279117.38     13393083.03      2279100.02     13394249.71
      2279136.88      13394930.9
#Sta/Elev= 30
  4131.6  279.07  4205.4  276.53  4275.4  272.89  4345.5  270.69  4425.5  266.21
  4503.2  262.84  4625.5  259.61  4675.5  256.94  4755.5  254.79  4765.5  255.15
  4805.5  253.68  4955.5  251.82  4965.5  250.12    4997  248.75  4999.8  248.25
    5003  248.75  5015.5  250.25  5055.5  251.68  5095.5  250.83  5145.5  251.67
  5165.5  252.99  5195.5  251.95  5225.6  252.11  5243.6  253.07  5375.7  253.01
  5555.9  255.63    5606  256.69  5696.1  260.88  5876.4  264.36  5980.6   264.7
#Mann= 5 ,-1 , 0
  4131.6     .05       0  4503.2      .1       0    4997     .07       0
    5003      .1       0  5243.6     .05       0
Bank Sta=4997,5003
XS Rating Curve= 0 ,0
Exp/Cntr=0.3,0.1

Type RM Length L Ch R = 1 ,4575    ,1366,1366,1366
BEGIN DESCRIPTION:
Mapping XS fa6b178e
END DESCRIPTION:
XS GIS Cut Line= 4
      2278915.99     13393103.83      2278912.52     13393905.96
      2278968.07     13394180.27      2279033.94     13394852.84
#Sta/Elev= 30
  4074.6  279.44  4107.6  278.99  4137.6  276.88  4237.6  273.33  4287.6  269.98
  4317.6  270.21  4347.6  267.02  4367.6  266.09  4397.6  266.12  4427.6  264.01
  4477.6  263.19  4497.6  261.57    4573  258.76  4657.6  256.54  4677.6  254.85
  4767.6  252.08  4898.1   250.5  4959.3  251.33  4981.6  248.69    4997  248.46
  4999.8  247.96    5003  248.46  5032.3  250.44  5071.5  249.64  5152.3  251.68
  5255.5  251.42  5384.3  252.18    5714   260.9  5786.2  261.68  5832.4  260.72
#Mann= 5 ,-1 , 0
  4074.6     .08       0    4573     .05       0    4997     .03       0
    5003     .05       0  5255.5     .08       0
Bank Sta=4997,5003
XS Rating Curve= 0 ,0
Exp/Cntr=0.3,0.1

Type RM Length L Ch R = 1 ,4414    ,1329,1329,1329
BEGIN DESCRIPTION:
Mapping XS fa6b178e
END DESCRIPTION:
XS GIS Cut Line= 4
      2278727.66     13393230.16      2278753.23     13393952.65
      2278957.84       13394656.      2279136.85      13394930.9
#Sta/Elev= 30
  4113.4  274.84  4160.1  273.83  4220.2  269.71  4240.2  269.98  4255.8   267.7
  4280.2  266.57  4310.2  266.64  4360.3  263.24  4450.3  260.85  4490.3  258.14
  4560.4  256.53  4590.4  254.26  4620.4  254.23  4680.5  251.09  4770.5  249.96
  4965.7  250.82  5004.4  247.47  5007.1  246.97  5010.4  247.47  5069.8  251.06
  5111.5   252.4  5224.6   250.8  5330.2  251.29  5584.1     257    5613  257.86
    5619  259.23  5713.1  260.89  5727.7   262.8  5756.3  263.35  5896.9   264.7
#Mann= 5 ,-1 , 0
  4113.4     .05       0  5004.4     .03       0  5010.4     .05       0
  5584.1     .08       0  5756.3     .05       0
Bank Sta=4965.7,5069.8
XS Rating Curve= 0 ,0
Exp/Cntr=0.3,0.1

Type RM Length L Ch R = 1 ,3209    ,218,218,218
BEGIN DESCRIPTION:
Mapping XS 4cef9
END DESCRIPTION:
XS GIS Cut Line= 6
      2278198.86     13393048.86      2278036.09     13393673.87
      2277970.38     13393765.88      2277994.86     13393899.57
       2278144.6     13394146.96      2279012.42     13394882.16
#Sta/Elev= 30
  4017.5  274.13  4163.1   269.8  4198.4  267.13  4253.1  266.59  4294.4  263.93
  4335.8  263.65  4355.3  261.91  4633.7  251.95  4771.9  251.89  4774.4  250.17
  4809.6  251.41  4844.2  251.08  4849.3  249.84  4897.4  252.15  4902.5  250.35
  4908.4  251.73  4920.9  251.74  4992.4  246.85    4997  246.54  4999.8  246.04
    5003  246.54  5037.6  249.83  5072.8  250.69  5175.4  249.08  5323.7  250.83
  5374.3  249.87  5813.7  249.95  5998.3  251.24  6271.7  258.26  6338.9   261.7
#Mann= 6 ,-1 , 0
  4017.5     .05       0  4809.6      .1       0  4992.4     .05       0
    4997     .03       0    5003     .05       0  6271.7     .08       0
Bank Sta=4997,5003
XS Rating Curve= 0 ,0
Exp/Cntr=0.3,0.1

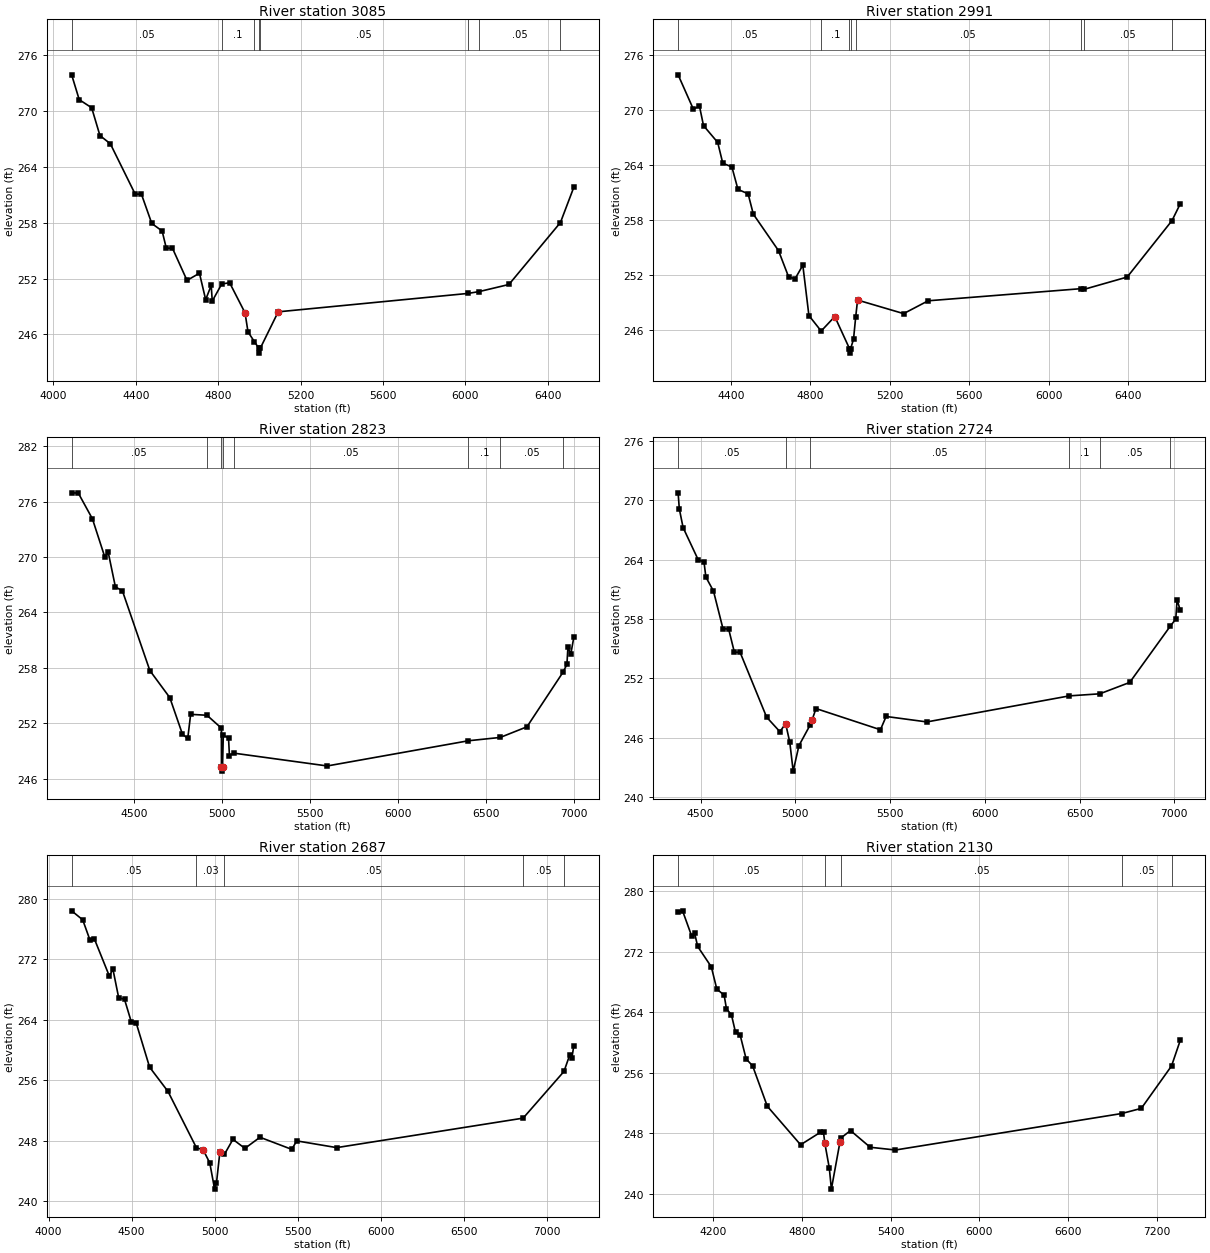
Type RM Length L Ch R = 1 ,3085    ,361,361,361
BEGIN DESCRIPTION:
Mapping XS 4cef98e9
END DESCRIPTION:
XS GIS Cut Line= 3
      2278049.88      13393070.3        2277922.     13394189.23
      2279014.05     13394917.26
#Sta/Elev= 30
  4088.6  273.91  4125.4  271.24  4185.8  270.37    4226  267.38  4276.4   266.5
  4397.2  261.08  4427.3  261.09  4477.7  257.93    4528  257.12  4548.1  255.28
  4578.3  255.26  4648.8  251.81  4709.2  252.58  4739.4  249.74  4766.3  251.27
  4771.4  249.59  4817.4  251.42  4855.7  251.56  4930.6  248.32    4945  246.27
  4975.9  245.23  4998.1  244.49  5000.8  243.99  5004.1  244.49  5091.6  248.43
  6013.9  250.41  6068.3  250.61  6212.1  251.37  6462.2  258.03  6527.3  261.83
#Mann= 8 ,-1 , 0
  4088.6     .05       0  4817.4      .1       0  4975.9     .05       0
  4998.1     .03       0  5004.1     .05       0  6013.9      .1       0
  6068.3     .05       0  6462.2     .08       0
Bank Sta=4930.6,5091.6
XS Rating Curve= 0 ,0
Exp/Cntr=0.3,0.1

Type RM Length L Ch R = 1 ,2991    ,168,168,168
BEGIN DESCRIPTION:
Mapping XS 4cef98e9
END DESCRIPTION:
XS GIS Cut Line= 3
      2278046.37      13393061.6      2277827.61     13394165.77
       2278993.5     13394940.77
#Sta/Elev= 30
  4135.3   273.8    4212  270.05  4242.6  270.39    4263  268.26  4334.3  266.43
  4359.9  264.16  4405.7  263.75  4436.3   261.3  4487.3  260.82  4513.5   258.6
  4640.2  254.62  4691.1  251.75  4723.5  251.55  4762.5  253.03  4793.1  247.54
  4854.7  245.85  4923.2  247.43    4997  243.94  4999.8  243.44    5003  243.94
  5017.4  244.95  5028.3  247.37  5037.8  249.23  5269.5  247.75  5392.8  249.15
  6160.9  250.47  6177.2   250.4  6393.8  251.74  6619.2   257.9  6660.9  259.74
#Mann= 8 ,-1 , 0
  4135.3     .05       0  4854.7      .1       0    4997     .07       0
    5003      .1       0  5028.3     .05       0  6160.9      .1       0
  6177.2     .05       0  6619.2     .08       0
Bank Sta=4923.2,5037.8
XS Rating Curve= 0 ,0
Exp/Cntr=0.3,0.1

Type RM Length L Ch R = 1 ,2823    ,136,136,136
BEGIN DESCRIPTION:
Mapping XS a337306c
END DESCRIPTION:
XS GIS Cut Line= 6
      2277830.92     13392939.06      2277767.96     13393669.97
      2277771.43     13393760.24       2277750.6     13393838.37
      2277759.58     13394401.95      2279013.28     13394996.27
#Sta/Elev= 30
    4145  276.94  4182.9  276.91  4263.2  274.12  4333.5  269.99  4352.8  270.51
  4393.7  266.76  4433.9  266.31  4589.8  257.69  4703.2  254.76  4775.1   250.8
  4805.2  250.34  4821.7  252.95  4914.5  252.85  4996.5  251.46    4997   247.3
  4999.8   246.8    5003   247.3  5007.4  250.69  5037.1  250.39  5042.3  248.49
  5066.1  248.75  5598.4  247.36  6401.8  250.09  6582.5  250.45  6734.2   251.6
  6938.9   257.5  6961.5  258.36  6967.2  260.19  6983.7  259.49  7000.9  261.31
#Mann= 8 ,-1 , 0
    4145     .05       0  4914.5      .1       0    4997     .07       0
    5003      .1       0  5066.1     .05       0  6401.8      .1       0
  6582.5     .05       0  6938.9     .08       0
Bank Sta=4997,5003
XS Rating Curve= 0 ,0
Exp/Cntr=0.3,0.1

Type RM Length L Ch R = 1 ,2724    ,1857,1857,1857
BEGIN DESCRIPTION:
Mapping XS a337306c
END DESCRIPTION:
XS GIS Cut Line= 4
      2277710.99     13393140.64      2277666.24     13393824.77
      2277679.03     13394272.35      2279002.61     13395014.07
#Sta/Elev= 30
  4381.3  270.75  4387.5  269.14  4407.6  267.24  4487.7  263.97  4517.8  263.79
  4527.8  262.24  4567.9  260.83    4618  257.03  4648.1  256.99  4678.2  254.65
  4708.2  254.65  4848.5  248.09  4918.7  246.62  4948.7  247.45  4970.7  245.55
  4988.6  242.64  5018.9  245.21    5079  247.33    5089  247.84    5109  248.96
  5449.1  246.82  5479.1  248.16  5694.3  247.61  6445.9  250.24  6607.1  250.45
  6764.9   251.6  6979.3  257.29    7008     258  7014.8  259.95  7031.9  258.87
#Mann= 6 ,-1 , 0
  4381.3     .05       0  4948.7     .03       0    5079     .05       0
  6445.9      .1       0  6607.1     .05       0  6979.3     .08       0
Bank Sta=4948.7,5089
XS Rating Curve= 0 ,0
Exp/Cntr=0.3,0.1

Type RM Length L Ch R = 1 ,2687    ,557,557,557
BEGIN DESCRIPTION:
Mapping XS 4cef98
END DESCRIPTION:
XS GIS Cut Line= 4
      2277735.49     13392890.72      2277576.72     13394253.17
      2277737.66     13394448.89      2279010.27     13395028.39
#Sta/Elev= 30
  4139.2   278.4  4205.8  277.21  4250.3  274.48  4276.3  274.67  4366.9  269.73
    4387  270.75  4422.3  266.91  4457.5  266.69  4497.7  263.75  4527.9  263.56
  4608.5  257.72  4719.2  254.51  4890.4  247.06  4930.7   246.8  4970.9  245.05
  4999.8  241.59  5011.2  242.42  5031.7  246.51  5059.2   246.2  5110.2  248.17
  5182.3  246.98    5273  248.45  5464.2  246.85  5494.4  247.97    5735  247.08
  6857.4  250.98  7103.3  257.16  7137.8  259.33  7150.6  258.95  7162.6  260.56
#Mann= 5 ,-1 , 0
  4139.2     .05       0  4890.4     .03       0  5059.2     .05       0
  6857.4     .05       0  7103.3     .08       0
Bank Sta=4930.7,5031.7
XS Rating Curve= 0 ,0
Exp/Cntr=0.3,0.1

Type RM Length L Ch R = 1 ,2130    ,1263,1263,1263
BEGIN DESCRIPTION:
Mapping XS a33730
END DESCRIPTION:
XS GIS Cut Line= 3
      2277497.82     13392867.52      2277200.94     13394252.95
      2279009.93     13395049.81
#Sta/Elev= 30
  3964.1  277.21  3994.1   277.4  4055.5  274.08  4075.9  274.41  4096.4  272.69
  4188.4     270  4225.6  267.06  4275.1  266.26  4290.7  264.46  4324.5  263.66
    4352  261.34  4382.7  261.03  4423.6  257.84  4467.7  256.91  4566.8  251.58
  4791.8  246.49  4924.8  248.13  4946.6  248.12  4955.4  246.71  4985.8  243.41
  4999.8  240.63  5057.7  246.85  5067.9  247.44    5129  248.37  5262.2  246.16
  5432.7   245.8  6961.9  250.62  7094.2   251.3  7298.3   256.9  7357.7   260.3
#Mann= 5 ,-1 , 0
  3964.1     .05       0  4955.4     .03       0  5067.9     .05       0
  6961.9     .05       0  7298.3     .08       0
Bank Sta=4955.4,5057.7
XS Rating Curve= 0 ,0
Exp/Cntr=0.3,0.1

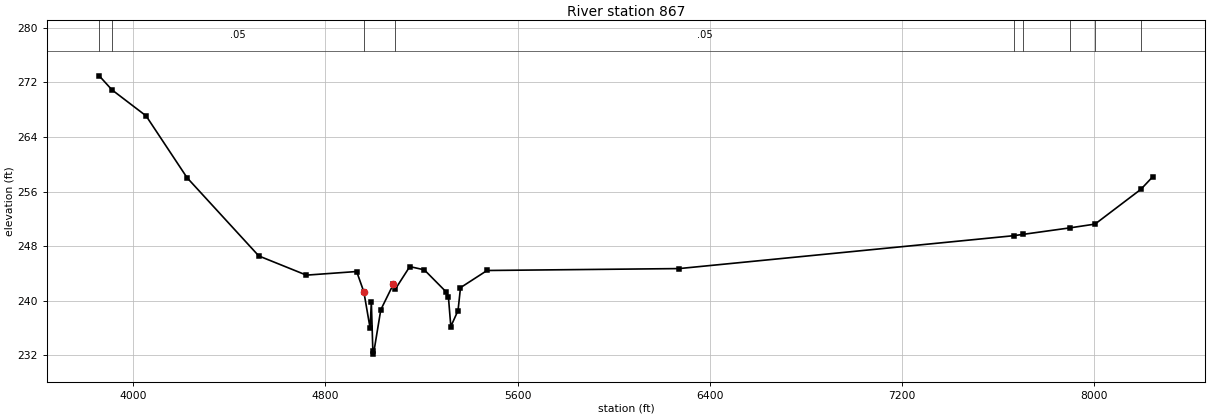
Type RM Length L Ch R = 1 ,867     ,0,0,0
BEGIN DESCRIPTION:
EAST FORK SALT CREEK 1.0
END DESCRIPTION:
XS GIS Cut Line= 4
      2277084.37     13392878.44      2276457.75     13393645.73
      2276553.66     13394528.12      2279002.56       13395078.
#Sta/Elev= 30
  3857.7  272.93  3910.7  270.88  4052.9  267.07  4223.8  258.01  4522.4  246.57
  4720.7  243.76    4930  244.29  4960.1  241.29  4986.1  235.97  4991.1  239.87
  4997.4   232.7  5000.1   232.2  5030.5  238.69  5082.6  242.42  5090.9  241.71
  5151.2  245.01  5211.6  244.54  5302.1  241.33  5312.2  240.57  5322.2  236.24
  5352.2  238.58  5362.5  241.93  5473.1  244.44    6273  244.72  7665.9  249.53
  7704.1  249.72    7901  250.68  8005.4  251.23  8196.4  256.32  8245.8  258.16
#Mann= 9 ,-1 , 0
  3857.7     .05       0  3910.7     .05       0  4960.1     .03       0
  5090.9     .05       0  7665.9      .1       0  7704.1     .05       0
    7901      .1       0  8005.4     .05       0  8196.4     .08       0
Bank Sta=4960.1,5082.6
XS Rating Curve= 0 ,0
Exp/Cntr=0.3,0.1

Chan Stop Cuts=-1
Use User Specified Reach Order=0
Composite Channel Slope=5