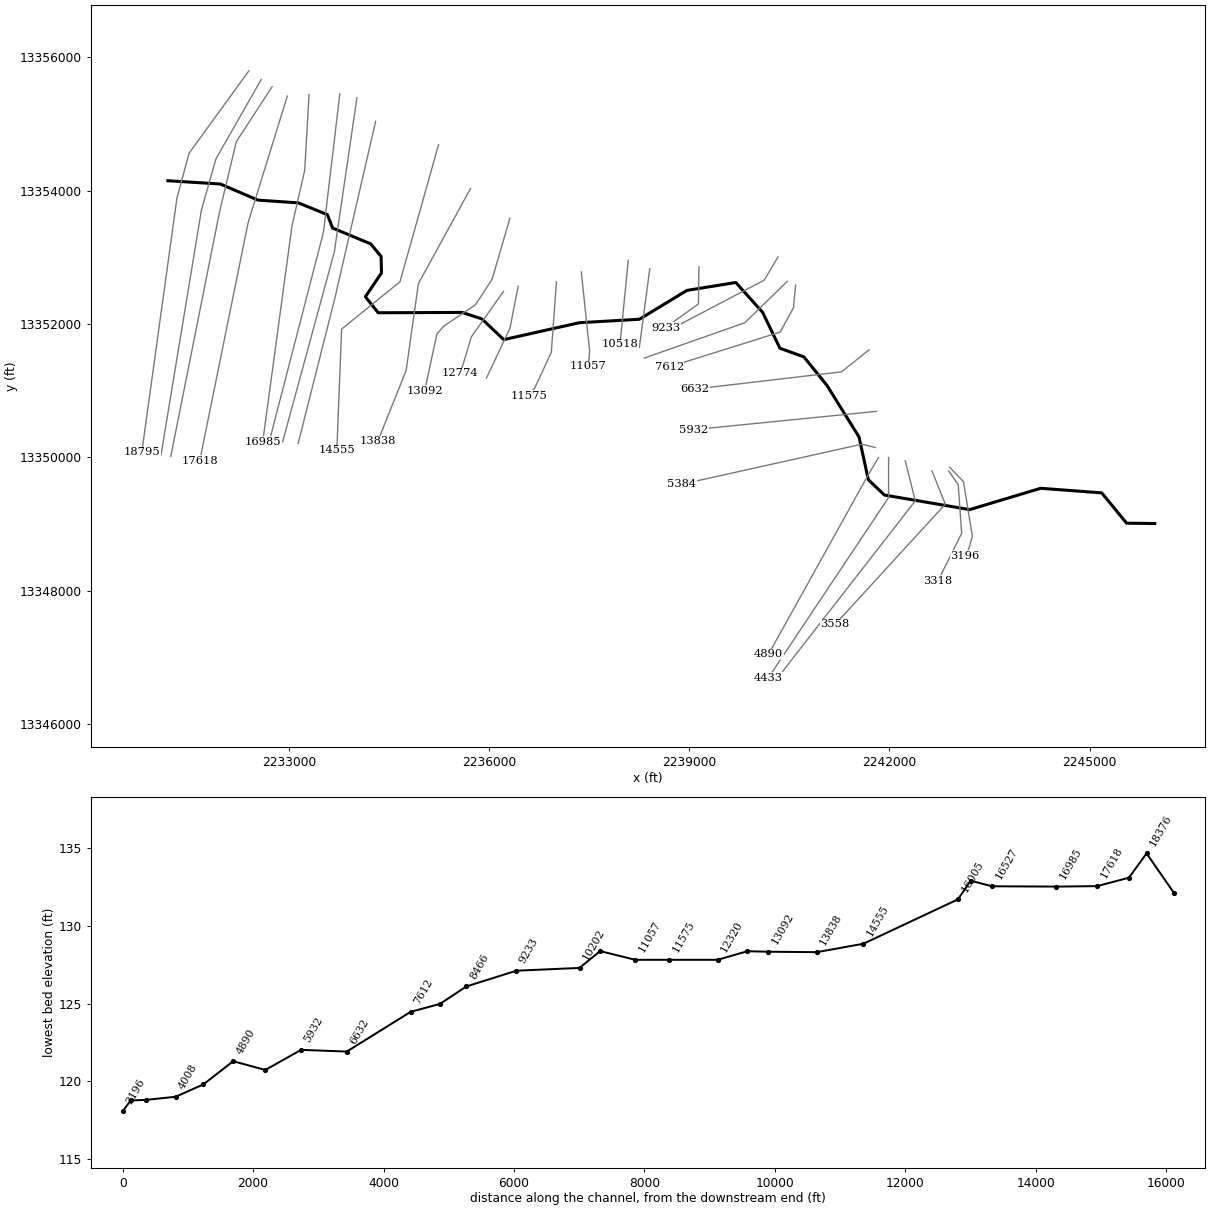
--- OLDS SLOUGH.prj (project) ---

Proj Title=OLDS SLOUGH Base Level Engineering
Current Plan=p01
Default Exp/Contr=0.3,0.1
English Units
Geom File=g01
Flow File=f01
Plan File=p01
Y Axis Title=Elevation
X Axis Title(PF)=Main Channel Distance
X Axis Title(XS)=Station
BEGIN DESCRIPTION:
OLDS SLOUGH
END DESCRIPTION:
DSS Export Rating Curves= 0
DSS Export Rating Curve Sorted= 0
DSS Export Volume Flow Curves= 0
DXF OffsetX= 0
DXF OffsetY= 0
DXF ScaleX= 1
DXF ScaleY= 10

--- OLDS SLOUGH.p01 (plan) ---

Plan Title=Multiple Run
Short Identifier=Multiple
Geom File=g01
Flow File=f01
Subcritical Flow
K Sum by GR= 0
Std Step Tol= 0.01
Critical Tol= 0.01
Num of Std Step Trials= 20
Max Error Tol= 0.3
Flow Tol Ratio= 0.001
Split Flow NTrial= 30
Split Flow Tol= 0.02
Split Flow Ratio= 0.02
Log Output Level= 0
Friction Slope Method= 1
Unsteady Friction Slope Method= 2
Unsteady Bridges Friction Slope Method= 1
Parabolic Critical Depth
Global Vel Dist=  1 , 1 , 1
Global Log Level= 0
CheckData=True
Encroach Param= -1, 0, 0, 0
BEGIN DESCRIPTION:
Multiple Run
END DESCRIPTION:

--- OLDS SLOUGH.f01 (steady flow) ---

Flow Title=Multiple
Program Version=4.10
Number of Profiles= 7
Profile Names=10-year,25-year,50-year,1pct_min,100-year,1pct_plu,500-year
River Rch & RM=OLDS SLOUGH,Reach-1         ,18795
     117     152     178     154     208     281     287
River Rch & RM=OLDS SLOUGH,Reach-1         ,18376
     172     226     269     234     317     428     447
River Rch & RM=OLDS SLOUGH,Reach-1         ,12774
     169     221     262     227     307     415     429
River Rch & RM=OLDS SLOUGH,Reach-1         ,8466
     301     401     487     429     581     785     838
River Rch & RM=OLDS SLOUGH,Reach-1         ,4433
     357     484     586     519     702     950    1026
River Rch & RM=OLDS SLOUGH,Reach-1         ,4008
     384     524     637     567     766    1036    1128
Boundary for River Rch & Prof#=OLDS SLOUGH,Reach-1         , 1
Up Type= 0
Dn Type= 3
Dn Slope=0.0007
Boundary for River Rch & Prof#=OLDS SLOUGH,Reach-1         , 2
Up Type= 0
Dn Type= 3
Dn Slope=0.0007
Boundary for River Rch & Prof#=OLDS SLOUGH,Reach-1         , 3
Up Type= 0
Dn Type= 3
Dn Slope=0.0007
Boundary for River Rch & Prof#=OLDS SLOUGH,Reach-1         , 4
Up Type= 0
Dn Type= 3
Dn Slope=0.0007
Boundary for River Rch & Prof#=OLDS SLOUGH,Reach-1         , 5
Up Type= 0
Dn Type= 3
Dn Slope=0.0007
Boundary for River Rch & Prof#=OLDS SLOUGH,Reach-1         , 6
Up Type= 0
Dn Type= 3
Dn Slope=0.0007
Boundary for River Rch & Prof#=OLDS SLOUGH,Reach-1         , 7
Up Type= 0
Dn Type= 3
Dn Slope=0.0007
DSS Import GetInterval= 0
DSS Import GetPeak= 0
DSS Import FillOption= 0

--- OLDS SLOUGH.g01 (geometry) ---

Geom Title=Existing Conditions
Program Version=4.10

River Reach=OLDS SLOUGH     ,Reach-1
Reach XY= 30
      2231184.41     13354146.85      2231970.86     13354097.75
      2232533.36     13353856.43        2233141.     13353814.76
      2233575.03     13353637.68      2233653.16     13353438.03
      2234224.34     13353200.18      2234380.59     13353010.94
       2234385.8     13352764.42      2234144.48     13352406.78
      2234337.18     13352167.19      2235594.13      13352172.4
        2235891.     13352075.18      2236219.13     13351764.42
      2237349.34     13352017.89      2238252.11     13352069.97
      2238964.72     13352502.49      2239697.89     13352621.05
      2240099.64     13352173.01      2240358.51     13351635.58
        2240718.     13351505.69      2241062.69     13351079.48
      2241544.42     13350305.49      2241683.95      13349664.1
      2241925.45     13349434.43      2243203.22     13349215.68
      2244267.27     13349535.62      2245182.62      13349466.5
      2245555.31     13349012.54      2245977.72     13349006.85

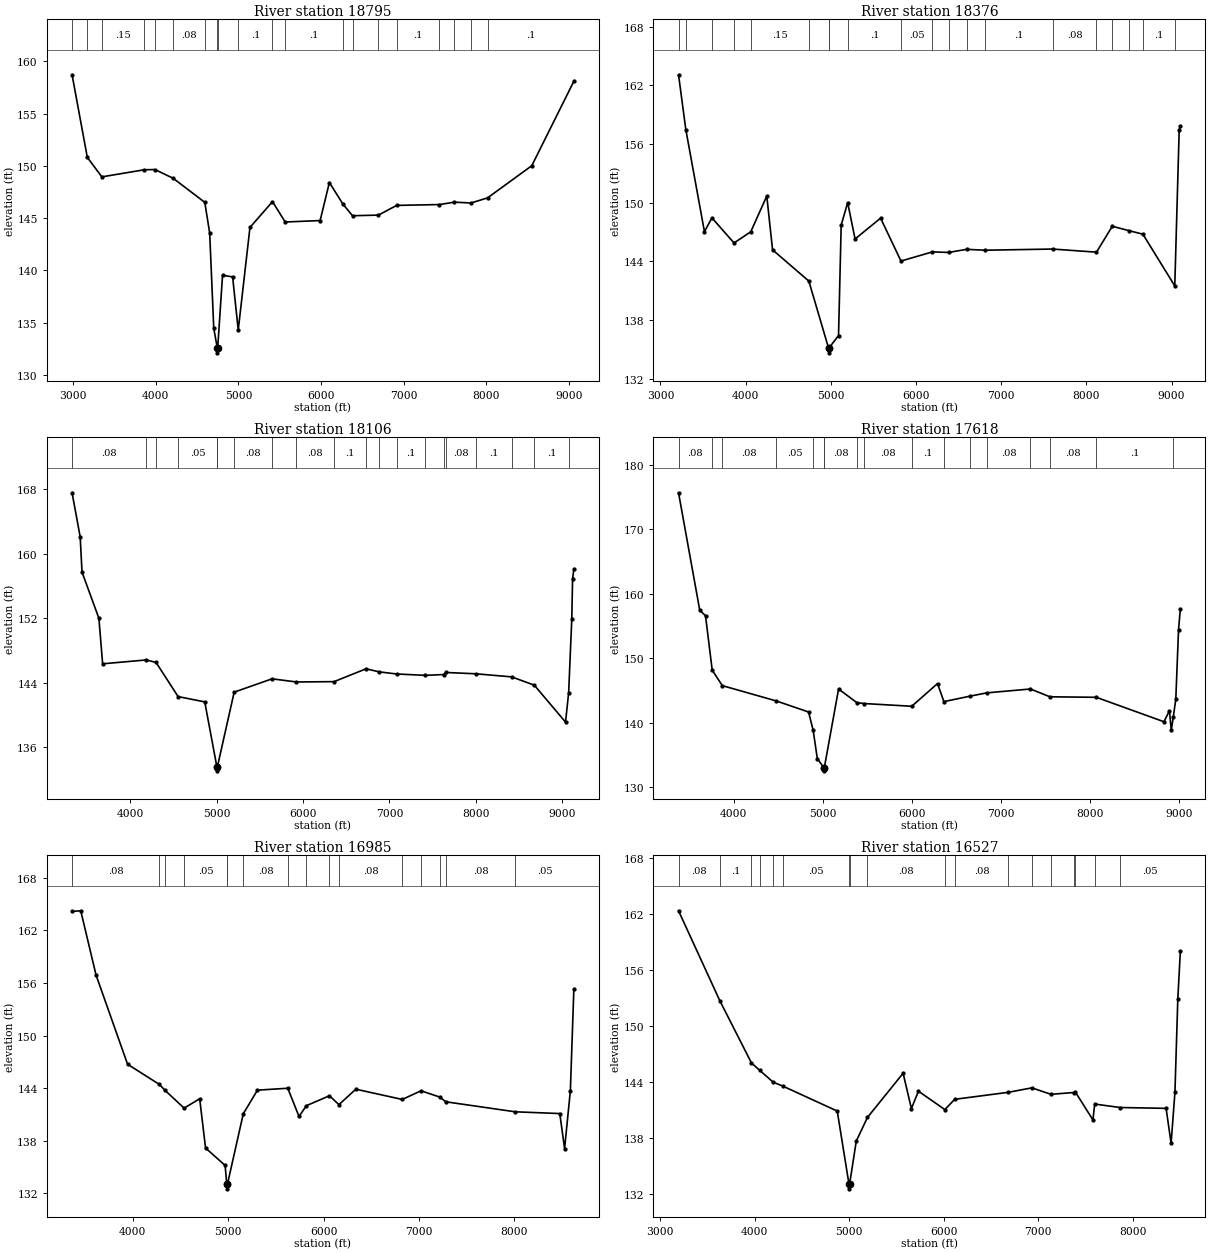
Type RM Length L Ch R = 1 ,18795   ,419,419,419
BEGIN DESCRIPTION:
OLDS SLOUGH 28.0
END DESCRIPTION:
XS GIS Cut Line= 4
      2232399.07     13355795.74      2231503.24     13354561.83
      2231319.86     13353889.44      2230793.16     13350077.41
#Sta/Elev= 30
  2988.1  158.72  3172.4  150.82  3348.1  148.95  3862.3  149.63  3990.5  149.65
  4212.1  148.81  4593.6  146.51  4652.8  143.57  4702.2  134.45  4744.1  132.61
  4746.8  132.11  4750.1  132.61  4808.3  139.53  4930.2  139.38  4998.1  134.29
    5140  144.11  5412.6  146.58  5566.4  144.63  5988.7  144.77  6100.8  148.41
  6264.2  146.35  6380.4  145.23    6694  145.29  6914.5  146.22  7431.3   146.3
  7613.8  146.53    7814  146.45  8014.1  146.94  8549.4  150.02  9058.1   158.1
#Mann= 20 ,-1 , 0
  2988.1      .1       0  3172.4      .1       0  3348.1     .15       0
  3862.3      .1       0  3990.5     .08       0  4212.1     .08       0
  4593.6     .05       0  4744.1     .07       0  4750.1     .05       0
  4998.1      .1       0  5412.6     .08       0  5566.4      .1       0
  6264.2     .15       0  6380.4      .1       0    6694     .15       0
  6914.5      .1       0  7431.3     .15       0  7613.8      .1       0
    7814     .15       0  8014.1      .1       0
Bank Sta=4744.1,4750.1
XS Rating Curve= 0 ,0
Exp/Cntr=0.3,0.1

Type RM Length L Ch R = 1 ,18376   ,270,270,270
BEGIN DESCRIPTION:
OLDS SLOUGH 27.0
END DESCRIPTION:
XS GIS Cut Line= 4
      2232583.55     13355665.57      2231903.95     13354473.53
      2231686.61     13353706.06      2231081.07     13350035.78
#Sta/Elev= 30
  3212.9  163.09  3298.3  157.49  3516.9  147.04    3605  148.45  3864.4  145.88
  4060.9  147.03  4248.7  150.68  4316.5  145.18  4742.4  141.98  4973.5  135.14
  4976.3  134.64  4979.5  135.14  5090.9  136.41    5122   147.7  5198.2  150.01
    5285  146.29  5584.6  148.42  5823.9  144.03  6192.7  144.97  6382.6  144.91
  6593.8  145.23  6807.4  145.14  7602.5  145.26  8118.5  144.94    8304  147.59
    8505  147.13  8663.2  146.78  9037.4  141.49  9089.4  157.48  9102.6  157.84
#Mann= 20 ,-1 , 0
  3212.9     .08       0  3298.3     .08       0    3605     .15       0
  3864.4     .08       0  4060.9     .15       0  4742.4      .1       0
  4973.5     .04       0  4979.5      .1       0  5198.2      .1       0
  5823.9     .05       0  6192.7     .08       0  6382.6      .1       0
  6593.8     .15       0  6807.4      .1       0  7602.5     .08       0
  8118.5     .08       0    8304      .1       0    8505     .05       0
  8663.2      .1       0  9037.4     .05       0
Bank Sta=4973.5,4979.5
XS Rating Curve= 0 ,0
Exp/Cntr=0.3,0.1

Type RM Length L Ch R = 1 ,18106   ,488,488,488
BEGIN DESCRIPTION:
OLDS SLOUGH 26.0
END DESCRIPTION:
XS GIS Cut Line= 4
       2232746.3     13355557.05      2232209.59     13354731.62
      2231958.29     13353678.89       2231227.2     13350012.36
#Sta/Elev= 30
  3328.8  167.53  3422.8  162.06  3443.9   157.7  3639.2  151.98  3682.4  146.34
  4187.7  146.82  4300.5  146.51  4555.5  142.28    4864  141.62  5004.1  133.58
  5006.9  133.08  5010.1  133.58  5204.3  142.83  5642.7  144.48  5925.4  144.09
  6360.2  144.13  6729.4  145.72    6884  145.34  7083.5  145.08  7416.3  144.91
  7628.5  145.01  7651.2  145.27  8005.8   145.1  8415.6  144.72  8676.9  143.69
    9038  139.12  9074.2  142.76  9110.3  151.88  9119.6   156.9  9134.4  158.04
#Mann= 20 ,-1 , 0
  3328.8     .08       0  4187.7      .1       0  4300.5     .08       0
  4555.5     .05       0  5004.1     .04       0  5010.1     .05       0
  5204.3     .08       0  5642.7      .1       0  5925.4     .08       0
  6360.2      .1       0  6729.4     .15       0    6884     .08       0
  7083.5      .1       0  7416.3     .08       0  7628.5      .1       0
  7651.2     .08       0  8005.8      .1       0  8415.6     .05       0
  8676.9      .1       0  9074.2     .05       0
Bank Sta=5004.1,5010.1
XS Rating Curve= 0 ,0
Exp/Cntr=0.3,0.1

Type RM Length L Ch R = 1 ,17618   ,633,633,633
BEGIN DESCRIPTION:
OLDS SLOUGH 25.0
END DESCRIPTION:
XS GIS Cut Line= 3
      2232974.16       13355416.      2232386.18     13353515.88
      2231661.22     13349947.19
#Sta/Elev= 30
  3380.8  175.65    3619  157.43  3683.5  156.59  3758.7  148.15  3872.2  145.75
    4479  143.37  4840.2  141.66  4891.7   138.8  4938.1  134.44  5010.8  133.04
  5013.5  132.54  5016.8  133.04  5176.8  145.23  5381.3  143.11  5457.7  142.98
  5997.6  142.55  6286.7  146.07  6358.5  143.27  6651.9  144.12  6840.2  144.63
  7329.3  145.23  7548.2  144.02  8068.4  143.94  8828.1  140.15  8889.3  141.87
  8909.7   138.8  8932.4  140.89  8960.7  143.65  8991.3  154.41  9011.4  157.59
#Mann= 17 ,-1 , 0
  3380.8     .08       0  3758.7      .1       0  3872.2     .08       0
    4479     .05       0  4891.7     .08       0  5010.8     .07       0
  5016.8     .08       0  5381.3     .05       0  5457.7     .08       0
  5997.6      .1       0  6358.5     .08       0  6651.9      .1       0
  6840.2     .08       0  7329.3      .1       0  7548.2     .08       0
  8068.4      .1       0  8932.4     .05       0
Bank Sta=5010.8,5016.8
XS Rating Curve= 0 ,0
Exp/Cntr=0.3,0.1

Type RM Length L Ch R = 1 ,16985   ,980,980,980
BEGIN DESCRIPTION:
Mapping XS 6d99066c
END DESCRIPTION:
XS GIS Cut Line= 4
      2233299.68     13355437.66      2233235.16     13354303.74
      2233044.98     13353475.13       2232605.4     13350230.58
#Sta/Elev= 30
  3364.3  164.17  3455.3  164.24  3615.5  156.91    3946  146.73  4280.1  144.42
  4339.5  143.74  4538.6  141.72  4702.1  142.79  4763.6  137.17  4968.8  135.18
  4986.3  133.01  4989.1  132.51  4992.3  133.01  5159.2  141.08  5307.4  143.77
  5625.4  143.99  5743.3  140.77  5820.8     142  6061.9  143.13    6162  142.12
  6338.9  143.88  6825.9  142.71  7022.3   143.7  7216.3  142.99  7283.5  142.44
  8010.2   141.3  8476.8   141.1  8527.2  137.11  8587.8  143.71  8624.4  155.31
#Mann= 16 ,-1 , 0
  3364.3     .08       0  4280.1     .05       0  4339.5     .08       0
  4538.6     .05       0  4986.3     .04       0  4992.3     .05       0
  5159.2     .08       0  5625.4      .1       0  5820.8     .08       0
  6061.9      .1       0    6162     .08       0  6825.9      .1       0
  7022.3     .08       0  7216.3      .1       0  7283.5     .08       0
  8010.2     .05       0
Bank Sta=4986.3,4992.3
XS Rating Curve= 0 ,0
Exp/Cntr=0.3,0.1

Type RM Length L Ch R = 1 ,16527   ,326,326,326
BEGIN DESCRIPTION:
Mapping XS 6d9906
END DESCRIPTION:
XS GIS Cut Line= 3
      2233760.69     13355444.98      2233515.54     13353372.74
      2232707.27     13350251.17
#Sta/Elev= 30
  3192.7  162.38    3629  152.74  3964.7  146.04  4051.9  145.25  4194.4  143.98
  4294.1  143.57  4872.5  140.88    4997  133.03  4999.8  132.53    5003  133.03
  5073.8  137.65  5191.8  140.19  5569.7  144.94  5657.3  141.15  5732.1  143.01
  6011.3  141.04  6115.8  142.14  6681.3  142.89  6932.1  143.37  7134.5  142.68
    7379  142.87  7390.7  142.96  7578.7  139.93  7597.8  141.63  7867.3  141.26
  8353.4  141.17  8406.3  137.41  8446.9  142.91  8477.2  152.88  8503.9  158.01
#Mann= 18 ,-1 , 0
  3192.7     .08       0    3629      .1       0  3964.7     .08       0
  4051.9      .1       0  4194.4     .08       0  4294.1     .05       0
    4997     .04       0    5003     .05       0  5191.8     .08       0
  6011.3      .1       0  6115.8     .08       0  6681.3      .1       0
  6932.1     .08       0  7134.5      .1       0    7379     .15       0
  7390.7      .1       0  7597.8     .08       0  7867.3     .05       0
Bank Sta=4997,5003
XS Rating Curve= 0 ,0
Exp/Cntr=0.3,0.1

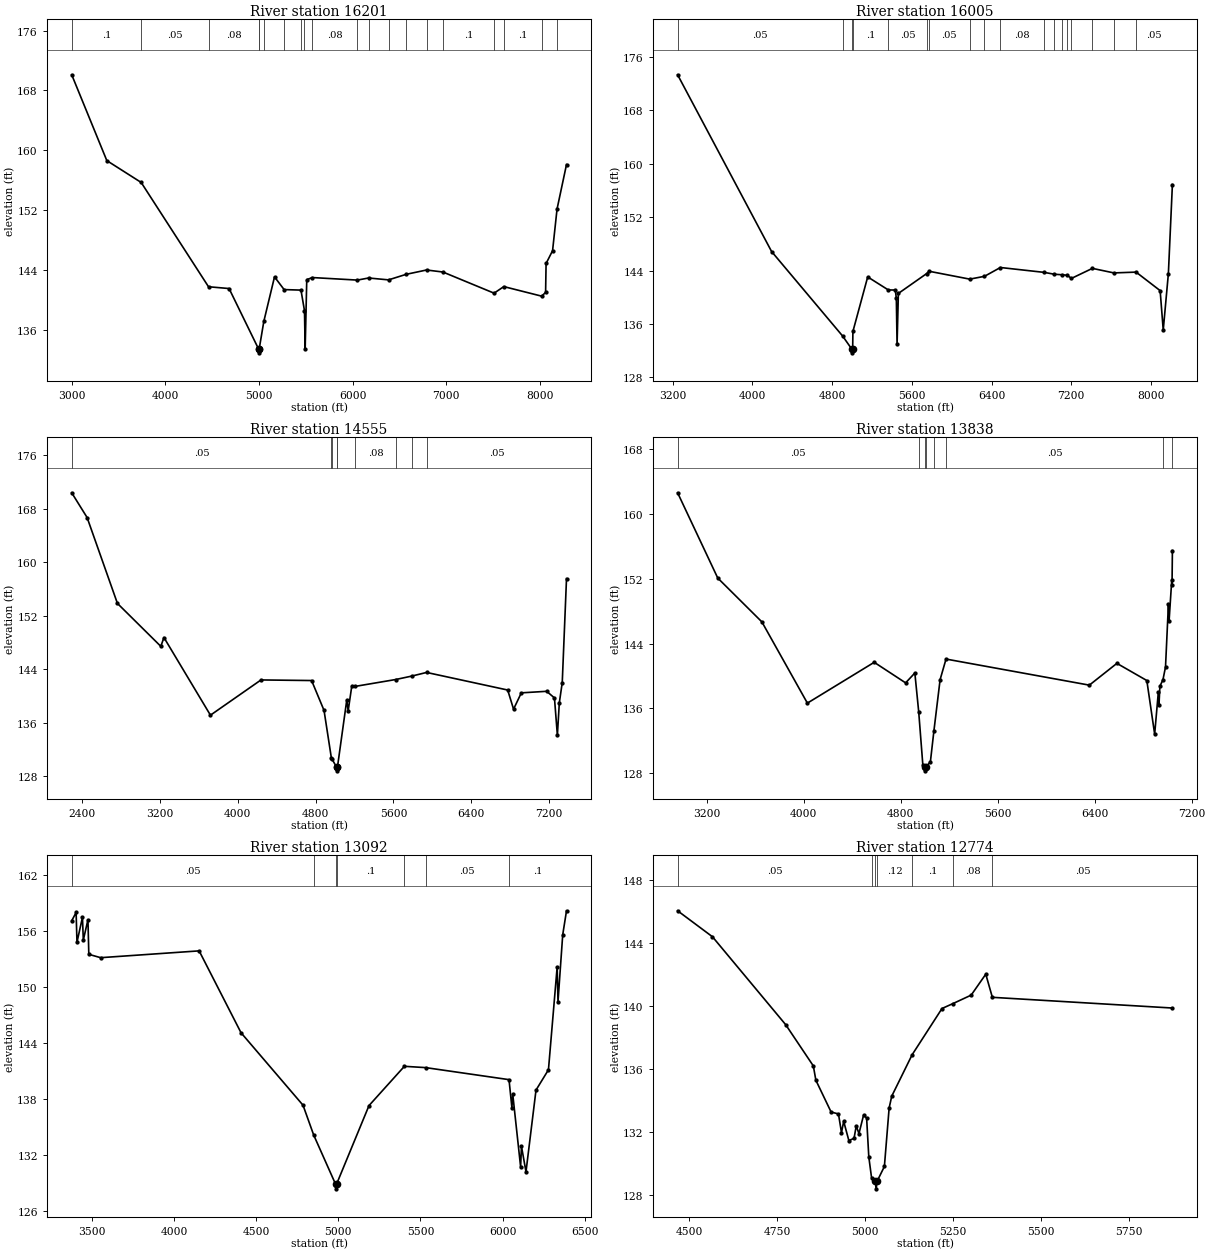
Type RM Length L Ch R = 1 ,16201   ,196,196,196
BEGIN DESCRIPTION:
Mapping XS 6d99066c
END DESCRIPTION:
XS GIS Cut Line= 3
      2234017.54     13355389.49      2233679.07     13353079.25
      2232904.77     13350233.93
#Sta/Elev= 30
  3001.2  170.08  3376.1   158.6  3742.8  155.68  4461.9  141.73  4681.6  141.49
    4997  133.39  4999.8  132.89    5003  133.39  5052.5  137.09  5166.7  143.05
  5269.2  141.35  5449.4  141.28  5486.9  138.52    5494  133.39  5511.1  142.68
  5570.2  142.96  6051.5  142.62  6171.4   142.9  6384.3  142.65  6572.5  143.39
  6790.2  143.97  6964.7   143.7  7511.5  140.87  7615.4  141.75    8020  140.47
  8061.6  140.98  8066.8  144.84    8136  146.55  8183.8  152.12  8284.9  158.08
#Mann= 20 ,-1 , 0
  3001.2      .1       0  3742.8     .05       0  4461.9     .08       0
    4997     .07       0    5003     .08       0  5052.5      .1       0
  5269.2     .08       0  5449.4     .05       0  5486.9      .1       0
  5570.2     .08       0  6051.5     .05       0  6171.4      .1       0
  6384.3     .15       0  6572.5      .1       0  6790.2     .15       0
  6964.7      .1       0  7511.5     .08       0  7615.4      .1       0
    8020     .05       0  8183.8     .08       0
Bank Sta=4997,5003
XS Rating Curve= 0 ,0
Exp/Cntr=0.3,0.1

Type RM Length L Ch R = 1 ,16005   ,1450,1450,1450
BEGIN DESCRIPTION:
OLDS SLOUGH 22.0
END DESCRIPTION:
XS GIS Cut Line= 3
      2234297.93     13355036.15       2233690.3     13352399.48
      2233136.92     13350207.64
#Sta/Elev= 30
  3248.8   173.3  4192.2  146.85  4904.3  134.22  4999.9  132.19  5002.6  131.69
  5005.9  132.19  5008.4  134.89  5156.8  143.05  5363.9   141.1  5433.9  141.09
  5444.2  139.87  5451.6  132.94  5464.7  140.58  5748.6  143.55  5771.9   143.9
  6181.1  142.72    6329  143.14  6488.9  144.46  6928.8  143.73    7031  143.45
  7111.1  143.37  7158.6   143.3  7202.1  142.83  7412.1  144.33  7627.9  143.65
  7850.6  143.77  8092.2     141  8123.2   135.1  8174.8  143.54  8215.2  156.87
#Mann= 18 ,-1 , 0
  3248.8     .05       0  4904.3      .1       0  4999.9     .07       0
  5005.9      .1       0  5363.9     .05       0  5748.6     .08       0
  5771.9     .05       0  6181.1      .1       0    6329     .15       0
  6488.9     .08       0  6928.8      .1       0    7031     .08       0
  7111.1     .05       0  7158.6     .08       0  7202.1      .1       0
  7412.1     .15       0  7627.9      .1       0  7850.6     .05       0
Bank Sta=4999.9,5005.9
XS Rating Curve= 0 ,0
Exp/Cntr=0.3,0.1

Type RM Length L Ch R = 1 ,14555   ,717,717,717
BEGIN DESCRIPTION:
OLDS SLOUGH 21.0
END DESCRIPTION:
XS GIS Cut Line= 4
      2235241.96       13354689.      2234662.72      13352631.1
      2233787.96     13351922.05      2233716.67     13350103.05
#Sta/Elev= 30
  2294.1  170.41  2452.2  166.71  2763.8  153.87  3209.7  147.45  3241.7  148.77
  3719.6  137.16    4239  142.43    4759  142.34  4886.9  137.87  4962.5  130.73
  4965.9  130.66  5018.2  129.34    5021  128.84  5024.2  129.34  5120.6  139.45
  5134.7  137.81  5171.4  141.46  5208.8  141.47  5622.3  142.49  5789.6  143.01
  5940.6  143.55  6774.1  140.92  6834.2  138.06  6914.2   140.5  7174.4  140.73
  7254.5  139.74  7284.5  134.16  7304.5     139  7334.6  142.04  7378.4  157.58
#Mann= 9 ,-1 , 0
  2294.1     .05       0  4962.5     .16       0  4965.9      .1       0
  5018.2     .07       0  5024.2      .1       0  5208.8     .08       0
  5622.3      .1       0  5789.6     .08       0  5940.6     .05       0
Bank Sta=5018.2,5024.2
XS Rating Curve= 0 ,0
Exp/Cntr=0.3,0.1

Type RM Length L Ch R = 1 ,13838   ,746,746,746
BEGIN DESCRIPTION:
OLDS SLOUGH 20.0
END DESCRIPTION:
XS GIS Cut Line= 4
      2235719.36     13354027.04      2234939.31     13352605.49
      2234754.92     13351299.37      2234330.84     13350241.06
#Sta/Elev= 30
    2960  162.63  3291.2   152.1    3655  146.69  4030.3  136.66  4581.5   141.7
  4840.5  139.16  4916.6  140.38  4948.4  135.59  4982.7  128.99  5001.3   128.8
    5004   128.3  5007.3   128.8  5044.7   129.4  5073.6  133.21  5124.9  139.56
  5173.7   142.1  6355.8  138.88    6583  141.57  6829.8  139.45  6894.4  132.83
  6924.7  138.02  6930.1  136.44  6937.5  138.74  6962.8  139.55  6983.9  141.12
  7008.1  148.94  7013.5  146.85  7035.3  151.84  7037.7   151.3  7040.7  155.49
#Mann= 8 ,-1 , 0
    2960     .05       0  4948.4     .12       0  5001.3     .07       0
  5007.3     .12       0  5073.6      .1       0  5173.7     .05       0
  6962.8      .1       0  7035.3     .05       0
Bank Sta=5001.3,5007.3
XS Rating Curve= 0 ,0
Exp/Cntr=0.3,0.1

Type RM Length L Ch R = 1 ,13092   ,318,318,318
BEGIN DESCRIPTION:
OLDS SLOUGH 18.0
END DESCRIPTION:
XS GIS Cut Line= 6
      2236311.23      13353584.1      2236043.36     13352667.71
      2235794.69     13352287.92      2235318.34     13351965.24
       2235215.9     13351847.43      2235032.76     13350994.13
#Sta/Elev= 30
  3376.2  157.08    3403  157.97  3408.2  154.77  3441.6  157.45  3446.8  155.01
  3475.1  157.19  3480.3  153.48  3552.4  153.12  4152.3  153.85  4407.4  145.07
  4784.9   137.3    4850   134.1  4983.2  128.83  4985.9  128.33  4989.2  128.83
  5186.9  137.26  5402.4  141.47    5532  141.33  6039.6  140.04  6057.2  137.03
  6062.3  138.48  6110.3  130.69  6115.4  132.89    6143  130.16    6204  138.92
  6279.8   141.1  6332.9  152.14  6337.9  148.39  6366.7  155.58  6389.8  158.15
#Mann= 7 ,-1 , 0
  3376.2     .05       0    4850      .1       0  4983.2     .07       0
  4989.2      .1       0  5402.4     .08       0    5532     .05       0
  6039.6      .1       0
Bank Sta=4983.2,4989.2
XS Rating Curve= 0 ,0
Exp/Cntr=0.3,0.1

Type RM Length L Ch R = 1 ,12774   ,454,454,454
BEGIN DESCRIPTION:
OLDS SLOUGH 17.0
END DESCRIPTION:
XS GIS Cut Line= 4
      2236214.71      13352487.7      2235733.22     13351806.45
      2235620.54     13351432.55      2235564.74     13351260.08
#Sta/Elev= 30
  4467.4  146.03  4566.4  144.38  4774.6  138.79  4853.1  136.17  4860.3  135.26
  4903.6  133.24  4924.5  133.12  4933.1  131.93  4939.3  132.65    4954  131.43
  4968.8  131.57    4975  132.36  4982.7  131.87  4995.9  133.05  5004.5  132.86
  5010.7  130.39  5018.5  129.07  5028.7  128.86  5031.5  128.36  5034.7  128.86
    5055  129.78  5068.5   133.5  5075.9  134.25  5133.8  136.88  5218.7  139.82
  5249.6  140.13  5301.6  140.67  5343.1     142  5361.8  140.53  5873.4  139.85
#Mann= 7 ,-1 , 0
  4467.4     .05       0  5018.5     .12       0  5028.7     .03       0
  5034.7     .12       0  5133.8      .1       0  5249.6     .08       0
  5361.8     .05       0
Bank Sta=5028.7,5034.7
XS Rating Curve= 0 ,0
Exp/Cntr=0.3,0.1

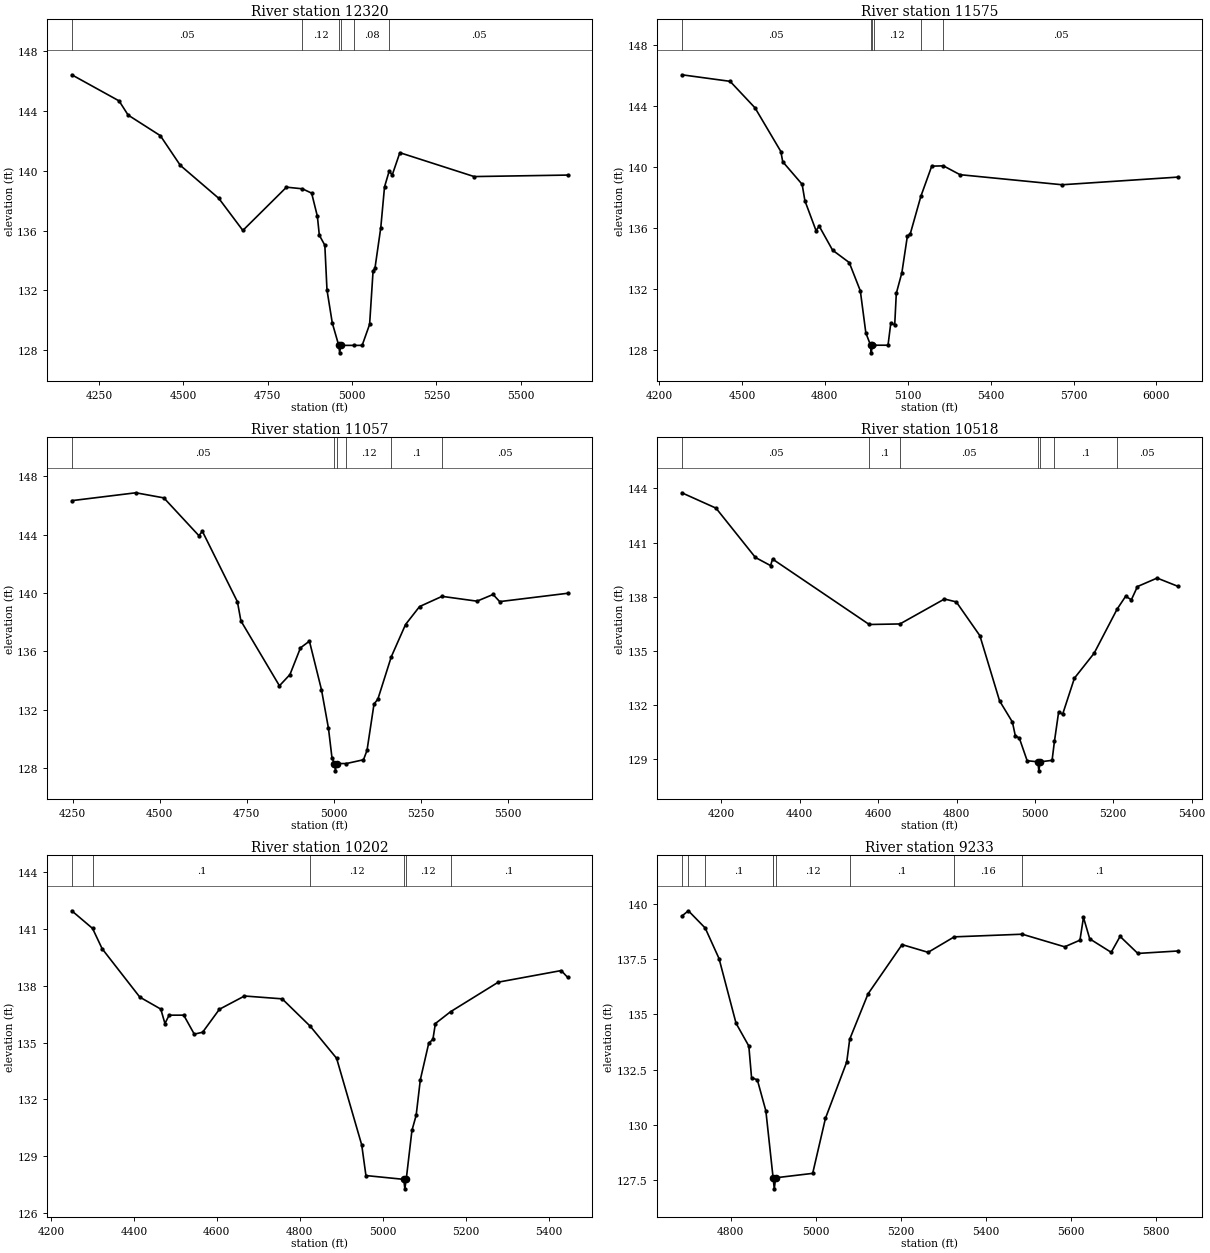
Type RM Length L Ch R = 1 ,12320   ,745,745,745
BEGIN DESCRIPTION:
OLDS SLOUGH 16.0
END DESCRIPTION:
XS GIS Cut Line= 3
      2236434.94      13352564.5      2236312.01      13351934.5
      2235958.59     13351186.69
#Sta/Elev= 30
  4169.4  146.44  4309.6  144.69  4336.4  143.74  4431.9  142.36  4491.1  140.37
  4605.1  138.16  4676.4  136.01  4805.7  138.91  4852.8   138.8  4880.2  138.51
  4897.2  136.96    4903  135.69  4919.3  135.02  4925.7  132.02  4941.4  129.81
  4960.5  128.31  4963.3  127.81  4966.5  128.31  5006.6  128.31  5029.9  128.31
    5052  129.72  5062.3  133.31  5067.8  133.47  5085.1   136.2  5096.2  138.93
  5110.2     140  5118.9  139.72  5141.6  141.22  5361.7  139.62  5638.4  139.72
#Mann= 6 ,-1 , 0
  4169.4     .05       0  4852.8     .12       0  4960.5     .07       0
  4966.5     .12       0  5006.6     .08       0  5110.2     .05       0
Bank Sta=4960.5,4966.5
XS Rating Curve= 0 ,0
Exp/Cntr=0.3,0.1

Type RM Length L Ch R = 1 ,11575   ,518,518,518
BEGIN DESCRIPTION:
OLDS SLOUGH 15.0
END DESCRIPTION:
XS GIS Cut Line= 4
      2237008.61     13352631.14      2236931.78     13351575.96
      2236687.72     13351046.85      2236593.71     13350925.45
#Sta/Elev= 30
  4282.4  146.04  4457.1  145.61  4547.4  143.87  4640.8  141.01  4647.6  140.34
  4717.8  138.86  4727.9  137.78    4768  135.83  4779.8  136.11  4828.1  134.54
  4888.3  133.73  4928.4  131.88  4948.4  129.12  4965.5  128.31  4968.2  127.81
  4971.5  128.31  4977.1  128.31  5028.7  128.31  5038.7  129.76  5052.9  129.64
  5058.7  131.71  5078.8  133.06  5098.8  135.47  5108.9  135.59  5147.7  138.08
  5186.9  140.05  5229.1  140.07  5289.3  139.49  5658.8  138.83  6076.6  139.33
#Mann= 6 ,-1 , 0
  4282.4     .05       0  4965.5     .07       0  4971.5     .05       0
  4977.1     .12       0  5147.7      .1       0  5229.1     .05       0
Bank Sta=4965.5,4971.5
XS Rating Curve= 0 ,0
Exp/Cntr=0.3,0.1

Type RM Length L Ch R = 1 ,11057   ,539,539,539
BEGIN DESCRIPTION:
Mapping XS 954eb45f
END DESCRIPTION:
XS GIS Cut Line= 3
      2237381.48     13352779.73      2237505.69     13351595.63
      2237489.13     13351363.82
#Sta/Elev= 30
  4247.6  146.33  4431.5  146.87  4511.9  146.52  4612.5  143.93  4622.5  144.23
  4723.1   139.4  4733.1  138.09  4843.7  133.64  4873.9  134.41  4904.1  136.24
  4929.8   136.7  4964.4  133.37  4984.5  130.72  4994.6  128.69  5001.6  128.31
  5004.4  127.81  5007.6  128.31  5035.8  128.31    5085  128.57  5095.1  129.21
  5115.2  132.39  5126.2  132.72  5164.8  135.63  5205.7  137.84  5245.9  139.07
  5310.5  139.77  5410.8  139.44    5457   139.9  5475.9  139.41  5670.6  139.98
#Mann= 6 ,-1 , 0
  4247.6     .05       0  5001.6     .03       0  5007.6     .05       0
  5035.8     .12       0  5164.8      .1       0  5310.5     .05       0
Bank Sta=5001.6,5007.6
XS Rating Curve= 0 ,0
Exp/Cntr=0.3,0.1

Type RM Length L Ch R = 1 ,10518   ,316,316,316
BEGIN DESCRIPTION:
Mapping XS bf8f08ea
END DESCRIPTION:
XS GIS Cut Line= 2
      2238085.31     13352953.62      2237961.11     13351695.04
#Sta/Elev= 30
  4099.2  143.76  4186.4  142.91  4286.9  140.18  4325.6  139.73  4330.7  140.09
  4577.3  136.47  4655.7   136.5  4769.2  137.88  4799.4  137.72  4859.6  135.85
  4909.9  132.24  4942.6  131.07  4950.1   130.3  4960.1  130.19  4980.2  128.93
  5007.4  128.87  5010.1  128.37  5013.4  128.87  5043.8  128.95  5049.8     130
  5060.6  131.64  5070.7   131.5  5100.8   133.5  5151.1  134.88  5209.7  137.32
  5231.4  138.03  5246.1  137.84  5261.6  138.57  5311.8  139.04  5363.9  138.59
#Mann= 7 ,-1 , 0
  4099.2     .05       0  4577.3      .1       0  4655.7     .05       0
  5007.4     .03       0  5013.4     .05       0  5049.8      .1       0
  5209.7     .05       0
Bank Sta=5007.4,5013.4
XS Rating Curve= 0 ,0
Exp/Cntr=0.3,0.1

Type RM Length L Ch R = 1 ,10202   ,969,969,969
BEGIN DESCRIPTION:
OLDS SLOUGH 14.0
END DESCRIPTION:
XS GIS Cut Line= 2
      2238408.25     13352829.44      2238250.92     13351645.35
#Sta/Elev= 30
  4250.4  141.94  4300.5  141.01  4323.6  139.94  4414.4  137.39  4464.9  136.76
  4474.9     136    4485  136.44  4520.2  136.44  4545.6  135.44  4565.7  135.54
  4606.1  136.75  4666.6  137.45  4757.4   137.3  4825.3  135.85  4888.5  134.17
  4949.1   129.6  4959.2  127.99  5050.3  127.79    5053  127.29  5056.3  127.79
  5070.1  130.37  5080.2  131.16  5090.3  133.04  5110.5  134.96  5120.6  135.17
  5126.6     136    5163  136.62  5278.2  138.18  5429.7  138.79  5444.9  138.44
#Mann= 6 ,-1 , 0
  4250.4     .05       0  4300.5      .1       0  4825.3     .12       0
  5050.3     .07       0  5056.3     .12       0    5163      .1       0
Bank Sta=5050.3,5056.3
XS Rating Curve= 0 ,0
Exp/Cntr=0.3,0.1

Type RM Length L Ch R = 1 ,9233    ,767,767,767
BEGIN DESCRIPTION:
OLDS SLOUGH 13.0
END DESCRIPTION:
XS GIS Cut Line= 3
      2239145.19     13352854.25      2239136.91     13352299.46
      2238641.37     13351944.33
#Sta/Elev= 30
  4685.3  139.45  4700.7  139.69  4740.2  138.91  4772.7  137.53  4812.7   134.6
  4842.7  133.57  4849.1  132.14  4862.7  132.04  4882.7  130.64  4899.6  127.63
  4899.7  127.61  4902.5  127.11  4905.7  127.61  4992.7  127.81  5022.7   130.3
  5072.7  132.85  5079.7  133.88  5122.7  135.93  5202.7  138.16  5263.8  137.81
  5325.2  138.51    5485  138.63  5584.6  138.06  5620.5  138.36  5628.8  139.39
  5643.5  138.42  5693.9  137.81  5714.8  138.53  5756.5  137.76  5849.8  137.87
#Mann= 9 ,-1 , 0
  4685.3      .1       0  4700.7     .16       0  4740.2      .1       0
  4899.6     .12       0  4899.7     .07       0  4905.7     .12       0
  5079.7      .1       0  5325.2     .16       0    5485      .1       0
Bank Sta=4899.7,4905.7
XS Rating Curve= 0 ,0
Exp/Cntr=0.3,0.1

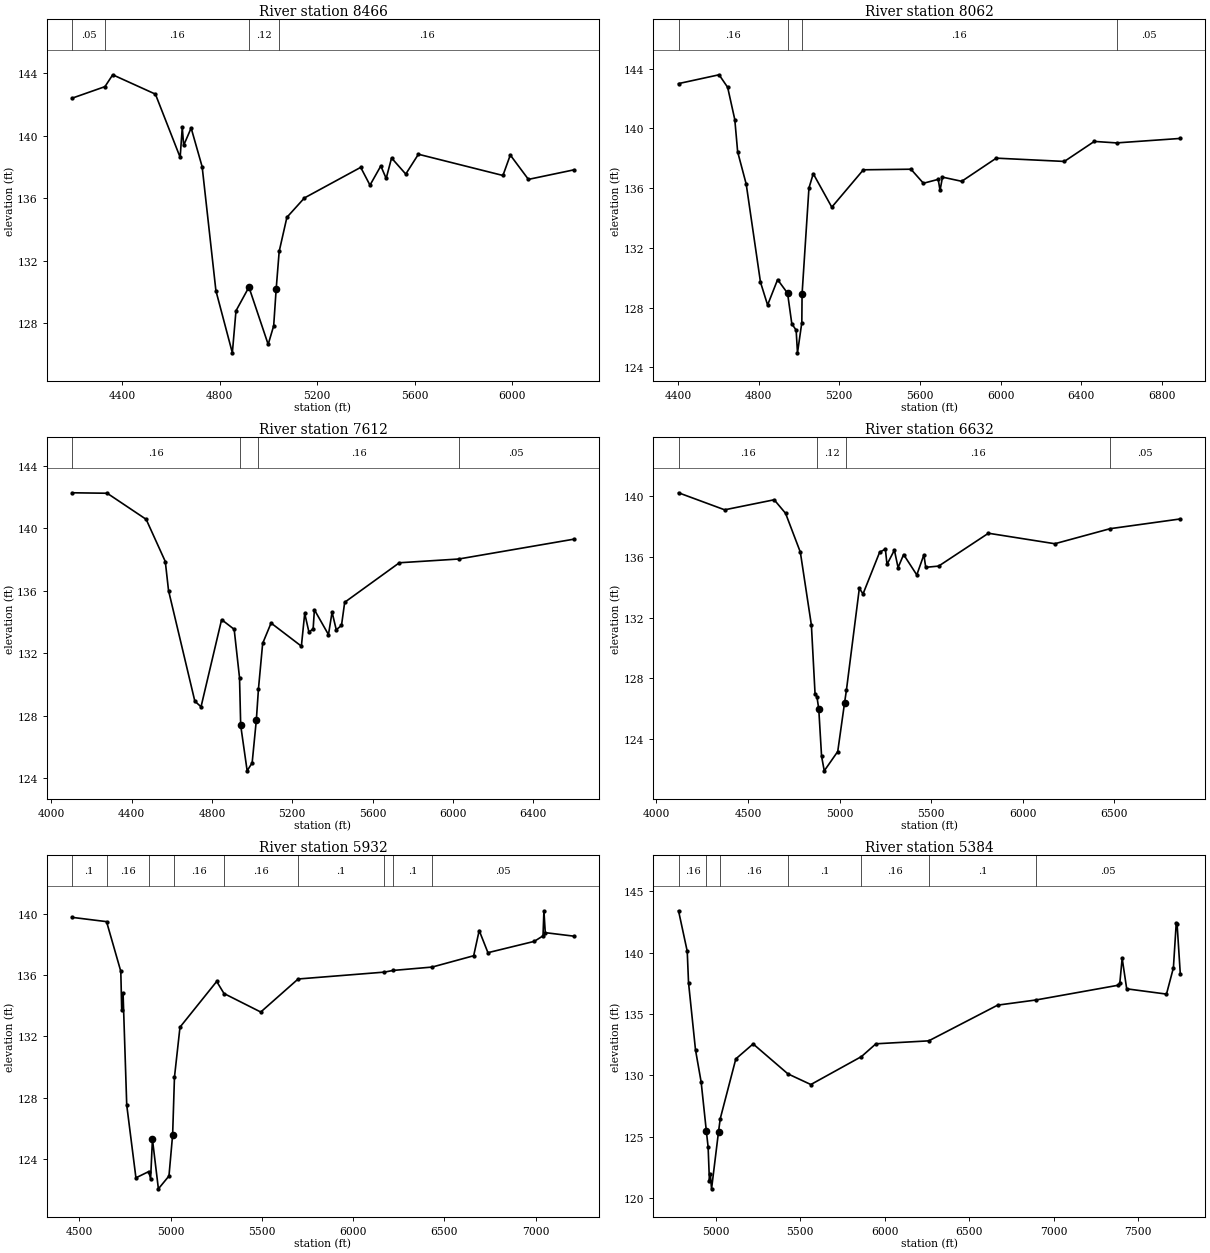
Type RM Length L Ch R = 1 ,8466    ,404,404,404
BEGIN DESCRIPTION:
OLDS SLOUGH 12.0
END DESCRIPTION:
XS GIS Cut Line= 3
      2240329.28      13353003.3      2240122.26     13352655.51
      2238656.69     13351885.47
#Sta/Elev= 30
  4193.6  142.41  4328.6  143.15  4360.5  143.91  4535.8  142.67  4637.4  138.62
  4646.1  140.54  4651.8  139.39  4682.5   140.5  4727.7  138.02  4784.2  130.08
  4851.7   126.1  4866.6  128.79  4919.8  130.31  4998.8  126.64  5021.4  127.83
  5031.6  130.18    5044   132.6  5075.7  134.78  5147.5  136.02  5378.7  137.98
  5416.8  136.84  5461.3  138.07  5483.3  137.27  5505.4  138.58  5563.7  137.55
  5615.6  138.82  5962.7  137.46  5992.9  138.77  6067.3  137.21  6253.9  137.82
#Mann= 4 ,-1 , 0
  4193.6     .05       0  4328.6     .16       0  4919.8     .12       0
    5044     .16       0
Bank Sta=4919.8,5031.6
XS Rating Curve= 0 ,0
Exp/Cntr=0.3,0.1

Type RM Length L Ch R = 1 ,8062    ,450,450,450
BEGIN DESCRIPTION:
OLDS SLOUGH 11.0
END DESCRIPTION:
XS GIS Cut Line= 3
        2240470.     13352638.92      2239832.45     13352017.93
      2238325.41     13351487.98
#Sta/Elev= 30
  4403.5     143  4604.5  143.59    4647  142.75  4682.4  140.59  4696.6  138.43
    4739  136.27  4809.7  129.71    4845  128.18  4894.6  129.88    4944  128.97
  4965.1  126.92  4986.5   126.5  4993.2  124.98  5014.7  127.01 5015.91  128.92
    5050  136.01  5071.3  136.97  5163.2  134.73  5319.7  137.23  5555.6  137.27
  5617.5  136.33  5690.7  136.59  5699.9  135.85  5711.9  136.74  5807.3  136.46
  5978.6  138.01  6316.1  137.79  6464.5  139.13  6574.8  139.03    6891  139.33
#Mann= 4 ,-1 , 0
  4403.5     .16       0    4944     .12       0 5015.91     .16       0
  6574.8     .05       0
Bank Sta=4944,5015.91
XS Rating Curve= 0 ,0
Exp/Cntr=0.3,0.1

Type RM Length L Ch R = 1 ,7612    ,980,980,980
BEGIN DESCRIPTION:
OLDS SLOUGH 10.0
END DESCRIPTION:
XS GIS Cut Line= 4
      2240594.24       13352581.      2240561.12      13352241.5
      2240362.39     13351877.16      2238698.05      13351355.5
#Sta/Elev= 30
  4102.6  142.27  4277.6  142.24  4471.8  140.57  4567.1  137.87  4583.3  136.01
  4714.3  128.93  4745.2  128.57  4847.7  134.15  4910.3  133.53    4937  130.43
  4942.8  127.38    4975  124.47  4999.9  124.98  5020.8  127.73  5031.3  129.71
  5052.3  132.63  5094.2  133.93  5245.2  132.45  5261.8  134.55  5282.9  133.35
  5303.8  133.56  5310.1  134.78  5380.2  133.19  5398.1  134.63    5419   133.5
  5445.1  133.78    5461  135.26  5733.4  137.79    6029  138.03  6602.9   139.3
#Mann= 4 ,-1 , 0
  4102.6     .16       0    4937     .12       0  5031.3     .16       0
    6029     .05       0
Bank Sta=4942.8,5020.8
XS Rating Curve= 0 ,0
Exp/Cntr=0.3,0.1

Type RM Length L Ch R = 1 ,6632    ,700,700,700
BEGIN DESCRIPTION:
OLDS SLOUGH 9.0
END DESCRIPTION:
XS GIS Cut Line= 3
      2241695.51     13351612.18       2241281.5     13351280.98
      2239087.25     13351024.29
#Sta/Elev= 30
  4120.9   140.2  4372.7  139.08  4643.1  139.74  4705.2  138.85  4785.8   136.3
  4846.2   131.5  4866.3  126.96  4876.4   126.8  4886.5  125.98  4901.7  122.89
  4916.4  121.92    4990  123.19  5027.4   126.4  5037.5  127.23    5108  133.92
  5128.1  133.55  5218.7  136.29    5250   136.5    5259  135.49  5299.3  136.43
  5319.4  135.28  5349.6  136.14  5421.6   134.8  5460.3  136.12  5470.4   135.3
  5540.9  135.38  5812.7  137.54  6175.2  136.85  6477.2  137.84  6860.3  138.48
#Mann= 4 ,-1 , 0
  4120.9     .16       0  4876.4     .12       0  5037.5     .16       0
  6477.2     .05       0
Bank Sta=4886.5,5027.4
XS Rating Curve= 0 ,0
Exp/Cntr=0.3,0.1

Type RM Length L Ch R = 1 ,5932    ,548,548,548
BEGIN DESCRIPTION:
OLDS SLOUGH 8.0
END DESCRIPTION:
XS GIS Cut Line= 2
      2241805.55     13350688.67      2239071.99     13350415.31
#Sta/Elev= 30
  4461.1  139.78  4649.9   139.5  4727.9  136.25  4732.9   133.7  4740.3  134.82
  4760.4   127.5  4810.7  122.75    4881  123.16  4891.1  122.68  4901.1  125.27
  4933.7  122.03  4991.6  122.87  5011.7  125.57  5021.7  129.33  5051.9   132.6
  5252.9  135.59  5292.9   134.8  5494.1  133.59  5698.8  135.75  6171.2   136.2
  6219.1  136.31  6432.5  136.53  6659.8  137.27    6690  138.92  6737.9  137.47
  6991.5  138.21  7039.4  138.57  7044.4  140.21  7051.8  138.78  7208.3  138.55
#Mann= 9 ,-1 , 0
  4461.1      .1       0  4649.9     .16       0    4881      .1       0
  5021.7     .16       0  5292.9     .16       0  5698.8      .1       0
  6171.2     .16       0  6219.1      .1       0  6432.5     .05       0
Bank Sta=4901.1,5011.7
XS Rating Curve= 0 ,0
Exp/Cntr=0.3,0.1

Type RM Length L Ch R = 1 ,5384    ,494,494,494
BEGIN DESCRIPTION:
OLDS SLOUGH 7.0
END DESCRIPTION:
XS GIS Cut Line= 3
      2241787.69     13350146.86      2241587.72     13350196.85
      2238887.71     13349596.85
#Sta/Elev= 30
  4778.5   143.4    4830   140.1  4837.7  137.54    4879  132.06  4912.5  129.44
  4943.4  125.42  4953.7  124.15  4961.4  121.41  4966.6  121.94  4974.1  120.74
  5015.4   125.4  5025.6  126.46  5117.8  131.33  5220.2  132.55  5426.3  130.11
  5562.1  129.24  5862.1  131.52  5947.6  132.56  6260.4   132.8  6668.5  135.71
  6895.1  136.13  7381.7  137.33  7391.9  137.48    7406  139.53  7432.9  137.04
  7668.5  136.61  7709.5  138.75  7726.2  142.39  7731.3  142.33  7750.5  138.21
#Mann= 7 ,-1 , 0
  4778.5     .16       0  4943.4      .1       0  5025.6     .16       0
  5426.3      .1       0  5862.1     .16       0  6260.4      .1       0
  6895.1     .05       0
Bank Sta=4943.4,5015.4
XS Rating Curve= 0 ,0
Exp/Cntr=0.3,0.1

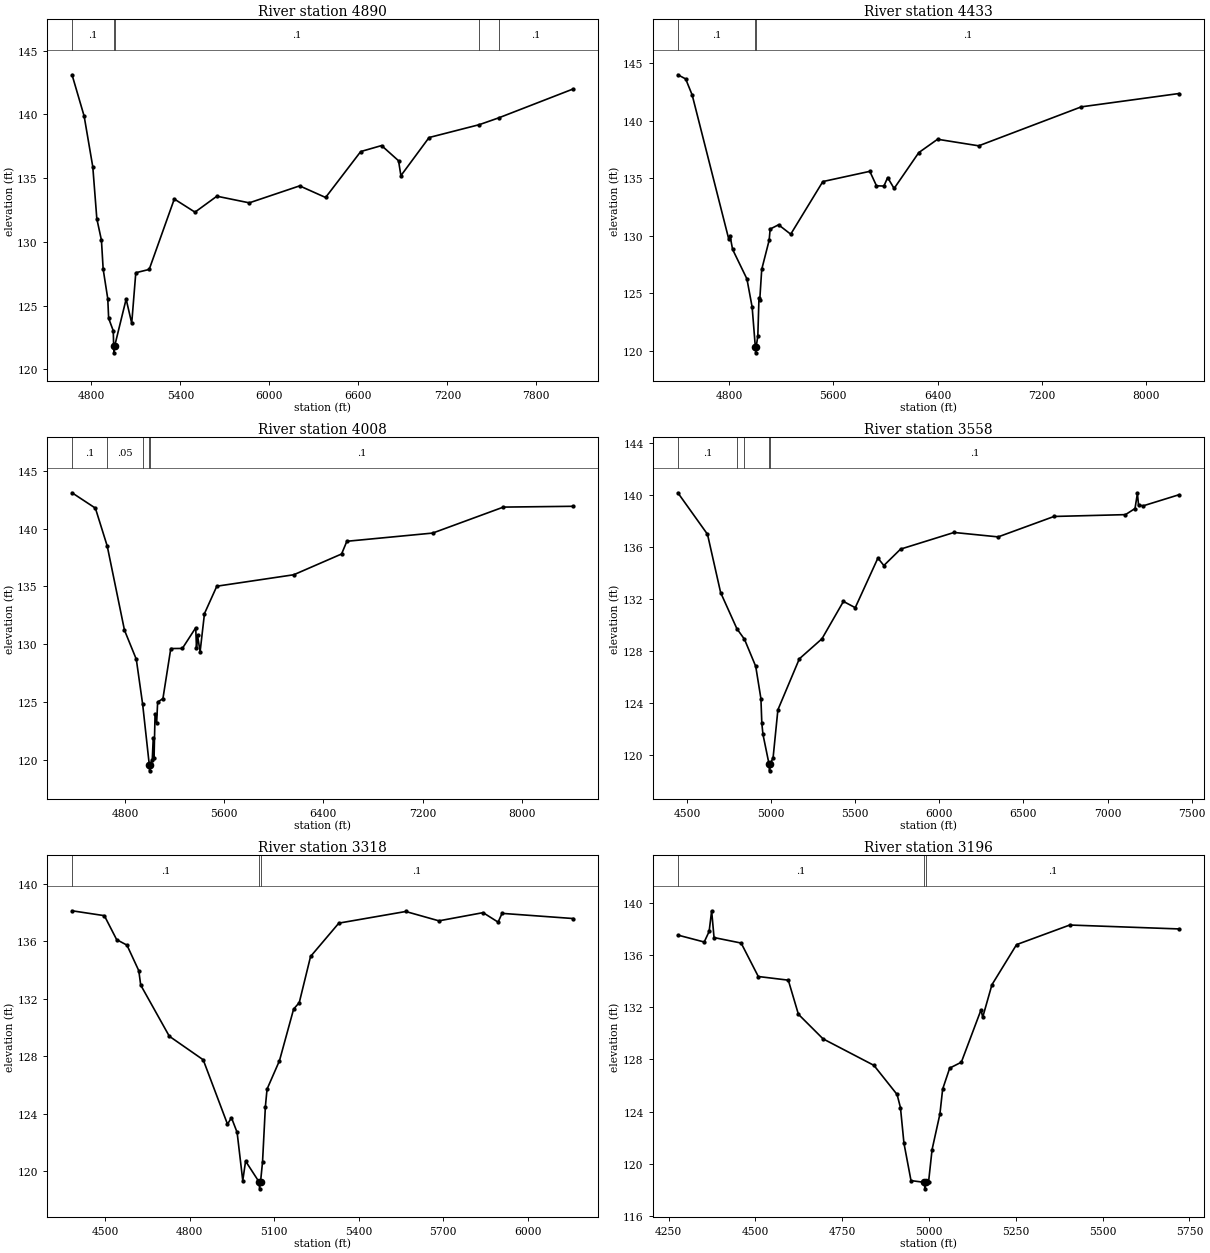
Type RM Length L Ch R = 1 ,4890    ,457,457,457
BEGIN DESCRIPTION:
OLDS SLOUGH 6.0
END DESCRIPTION:
XS GIS Cut Line= 3
      2241837.73     13349996.87      2241687.72     13349746.85
      2240187.74      13347046.9
#Sta/Elev= 30
  4668.8   143.1  4750.4  139.86  4808.8  135.88    4836  131.81  4867.1  130.13
  4878.7  127.86  4909.8  125.54  4915.7  124.01  4946.8  123.03  4949.6   121.8
  4952.3   121.3  4955.6   121.8  5033.6  125.51  5071.3  123.62  5098.8  127.58
  5189.2  127.84  5358.5  133.36    5498  132.33  5645.6  133.58  5864.1  133.06
  6203.8  134.39  6378.9  133.48  6615.7  137.08  6756.4  137.55  6870.8  136.36
  6886.8  135.19  7076.7  138.18  7415.8  139.19  7545.9  139.72    8049  141.99
#Mann= 5 ,-1 , 0
  4668.8      .1       0  4949.6     .07       0  4955.6      .1       0
  7415.8     .16       0  7545.9      .1       0
Bank Sta=4949.6,4955.6
XS Rating Curve= 0 ,0
Exp/Cntr=0.3,0.1

Type RM Length L Ch R = 1 ,4433    ,425,425,425
BEGIN DESCRIPTION:
OLDS SLOUGH 5.0
END DESCRIPTION:
XS GIS Cut Line= 3
      2241987.72     13349996.84      2241987.72     13349396.85
      2240187.71     13346696.84
#Sta/Elev= 30
  4407.5     144  4467.5  143.64  4517.5  142.24  4797.5  129.73  4807.5  130.01
  4827.5  128.81  4937.5  126.24  4977.5  123.79    5002  120.31  5004.7  119.81
    5008  120.31    5021  121.26    5030  124.61    5036  124.44    5051  127.07
  5108.1  129.61  5115.6  130.58  5180.2  130.95  5273.4  130.13  5519.8  134.71
  5880.3   135.6  5931.4  134.34  5988.5  134.32    6017  135.06  6066.6  134.11
  6255.9  137.23  6400.1  138.39  6715.6  137.82  7502.8  141.21  8252.5  142.37
#Mann= 3 ,-1 , 0
  4407.5      .1       0    5002     .07       0    5008      .1       0
Bank Sta=5002,5008
XS Rating Curve= 0 ,0
Exp/Cntr=0.3,0.1

Type RM Length L Ch R = 1 ,4008    ,450,450,450
BEGIN DESCRIPTION:
OLDS SLOUGH 4.0
END DESCRIPTION:
XS GIS Cut Line= 3
      2242237.73     13349946.83      2242387.72     13349346.85
       2240287.7     13346646.83
#Sta/Elev= 30
  4374.2   143.1  4562.3  141.77  4657.9  138.48  4796.8   131.2  4892.1  128.68
  4943.2  124.79  4996.9  119.52  4999.6  119.02  5002.9  119.52  5020.7  119.96
  5028.8   121.9  5035.2  120.15  5043.3  123.94    5056  123.17  5064.1  124.97
  5106.7  125.28    5170  129.61  5263.2  129.62  5370.9  131.41  5377.2  129.67
  5385.4  130.76  5406.2  129.33  5441.5  132.64    5541  135.01  6160.9     136
  6546.4   137.8  6588.9   138.9  7280.2  139.61  7850.3  141.86  8413.2  141.93
#Mann= 5 ,-1 , 0
  4374.2      .1       0  4657.9     .05       0  4943.2      .1       0
  4996.9     .07       0  5002.9      .1       0
Bank Sta=4996.9,5002.9
XS Rating Curve= 0 ,0
Exp/Cntr=0.3,0.1

Type RM Length L Ch R = 1 ,3558    ,240,240,240
BEGIN DESCRIPTION:
OLDS SLOUGH 3.0
END DESCRIPTION:
XS GIS Cut Line= 3
      2242637.74     13349796.81      2242837.72     13349296.85
      2241187.72     13347496.85
#Sta/Elev= 30
  4444.8  140.19  4621.1     137  4699.2  132.52    4796  129.74  4841.1  128.93
  4907.9  126.85  4938.8  124.37  4944.2  122.47    4951  121.62  4987.4  119.32
  4990.1  118.82  4993.4  119.32  5011.3  119.84  5039.7  123.51  5167.3  127.43
  5301.8  128.97  5429.4  131.84  5499.7  131.36  5634.4  135.17  5669.9   134.6
  5769.2  135.86  6087.3  137.14  6349.4   136.8  6681.8  138.37  7106.6  138.51
  7163.3  138.98  7177.5  140.14  7184.3  139.24  7212.7  139.19  7425.1  140.04
#Mann= 5 ,-1 , 0
  4444.8      .1       0    4796     .05       0  4841.1      .1       0
  4987.4     .07       0  4993.4      .1       0
Bank Sta=4987.4,4993.4
XS Rating Curve= 0 ,0
Exp/Cntr=0.3,0.1

Type RM Length L Ch R = 1 ,3318    ,122,122,122
BEGIN DESCRIPTION:
OLDS SLOUGH 2.0
END DESCRIPTION:
XS GIS Cut Line= 4
      2242887.75     13349796.82      2243031.23     13349590.75
      2243083.32     13348861.58      2242729.16     13348148.07
#Sta/Elev= 30
  4382.9  138.13  4497.6  137.79  4541.3  136.12  4577.8  135.74  4619.8  133.96
  4626.6  132.96  4728.1   129.4  4848.4  127.76  4934.6  123.28  4948.7  123.73
  4968.7  122.71  4988.8  119.35  4998.8  120.71    5046  119.28  5048.7  118.78
    5052  119.28    5059  120.66    5069  124.49    5075  125.72  5119.1   127.7
  5169.3  131.29  5189.3  131.74  5229.4  134.95  5329.7  137.27  5567.2  138.08
  5684.9  137.43  5841.7     138    5895  137.34    5909  137.95  6161.6  137.59
#Mann= 3 ,-1 , 0
  4382.9      .1       0    5046     .07       0    5052      .1       0
Bank Sta=5046,5052
XS Rating Curve= 0 ,0
Exp/Cntr=0.3,0.1

Type RM Length L Ch R = 1 ,3196    ,430,430,430
BEGIN DESCRIPTION:
Mapping XS 1490532c
END DESCRIPTION:
XS GIS Cut Line= 5
      2242903.51     13349850.13      2243110.19     13349634.95
      2243243.26     13348813.88      2243183.81     13348610.03
      2243130.03     13348525.11
#Sta/Elev= 30
  4276.9  137.51  4352.8  136.98    4367  137.79  4374.2  139.37  4381.1  137.32
  4459.1   136.9  4508.5  134.34  4594.9  134.06    4624  131.45  4694.9  129.57
  4841.4  127.54  4908.1  125.31  4917.8  124.31  4927.9  121.58  4948.2  118.72
  4985.7  118.59  4988.4  118.09  4991.7  118.59  4998.8  118.63  5008.9   121.1
  5031.4  123.81  5039.3  125.72  5059.6  127.33  5093.1  127.78  5149.7  131.78
  5154.7  131.23  5181.2  133.71  5252.1  136.78  5405.3  138.28  5719.9  137.98
#Mann= 3 ,-1 , 0
  4276.9      .1       0  4985.7     .07       0  4991.7      .1       0
Bank Sta=4985.7,4991.7
XS Rating Curve= 0 ,0
Exp/Cntr=0.3,0.1