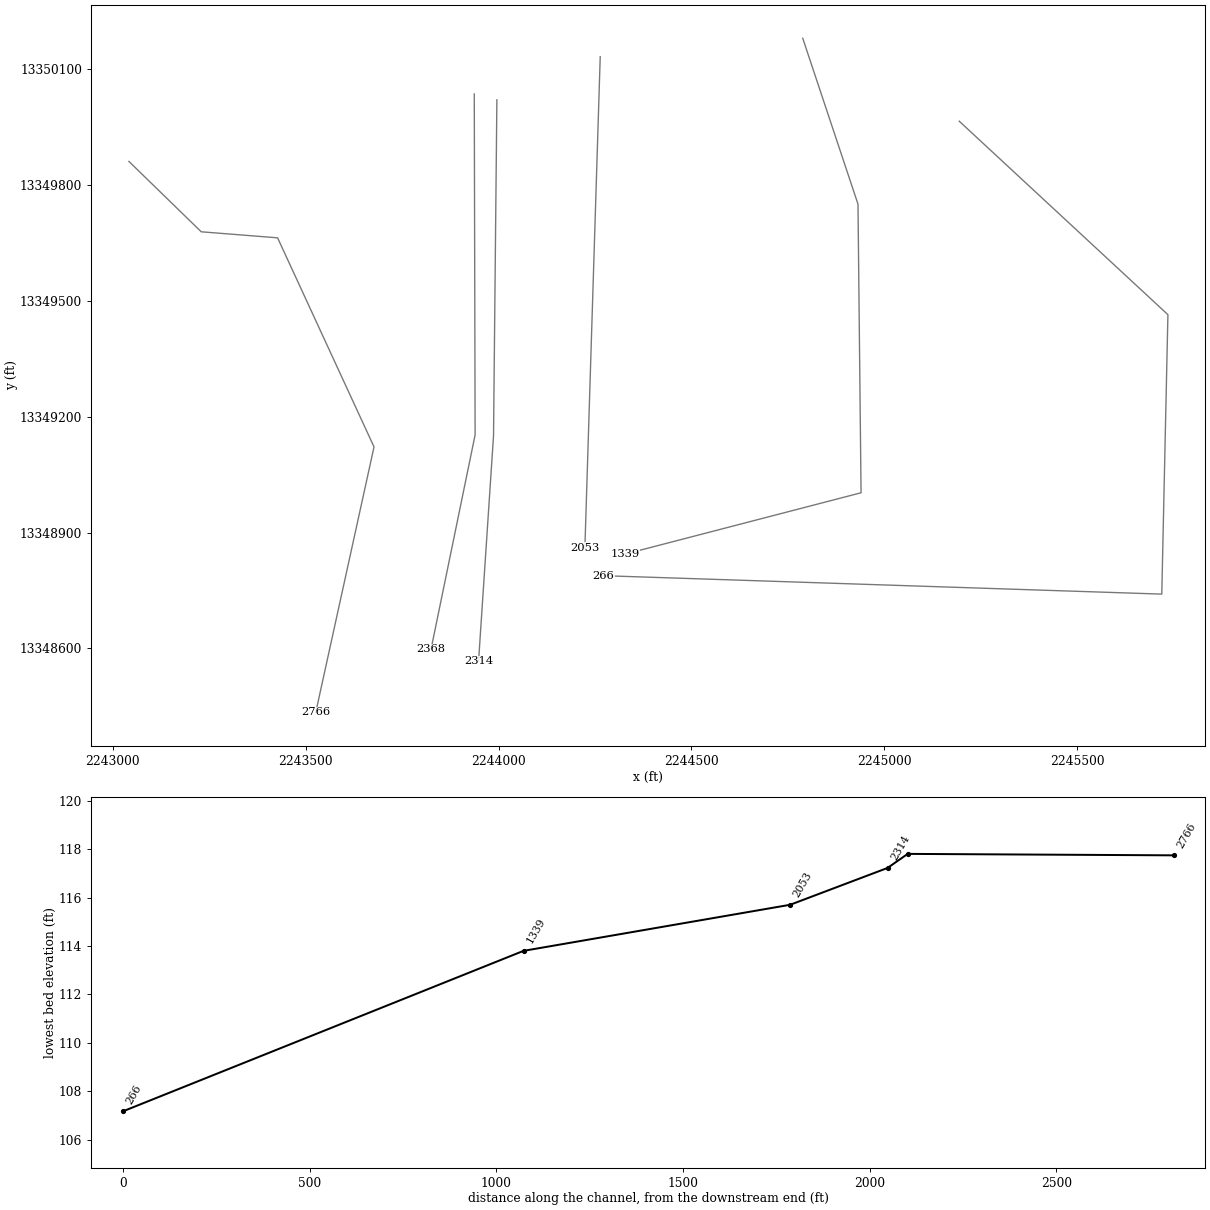
HEC-RAS study OLDS SLOUGH.prj: OLDS SLOUGH Base Level Engineering

--- OLDS SLOUGH.g01 (geometry) --- (continued)

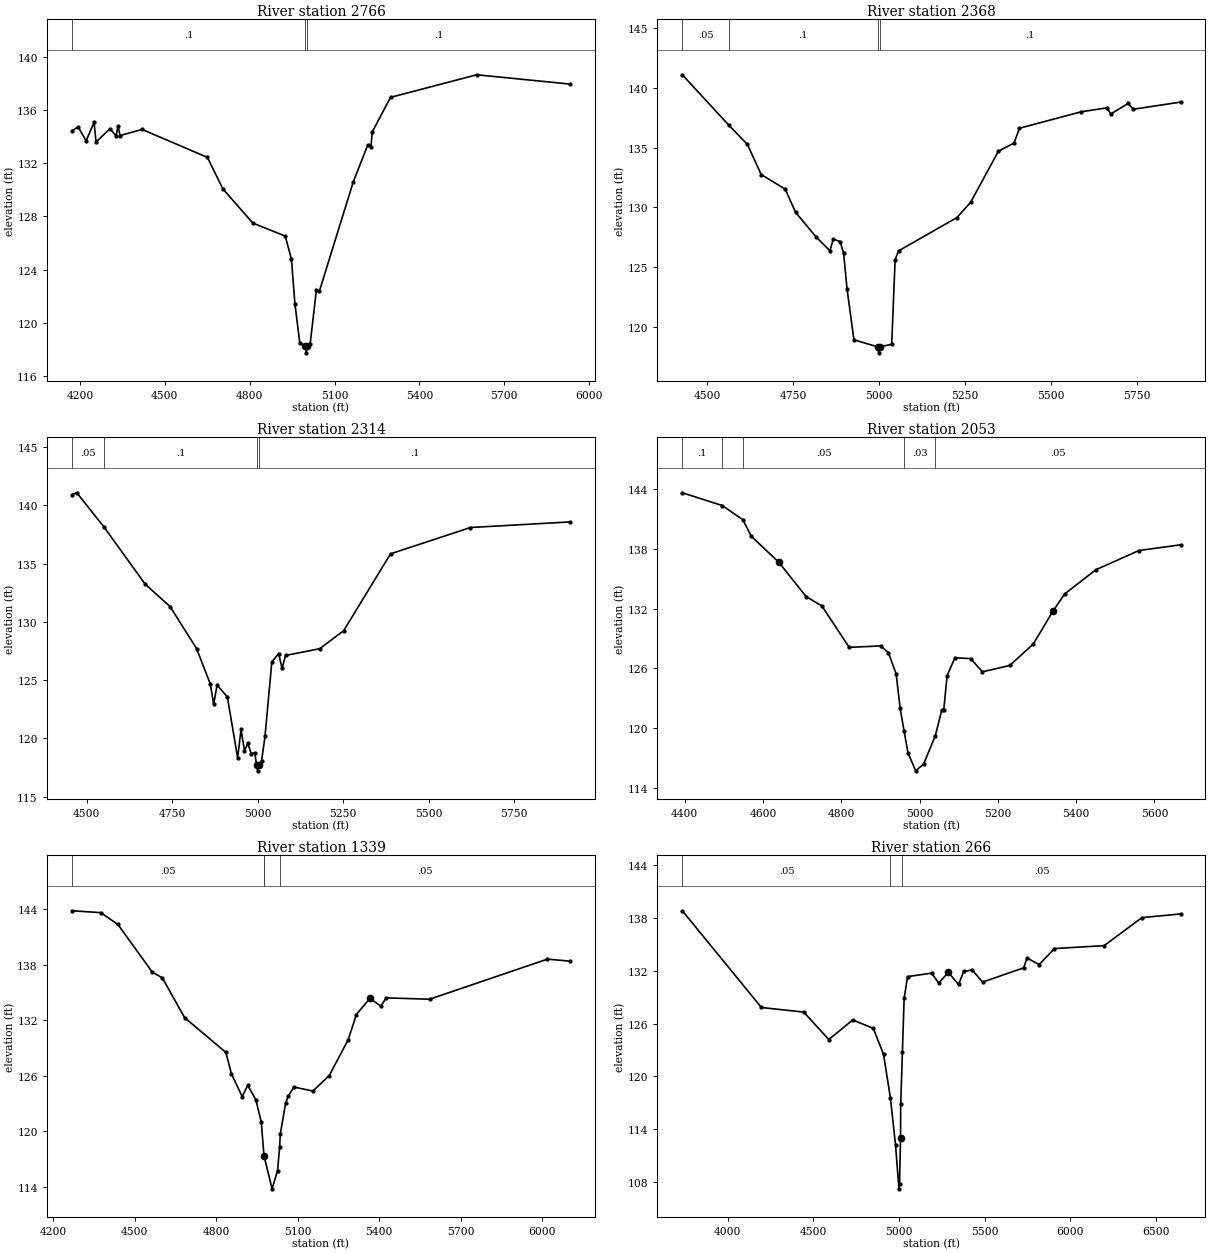
Type RM Length L Ch R = 1 ,2766    ,713,713,713
BEGIN DESCRIPTION:
Mapping XS 3033f12d
END DESCRIPTION:
XS GIS Cut Line= 5
      2243041.65     13349861.59      2243229.15     13349679.29
      2243427.07     13349663.67      2243677.07       13349122.
      2243526.03     13348434.52
#Sta/Elev= 30
  4171.9  134.41  4193.8  134.74  4222.1  133.68  4250.2  135.07  4257.3  133.59
  4306.7   134.6  4328.1  134.05    4335  134.82  4342.2  134.08  4419.9  134.54
  4650.7  132.44  4705.5  130.07  4811.3   127.5  4925.8  126.52  4947.8  124.79
    4960  121.45  4977.4  118.46  4997.4  118.24  5000.1  117.74  5003.4  118.24
  5013.9   118.4  5035.9  122.45  5046.3  122.36  5166.5  130.61  5217.9  133.39
  5228.5  133.25  5233.8  134.37  5297.9  136.95  5602.4  138.65  5932.4  137.95
#Mann= 3 ,-1 , 0
  4171.9      .1       0  4997.4     .07       0  5003.4      .1       0
Bank Sta=4997.4,5003.4
XS Rating Curve= 0 ,0
Exp/Cntr=0.3,0.1

Type RM Length L Ch R = 1 ,2368    ,54,54,54
BEGIN DESCRIPTION:
Mapping XS db498d
END DESCRIPTION:
XS GIS Cut Line= 3
      2243936.96     13350036.35      2243939.13     13349153.12
      2243824.79      13348597.7
#Sta/Elev= 30
  4427.8  141.11  4562.3  136.91  4617.3  135.27  4657.3  132.75  4727.3  131.52
  4757.3  129.59  4817.3  127.51  4857.3  126.36  4867.3  127.33  4887.3  127.13
  4897.3  126.13  4907.3  123.16  4927.3  118.89    4997   118.3  4999.8   117.8
    5003   118.3  5037.3  118.52  5047.3  125.62  5057.3  126.35  5227.3  129.14
  5267.3  130.43  5348.1  134.71  5393.2  135.38  5409.3  136.63  5589.4  138.01
  5664.6  138.34  5674.8  137.82  5725.8  138.71  5740.4  138.22  5878.1  138.82
#Mann= 4 ,-1 , 0
  4427.8     .05       0  4562.3      .1       0    4997     .07       0
    5003      .1       0
Bank Sta=4997,5003
XS Rating Curve= 0 ,0
Exp/Cntr=0.3,0.1

Type RM Length L Ch R = 1 ,2314    ,261,261,261
BEGIN DESCRIPTION:
Mapping XS db498d15
END DESCRIPTION:
XS GIS Cut Line= 3
      2243995.56     13350021.19      2243986.88     13349150.95
      2243948.06     13348566.53
#Sta/Elev= 30
  4457.1  140.92  4471.4  141.08  4551.8  138.11  4671.5  133.23    4744  131.32
  4821.5  127.71  4861.5  124.69  4871.5  122.93  4881.5  124.58  4911.5  123.56
  4941.5  118.34  4951.5  120.77  4961.5  118.95  4971.5  119.57  4981.5  118.67
  4991.5  118.79    4997  117.72  4999.8  117.22    5003  117.72  5011.5  118.08
  5021.5  120.17  5041.5  126.57  5061.5  127.28  5071.5  126.01  5081.5  127.12
  5181.5   127.7  5251.5  129.25  5388.4  135.84  5622.1   138.1  5913.1  138.58
#Mann= 4 ,-1 , 0
  4457.1     .05       0  4551.8      .1       0    4997     .07       0
    5003      .1       0
Bank Sta=4997,5003
XS Rating Curve= 0 ,0
Exp/Cntr=0.3,0.1

Type RM Length L Ch R = 1 ,2053    ,714,714,714
BEGIN DESCRIPTION:
Mapping XS db498d15
END DESCRIPTION:
XS GIS Cut Line= 2
      2244263.47     13350132.84      2244223.72     13348860.96
#Sta/Elev= 30
  4394.1  143.64  4495.8  142.36  4548.8  140.93  4570.2  139.27  4640.2  136.67
  4710.2  133.21  4750.3  132.28  4820.3  128.11  4900.3  128.25  4920.3  127.59
  4940.4  125.42  4950.4  121.98  4960.4  119.72  4970.4  117.52  4990.1   115.7
  5010.4  116.38  5040.4  119.24  5056.9  121.82  5061.9  121.84  5070.4  125.27
  5090.4  127.06  5130.4  126.98  5160.5  125.65  5230.5  126.29  5290.5  128.44
  5340.5  131.73  5370.6  133.47  5450.6  135.91  5560.7  137.84  5666.6  138.41
#Mann= 5 ,-1 , 0
  4394.1      .1       0  4495.8     .05       0  4548.8     .05       0
  4960.4     .03       0  5040.4     .05       0
Bank Sta=4640.2,5340.5
XS Rating Curve= 0 ,0
Exp/Cntr=0.3,0.1

Type RM Length L Ch R = 1 ,1339    ,1073,1073,1073
BEGIN DESCRIPTION:
Mapping XS 696b9aee
END DESCRIPTION:
XS GIS Cut Line= 4
      2244788.49      13350180.6       2244931.7     13349750.99
      2244939.65     13349003.21      2244327.15     13348844.12
#Sta/Elev= 30
  4269.3  143.82  4375.5  143.62  4438.7  142.34  4565.2   137.2  4602.1  136.58
  4684.3  132.28  4836.3  128.52  4856.3  126.22  4896.3  123.75  4916.3  124.98
  4946.3  123.43  4966.3  121.02  4976.3  117.38  5006.1   113.8  5026.3  115.76
 5034.09  118.37  5036.3  119.71  5056.3  123.11  5066.3  123.84  5086.3  124.79
  5156.3  124.36  5216.3  126.02  5286.3   129.9  5316.3  132.62  5366.3  134.37
  5406.3  133.52  5426.3  134.42  5585.6  134.27  6019.6   138.6  6102.8  138.38
#Mann= 4 ,-1 , 0
  4269.3     .05       0  4976.3      .1       0  4976.3     .03       0
 5034.09     .05       0
Bank Sta=4976.3,5366.3
XS Rating Curve= 0 ,0
Exp/Cntr=0.3,0.1

Type RM Length L Ch R = 1 ,266     ,0,0,0
BEGIN DESCRIPTION:
OLDS SLOUGH 1.0
END DESCRIPTION:
XS GIS Cut Line= 4
      2245194.19      13349965.8      2245735.16     13349464.61
      2245719.25     13348740.69      2244272.08      13348788.4
#Sta/Elev= 30
  3734.9  138.84  4196.6  127.83  4444.4   127.3  4590.1  124.18  4730.2  126.41
  4850.2  125.45  4910.2  122.48  4950.2  117.51  4980.2  112.13    5000  107.18
  5003.2  107.68 5009.38  113.02  5010.2   116.8  5020.2   122.8  5030.2  128.86
  5050.3  131.34  5190.3  131.74  5232.4   130.6    5288  131.83  5348.1  130.45
  5378.1  131.93  5428.1   132.1  5488.1  130.72  5728.3  132.34  5748.3  133.46
  5818.3  132.71  5908.4  134.54  6198.5  134.87  6418.6  138.06  6644.4  138.48
#Mann= 3 ,-1 , 0
  3734.9     .05       0  4950.2     .03       0  5020.2     .05       0
Bank Sta=5009.38,5288
XS Rating Curve= 0 ,0
Exp/Cntr=0.3,0.1

Chan Stop Cuts=-1
Use User Specified Reach Order=0
Composite Channel Slope=5