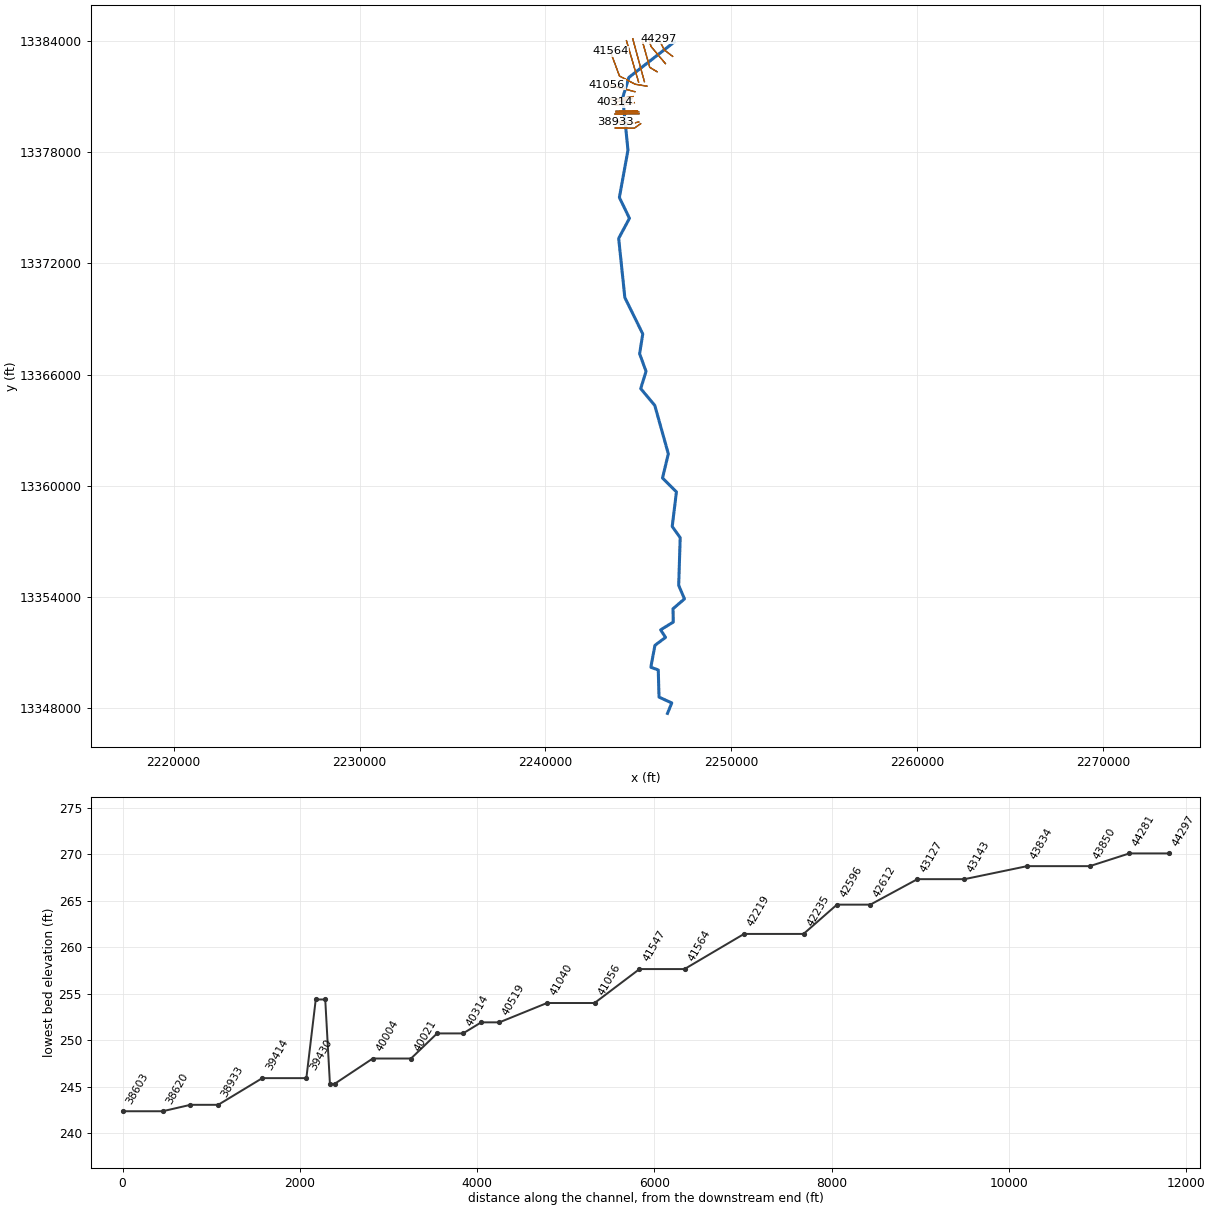
--- ROCK QUARRY BRANCH.prj (project) ---

Proj Title=ROCK QUARRY BRANCH Base Level Engineering
Current Plan=p01
Default Exp/Contr=0.3,0.1
English Units
Geom File=g01
Flow File=f01
Plan File=p01
Y Axis Title=Elevation
X Axis Title(PF)=Main Channel Distance
X Axis Title(XS)=Station
BEGIN DESCRIPTION:
ROCK QUARRY BRANCH
END DESCRIPTION:
DSS Export Rating Curves= 0
DSS Export Rating Curve Sorted= 0
DSS Export Volume Flow Curves= 0
DXF OffsetX= 0
DXF OffsetY= 0
DXF ScaleX= 1
DXF ScaleY= 10

--- ROCK QUARRY BRANCH.p01 (plan) ---

Plan Title=Multiple Run
Short Identifier=Multiple
Geom File=g01
Flow File=f01
Subcritical Flow
K Sum by GR= 0
Std Step Tol= 0.01
Critical Tol= 0.01
Num of Std Step Trials= 20
Max Error Tol= 0.3
Flow Tol Ratio= 0.001
Split Flow NTrial= 30
Split Flow Tol= 0.02
Split Flow Ratio= 0.02
Log Output Level= 0
Friction Slope Method= 1
Unsteady Friction Slope Method= 2
Unsteady Bridges Friction Slope Method= 1
Parabolic Critical Depth
Global Vel Dist=  1 , 1 , 1
Global Log Level= 0
CheckData=True
Encroach Param= -1, 0, 0, 0
BEGIN DESCRIPTION:
Multiple Run
END DESCRIPTION:

--- ROCK QUARRY BRANCH.f01 (steady flow) ---

Flow Title=Multiple
Program Version=4.10
Number of Profiles= 7
Profile Names=10-year,25-year,50-year,1pct_min,100-year,1pct_plu,500-year
River Rch & RM=ROCK QUARRY BRAN,Reach-1         ,44297
     191     260     316     282     382     516     566
River Rch & RM=ROCK QUARRY BRAN,Reach-1         ,42219
     256     354     435     392     530     717     802
River Rch & RM=ROCK QUARRY BRAN,Reach-1         ,37384
     433     613     765     701     948    1282    1478
River Rch & RM=ROCK QUARRY BRAN,Reach-1         ,32959
     476     676     846     776    1050    1420    1643
River Rch & RM=ROCK QUARRY BRAN,Reach-1         ,28202
     548     784     985     908    1228    1660    1938
River Rch & RM=ROCK QUARRY BRAN,Reach-1         ,26726
     598     859    1082     999    1351    1828    2143
River Rch & RM=ROCK QUARRY BRAN,Reach-1         ,24764
     616     884    1113    1027    1389    1879    2199
River Rch & RM=ROCK QUARRY BRAN,Reach-1         ,22201
     707    1022    1294    1201    1624    2196    2598
River Rch & RM=ROCK QUARRY BRAN,Reach-1         ,19435
     721    1043    1321    1226    1659    2243    2656
River Rch & RM=ROCK QUARRY BRAN,Reach-1         ,17418
     719    1040    1317    1222    1652    2234    2642
River Rch & RM=ROCK QUARRY BRAN,Reach-1         ,14986
     819    1189    1509    1403    1898    2567    3050
River Rch & RM=ROCK QUARRY BRAN,Reach-1         ,10928
     885    1289    1640    1528    2066    2794    3332
River Rch & RM=ROCK QUARRY BRAN,Reach-1         ,6809
    1017    1489    1901    1777    2403    3250    3903
River Rch & RM=ROCK QUARRY BRAN,Reach-1         ,1419
    1359    2012    2589    2437    3296    4458    5429
Boundary for River Rch & Prof#=ROCK QUARRY BRAN,Reach-1         , 1
Up Type= 0
Dn Type= 3
Dn Slope=0.0053
Boundary for River Rch & Prof#=ROCK QUARRY BRAN,Reach-1         , 2
Up Type= 0
Dn Type= 3
Dn Slope=0.0053
Boundary for River Rch & Prof#=ROCK QUARRY BRAN,Reach-1         , 3
Up Type= 0
Dn Type= 3
Dn Slope=0.0053
Boundary for River Rch & Prof#=ROCK QUARRY BRAN,Reach-1         , 4
Up Type= 0
Dn Type= 3
Dn Slope=0.0053
Boundary for River Rch & Prof#=ROCK QUARRY BRAN,Reach-1         , 5
Up Type= 0
Dn Type= 3
Dn Slope=0.0053
Boundary for River Rch & Prof#=ROCK QUARRY BRAN,Reach-1         , 6
Up Type= 0
Dn Type= 3
Dn Slope=0.0053
Boundary for River Rch & Prof#=ROCK QUARRY BRAN,Reach-1         , 7
Up Type= 0
Dn Type= 3
Dn Slope=0.0053
DSS Import GetInterval= 0
DSS Import GetPeak= 0
DSS Import FillOption= 0

--- ROCK QUARRY BRANCH.g01 (geometry) ---

Geom Title=Existing Conditions
Program Version=4.10

River Reach=ROCK QUARRY BRAN,Reach-1
Reach XY= 30
      2246937.72     13383926.86        2244486.     13382010.64
       2244153.4     13380912.57      2244437.51     13378092.17
      2243975.57     13375542.15      2244517.75     13374416.98
      2243937.74     13373336.73      2244268.96     13370147.31
      2245233.43     13368185.95      2245064.02     13367116.84
      2245409.66     13366171.36       2245123.2     13365239.29
       2245880.2     13364331.09       2246608.3     13361725.62
      2246294.86     13360418.34      2247044.36     13359675.61
      2246817.62     13357811.96      2247246.51     13357206.35
      2247166.11     13354634.65      2247476.27     13353907.25
      2246861.18     13353375.72      2246873.36     13352657.61
      2246195.49     13352237.73      2246456.67     13351832.31
      2245887.61     13351402.29      2245667.13     13350223.08
      2246066.91      13350077.2      2246107.24     13348612.04
      2246793.52     13348299.69      2246562.31     13347736.87

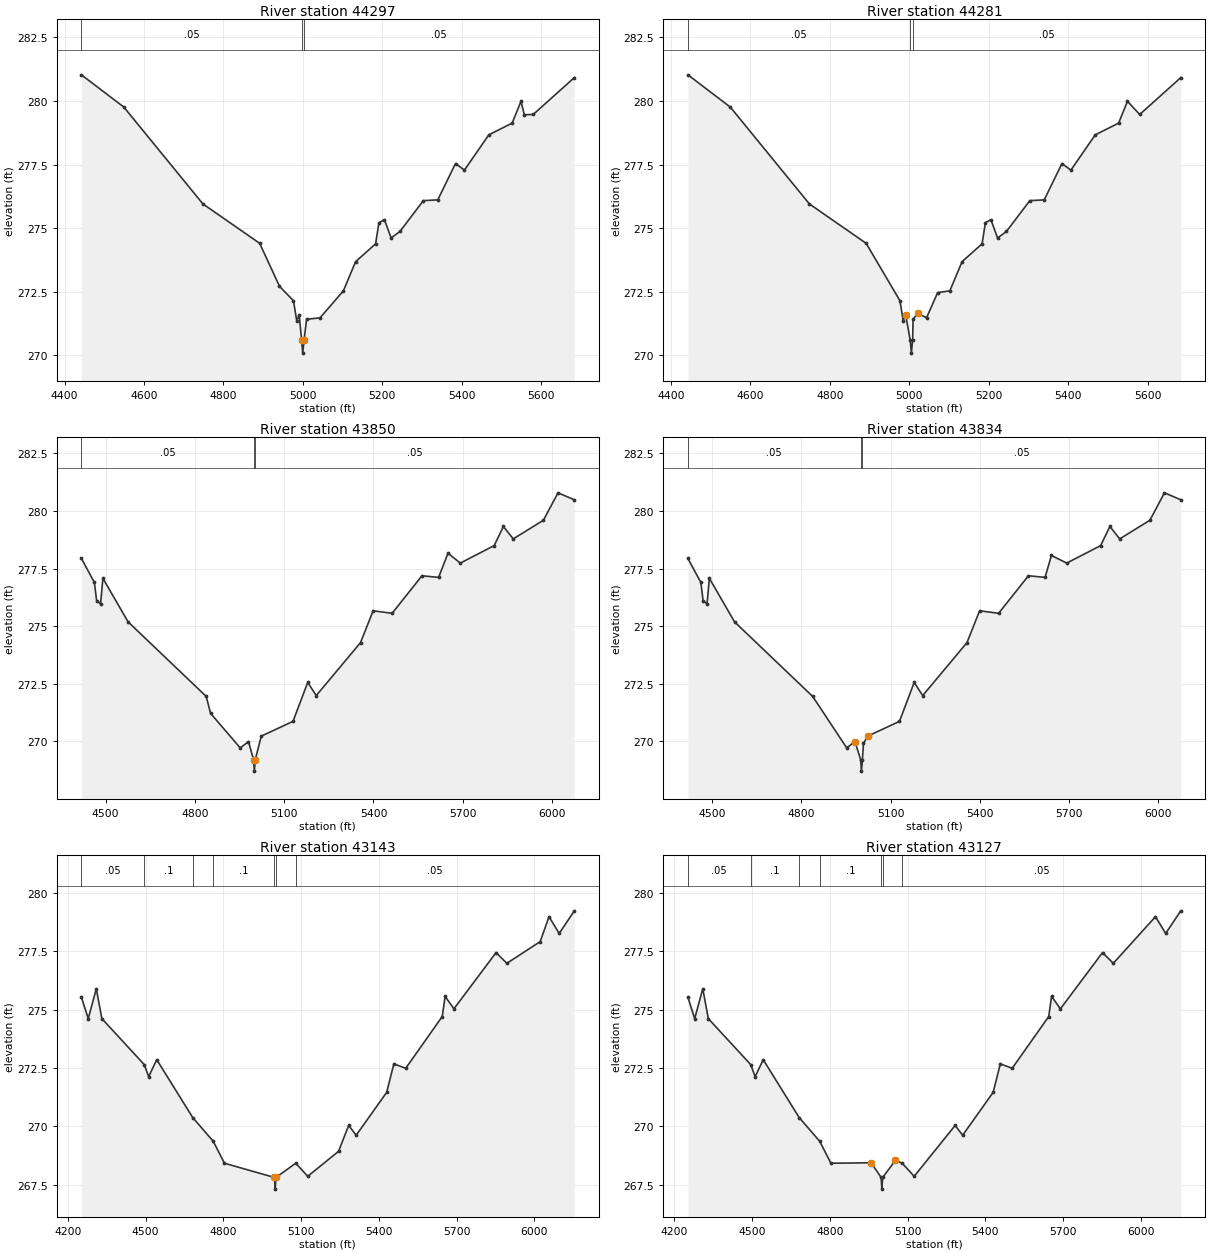
Type RM Length L Ch R = 1 ,44297   ,447,447,447
BEGIN DESCRIPTION:
ROCK QUARRY BRANCH 84.0
END DESCRIPTION:
XS GIS Cut Line= 3
      2246837.72     13383146.85      2246387.72     13383496.85
      2246087.72     13384096.85
#Sta/Elev= 30
  4442.6  281.03  4549.4  279.76  4748.5  275.95  4891.4   274.4  4941.2  272.71
  4976.5  272.14  4984.6  271.36    4991  271.58    4997  270.58  4999.8  270.08
    5003  270.58  5009.5  271.41  5043.4  271.47  5102.1  272.53  5132.9  273.68
  5183.2  274.38  5191.6  275.21  5205.5  275.33  5222.3  274.61  5244.7  274.87
  5303.4  276.08  5339.7  276.11  5384.4  277.54  5406.8  277.28  5468.3  278.67
    5527  279.13  5549.3  279.99  5557.7  279.46  5580.1  279.47  5683.5  280.92
#Mann= 3 ,-1 , 0
  4442.6     .05       0    4997     .03       0    5003     .05       0
Bank Sta=4997,5003
XS Rating Curve= 0 ,0
Exp/Cntr=0.3,0.1

Type RM Length L Ch R = 1 ,44281   ,447,447,447
BEGIN DESCRIPTION:
ROCK QUARRY BRANCH 84.0
END DESCRIPTION:
XS GIS Cut Line= 3
      2246837.72     13383146.85      2246387.72     13383496.85
      2246087.72     13384096.85
#Sta/Elev= 30
  4442.6  281.03  4549.4  279.76  4748.5  275.95  4891.4   274.4  4976.5  272.14
  4984.6  271.36    4991  271.58  5002.4  270.58  5005.2  270.08  5008.4  270.58
  5009.5  271.41  5021.1  271.65  5043.4  271.47  5071.4  272.46  5102.1  272.53
  5132.9  273.68  5183.2  274.38  5191.6  275.21  5205.5  275.33  5222.3  274.61
  5244.7  274.87  5303.4  276.08  5339.7  276.11  5384.4  277.54  5406.8  277.28
  5468.3  278.67    5527  279.13  5549.3  279.99  5580.1  279.47  5683.5  280.92
#Mann= 3 ,-1 , 0
  4442.6     .05       0  5002.4     .03       0  5008.4     .05       0
Bank Sta=4991,5021.1
XS Rating Curve= 0 ,0
Exp/Cntr=0.3,0.1

Type RM Length L Ch R = 1 ,43850   ,707,707,707
BEGIN DESCRIPTION:
ROCK QUARRY BRANCH 83.0
END DESCRIPTION:
XS GIS Cut Line= 3
      2246449.96      13382757.7      2245673.91      13383684.8
      2245559.32     13384117.14
#Sta/Elev= 30
  4418.7  277.94  4462.2   276.9  4469.8  276.11    4483  275.97  4490.8  277.08
  4575.4  275.19  4838.2  271.95  4852.5  271.22  4952.3  269.72  4980.1  269.99
    4997  269.21  4999.8  268.71    5003  269.21    5023  270.23  5129.7  270.87
  5179.1  272.56  5207.8  271.99  5356.6  274.29    5399  275.67  5462.8  275.56
    5563  277.19    5619  277.12  5650.6  278.17  5691.9  277.74  5805.7   278.5
  5836.8  279.33  5869.8  278.79  5971.3   279.6  6020.2  280.79    6075  280.49
#Mann= 3 ,-1 , 0
  4418.7     .05       0    4997     .03       0    5003     .05       0
Bank Sta=4997,5003
XS Rating Curve= 0 ,0
Exp/Cntr=0.3,0.1

Type RM Length L Ch R = 1 ,43834   ,707,707,707
BEGIN DESCRIPTION:
ROCK QUARRY BRANCH 83.0
END DESCRIPTION:
XS GIS Cut Line= 3
      2246449.96      13382757.7      2245673.91      13383684.8
      2245559.32     13384117.14
#Sta/Elev= 30
  4418.7  277.94  4462.2   276.9  4469.8  276.11    4483  275.97  4490.8  277.08
  4575.4  275.19  4838.2  271.95  4952.3  269.72  4980.1  269.99  4999.2  269.21
  5001.9  268.71  5005.2  269.21  5008.7  269.91    5023  270.23  5129.7  270.87
  5179.1  272.56  5207.8  271.99  5356.6  274.29    5399  275.67  5462.8  275.56
    5563  277.19    5619  277.12  5640.2  278.07  5691.9  277.74  5805.7   278.5
  5836.8  279.33  5869.8  278.79  5971.3   279.6  6020.2  280.79    6075  280.49
#Mann= 3 ,-1 , 0
  4418.7     .05       0  4999.2     .03       0  5005.2     .05       0
Bank Sta=4980.1,5023
XS Rating Curve= 0 ,0
Exp/Cntr=0.3,0.1

Type RM Length L Ch R = 1 ,43143   ,531,531,531
BEGIN DESCRIPTION:
ROCK QUARRY BRANCH 82.0
END DESCRIPTION:
XS GIS Cut Line= 3
      2245998.08     13382319.99      2245607.48     13382554.35
      2245216.85      13383947.6
#Sta/Elev= 30
    4252  275.53  4278.3  274.62  4309.4   275.9  4330.8  274.62  4494.3  272.65
  4511.6  272.13  4542.7  272.86  4681.4  270.38  4760.9  269.36    4804  268.42
    4997  267.81  4999.8  267.31    5003  267.81  5079.3  268.42  5125.5  267.86
  5244.4  268.93  5283.6  270.04  5312.5  269.62  5430.4  271.46  5457.9  272.68
  5503.8  272.49  5644.8  274.71  5655.8  275.57  5689.9  275.04  5852.5  277.45
  5894.1  276.99  6022.8  277.92  6056.9  278.99  6096.2  278.27  6154.5  279.24
#Mann= 7 ,-1 , 0
    4252     .05       0  4494.3      .1       0  4681.4     .05       0
  4760.9      .1       0    4997     .07       0    5003      .1       0
  5079.3     .05       0
Bank Sta=4997,5003
XS Rating Curve= 0 ,0
Exp/Cntr=0.3,0.1

Type RM Length L Ch R = 1 ,43127   ,531,531,531
BEGIN DESCRIPTION:
ROCK QUARRY BRANCH 82.0
END DESCRIPTION:
XS GIS Cut Line= 3
      2245998.08     13382319.99      2245607.48     13382554.35
      2245216.85      13383947.6
#Sta/Elev= 30
    4252  275.53  4278.3  274.62  4309.4   275.9  4330.8  274.62  4494.3  272.65
  4511.6  272.13  4542.7  272.86  4681.4  270.38  4760.9  269.36    4804  268.42
  4959.4  268.44  4997.9  267.81  5000.7  267.31  5003.9  267.81  5052.8  268.54
  5079.3  268.42  5125.5  267.86  5283.6  270.04  5312.5  269.62  5430.4  271.46
  5457.9  272.68  5503.8  272.49  5644.8  274.71  5655.8  275.57  5689.9  275.04
  5852.5  277.45  5894.1  276.99  6056.9  278.99  6096.2  278.27  6154.5  279.24
#Mann= 7 ,-1 , 0
    4252     .05       0  4494.3      .1       0  4681.4     .05       0
  4760.9      .1       0  4997.9     .07       0  5003.9      .1       0
  5079.3     .05       0
Bank Sta=4959.4,5052.8
XS Rating Curve= 0 ,0
Exp/Cntr=0.3,0.1

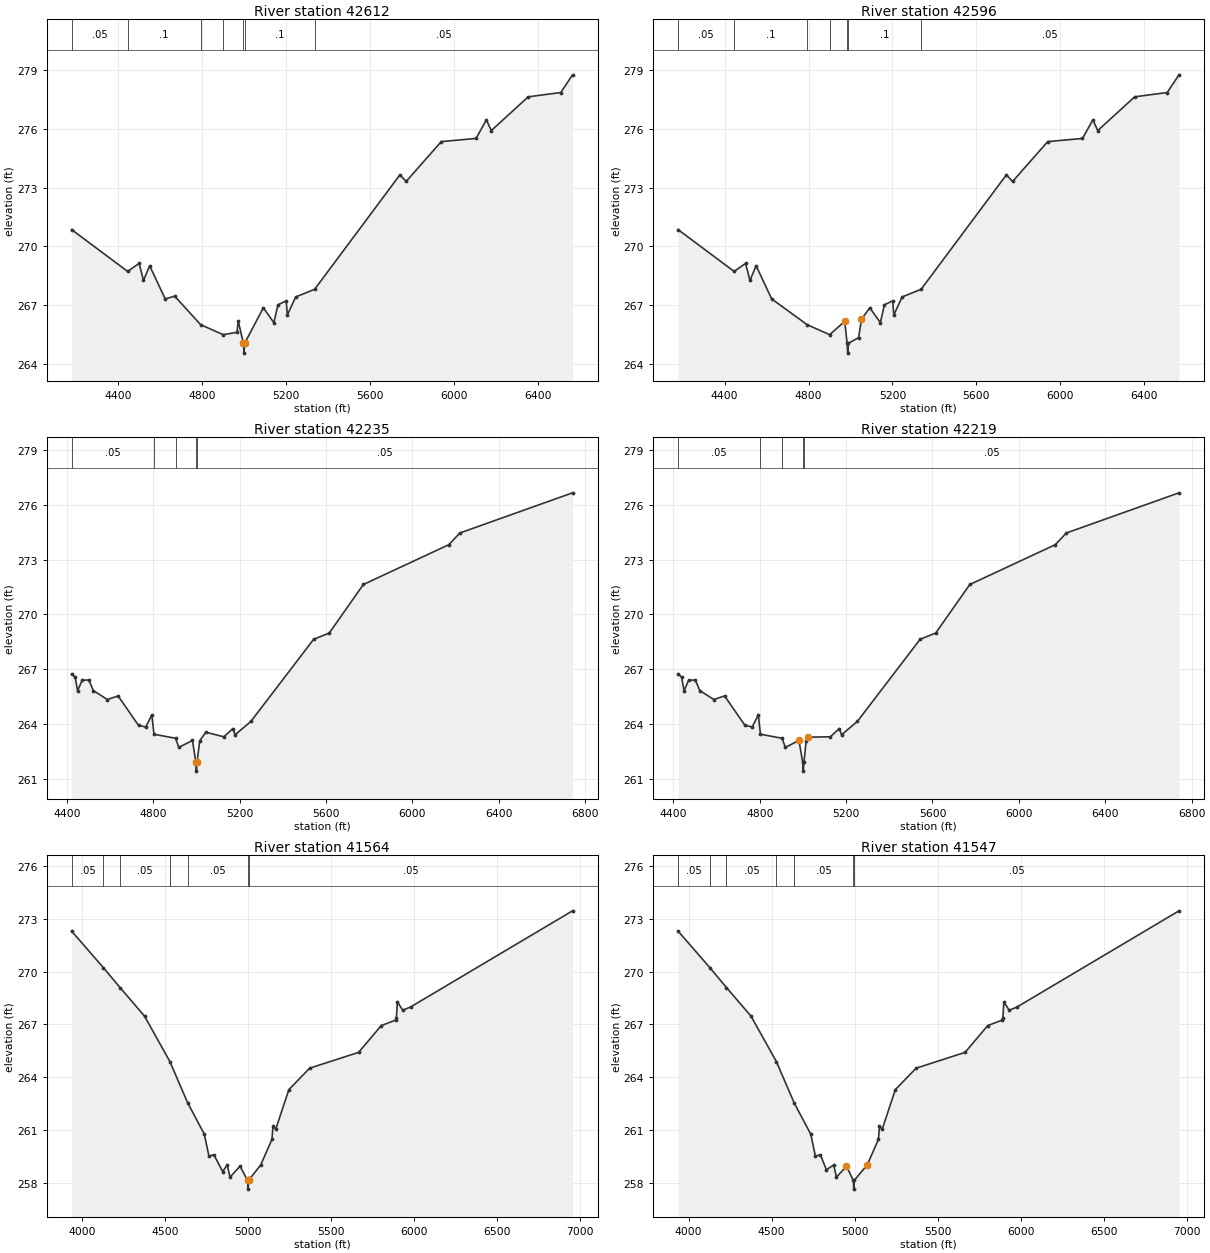
Type RM Length L Ch R = 1 ,42612   ,377,377,377
BEGIN DESCRIPTION:
ROCK QUARRY BRANCH 81.0
END DESCRIPTION:
XS GIS Cut Line= 2
      2245321.02     13381786.12      2244696.03     13384090.78
#Sta/Elev= 30
    4178  270.86  4445.3  268.73    4500  269.14  4520.7  268.27  4550.1  269.02
  4624.3  267.33  4669.6  267.47    4793  266.02  4900.7  265.51  4966.2  265.63
  4972.6  266.19    4997  265.07  4999.8  264.57    5003  265.07  5092.1  266.88
  5142.4  266.12  5161.4  267.03  5201.2  267.23  5206.4  266.51  5246.2  267.43
  5336.6  267.82  5743.3  273.65  5772.7  273.31  5940.2  275.34  6105.9   275.5
  6155.4  276.45  6178.5   275.9  6354.6  277.62    6510  277.84  6565.9  278.74
#Mann= 7 ,-1 , 0
    4178     .05       0  4445.3      .1       0    4793     .05       0
  4900.7      .1       0    4997     .07       0    5003      .1       0
  5336.6     .05       0
Bank Sta=4997,5003
XS Rating Curve= 0 ,0
Exp/Cntr=0.3,0.1

Type RM Length L Ch R = 1 ,42596   ,377,377,377
BEGIN DESCRIPTION:
ROCK QUARRY BRANCH 81.0
END DESCRIPTION:
XS GIS Cut Line= 2
      2245321.02     13381786.12      2244696.03     13384090.78
#Sta/Elev= 30
    4178  270.86  4445.3  268.73    4500  269.14  4520.7  268.27  4550.1  269.02
  4624.3  267.33    4793  266.02  4900.7  265.51  4972.6  266.19  4983.9  265.07
  4986.7  264.57  4989.9  265.07  5038.7  265.36  5052.3  266.29  5092.1  266.88
  5142.4  266.12  5161.4  267.03  5201.2  267.23  5206.4  266.51  5246.2  267.43
  5336.6  267.82  5743.3  273.65  5772.7  273.31  5940.2  275.34  6105.9   275.5
  6155.4  276.45  6178.5   275.9  6354.6  277.62    6510  277.84  6565.9  278.74
#Mann= 7 ,-1 , 0
    4178     .05       0  4445.3      .1       0    4793     .05       0
  4900.7      .1       0  4983.9     .07       0  4989.9      .1       0
  5336.6     .05       0
Bank Sta=4972.6,5052.3
XS Rating Curve= 0 ,0
Exp/Cntr=0.3,0.1

Type RM Length L Ch R = 1 ,42235   ,671,671,671
BEGIN DESCRIPTION:
ROCK QUARRY BRANCH 80.0
END DESCRIPTION:
XS GIS Cut Line= 2
      2245008.52     13381760.06      2244357.48     13383986.63
#Sta/Elev= 30
  4421.8  266.74  4438.3  266.57  4449.7  265.82  4470.6   266.4  4501.8  266.41
  4522.6  265.83  4587.7  265.34  4637.2  265.54  4731.9  263.92  4765.3  263.84
  4793.5   264.5  4803.3  263.44  4903.3  263.22  4918.6  262.72  4981.6   263.1
    4997  261.92  4999.8  261.42    5003  261.92  5015.1  263.08  5043.3  263.55
  5126.9   263.3  5168.6  263.75    5179  263.41    5252  264.14  5542.8  268.64
  5614.9  268.98  5772.9  271.64  6168.8  273.82  6219.9  274.46  6741.6  276.66
#Mann= 5 ,-1 , 0
  4421.8     .05       0  4803.3     .08       0  4903.3     .05       0
    4997     .03       0    5003     .05       0
Bank Sta=4997,5003
XS Rating Curve= 0 ,0
Exp/Cntr=0.3,0.1

Type RM Length L Ch R = 1 ,42219   ,672,672,672
BEGIN DESCRIPTION:
ROCK QUARRY BRANCH 80.0
END DESCRIPTION:
XS GIS Cut Line= 2
      2245008.52     13381760.06      2244357.48     13383986.63
#Sta/Elev= 30
  4421.8  266.74  4438.3  266.57  4449.7  265.82  4470.6   266.4  4501.8  266.41
  4522.6  265.83  4587.7  265.34  4637.2  265.54  4731.9  263.92  4765.3  263.84
  4793.5   264.5  4803.3  263.44  4903.3  263.22  4918.6  262.72  4981.6   263.1
  4998.9  261.92  5001.7  261.42  5004.9  261.92  5015.1  263.08  5022.7  263.28
  5126.9   263.3  5168.6  263.75    5179  263.41    5252  264.14  5542.8  268.64
  5614.9  268.98  5772.9  271.64  6168.8  273.82  6219.9  274.46  6741.6  276.66
#Mann= 5 ,-1 , 0
  4421.8     .05       0  4803.3     .08       0  4903.3     .05       0
  4998.9     .03       0  5004.9     .05       0
Bank Sta=4981.6,5022.7
XS Rating Curve= 0 ,0
Exp/Cntr=0.3,0.1

Type RM Length L Ch R = 1 ,41564   ,508,508,508
BEGIN DESCRIPTION:
ROCK QUARRY BRANCH 79.0
END DESCRIPTION:
XS GIS Cut Line= 4
       2245451.2     13381538.73      2244826.23     13381642.89
      2243979.87      13382085.6       2243485.1      13383426.7
#Sta/Elev= 30
  3936.5   272.3  4128.2  270.22  4228.3  269.09    4376  267.47  4528.6  264.89
    4636  262.54  4736.3  260.76    4764  259.52  4794.1  259.59  4846.6  258.64
  4874.3  259.01  4890.8  258.32  4951.3  258.94    4997  258.14  4999.8  257.64
    5003  258.14  5076.3  259.02    5144  260.47    5150  261.23  5166.4  261.04
  5245.5  263.29  5370.7  264.51    5666  265.41  5802.2  266.93  5888.1  267.24
  5893.5  267.38  5899.6  268.28  5931.6   267.8  5979.4  267.99  6954.7  273.45
#Mann= 7 ,-1 , 0
  3936.5     .05       0  4128.2     .08       0  4228.3     .05       0
  4528.6     .08       0    4636     .05       0    4997     .03       0
    5003     .05       0
Bank Sta=4997,5003
XS Rating Curve= 0 ,0
Exp/Cntr=0.3,0.1

Type RM Length L Ch R = 1 ,41547   ,507,507,507
BEGIN DESCRIPTION:
ROCK QUARRY BRANCH 79.0
END DESCRIPTION:
XS GIS Cut Line= 4
       2245451.2     13381538.73      2244826.23     13381642.89
      2243979.87      13382085.6       2243485.1      13383426.7
#Sta/Elev= 30
  3936.5   272.3  4128.2  270.22  4228.3  269.09    4376  267.47  4528.6  264.89
    4636  262.54  4736.3  260.76    4764  259.52  4794.1  259.59  4830.2  258.74
  4874.3  259.01  4890.8  258.32  4951.3  258.94  4992.5  258.14  4995.2  257.64
  4998.5  258.14  5076.3  259.02    5144  260.47    5150  261.23  5166.4  261.04
  5245.5  263.29  5370.7  264.51    5666  265.41  5802.2  266.93  5888.1  267.24
  5893.5  267.38  5899.6  268.28  5931.6   267.8  5979.4  267.99  6954.7  273.45
#Mann= 7 ,-1 , 0
  3936.5     .05       0  4128.2     .08       0  4228.3     .05       0
  4528.6     .08       0    4636     .05       0  4992.5     .03       0
  4998.5     .05       0
Bank Sta=4951.3,5076.3
XS Rating Curve= 0 ,0
Exp/Cntr=0.3,0.1

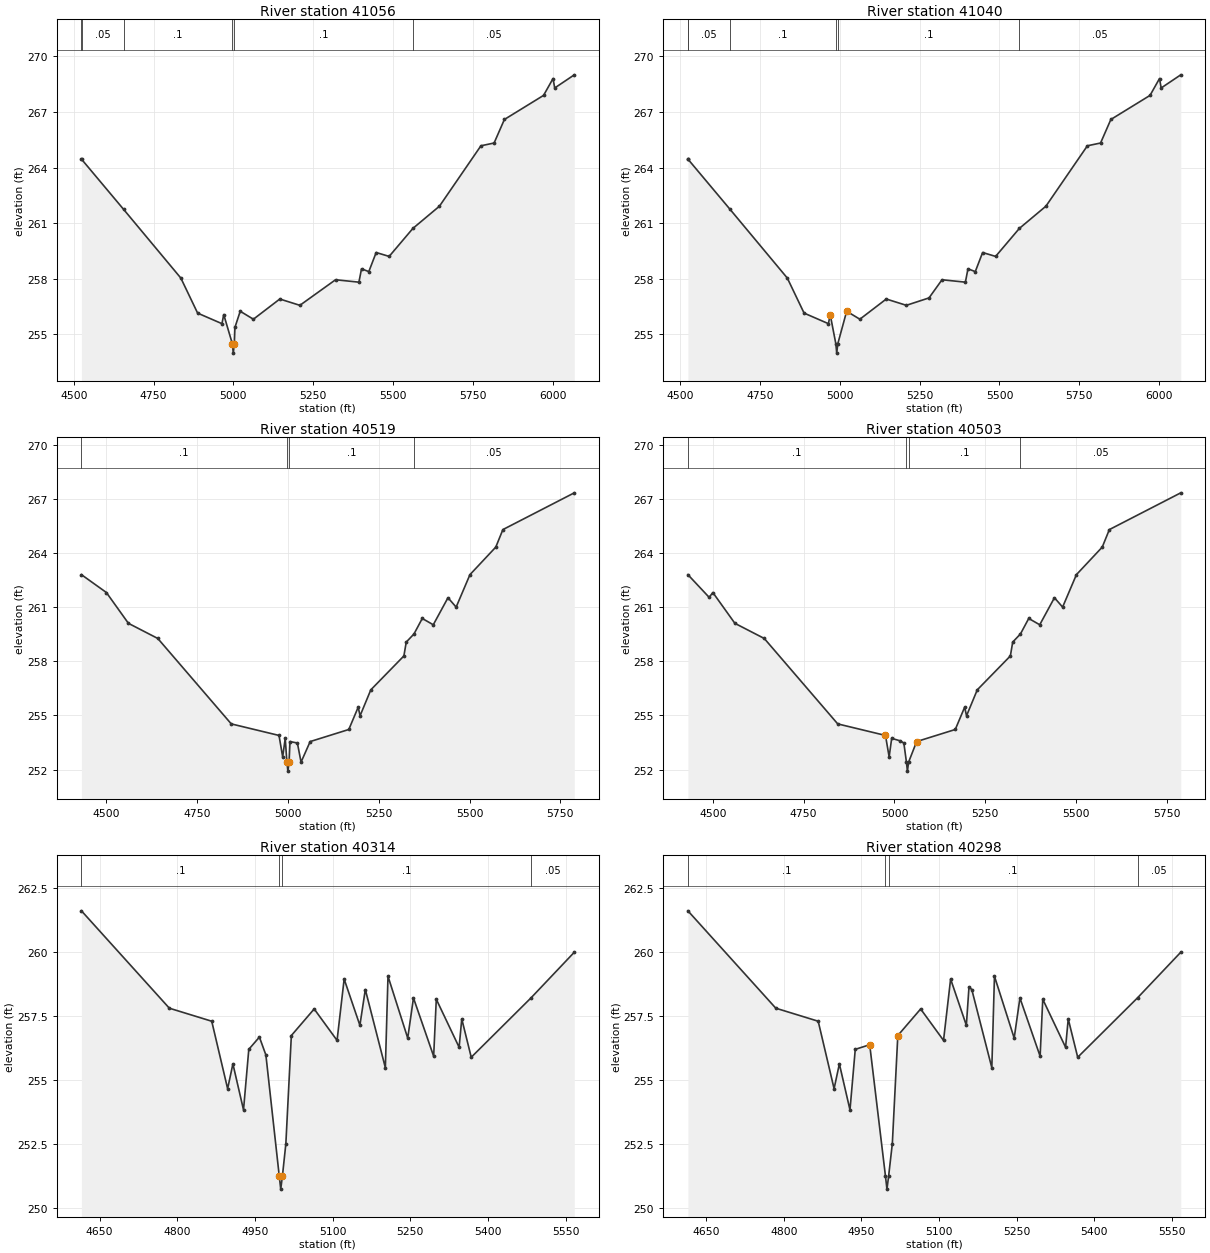
Type RM Length L Ch R = 1 ,41056   ,537,537,537
BEGIN DESCRIPTION:
ROCK QUARRY BRANCH 78.0
END DESCRIPTION:
XS GIS Cut Line= 2
       2244809.3      13381242.1      2243314.49     13381627.52
#Sta/Elev= 30
  4524.2  264.45  4524.8  264.45  4656.2  261.75  4835.6  258.04  4888.1  256.15
  4964.3  255.58  4969.9  256.07    4997  254.49  4999.8  253.99    5003  254.49
    5005  255.38  5021.5  256.25  5062.8  255.82  5145.5  256.91  5208.4  256.57
  5320.1  257.95  5393.3  257.82  5401.4  258.54  5424.3  258.39  5447.3  259.42
    5488  259.21  5562.3  260.72  5645.5  261.92  5775.4  265.18  5816.7  265.33
  5848.9   266.6  5971.6   267.9  6001.3  268.81  6006.5   268.3  6067.9  269.01
#Mann= 6 ,-1 , 0
  4524.2      .1       0  4524.8     .05       0  4656.2      .1       0
    4997     .07       0    5003      .1       0  5562.3     .05       0
Bank Sta=4997,5003
XS Rating Curve= 0 ,0
Exp/Cntr=0.3,0.1

Type RM Length L Ch R = 1 ,41040   ,537,537,537
BEGIN DESCRIPTION:
ROCK QUARRY BRANCH 78.0
END DESCRIPTION:
XS GIS Cut Line= 2
       2244809.3      13381242.1      2243314.49     13381627.52
#Sta/Elev= 30
  4524.2  264.45  4524.8  264.45  4656.2  261.75  4835.6  258.04  4888.1  256.15
  4964.3  255.58  4969.9  256.07  4987.6  254.49  4990.3  253.99  4993.6  254.49
  5021.5  256.25  5062.8  255.82  5145.5  256.91  5208.4  256.57  5279.4  256.97
  5320.1  257.95  5393.3  257.82  5401.4  258.54  5424.3  258.39  5447.3  259.42
    5488  259.21  5562.3  260.72  5645.5  261.92  5775.4  265.18  5816.7  265.33
  5848.9   266.6  5971.6   267.9  6001.3  268.81  6006.5   268.3  6067.9  269.01
#Mann= 6 ,-1 , 0
  4524.2      .1       0  4524.8     .05       0  4656.2      .1       0
  4987.6     .07       0  4993.6      .1       0  5562.3     .05       0
Bank Sta=4969.9,5021.5
XS Rating Curve= 0 ,0
Exp/Cntr=0.3,0.1

Type RM Length L Ch R = 1 ,40519   ,205,205,205
BEGIN DESCRIPTION:
ROCK QUARRY BRANCH 77.0
END DESCRIPTION:
XS GIS Cut Line= 3
      2244715.62     13380976.47      2243653.08     13380815.01
      2243372.25     13380846.21
#Sta/Elev= 30
  4431.2  262.81  4499.9  261.82  4560.6  260.11  4641.5  259.27  4843.8  254.53
  4975.3  253.89  4985.4   252.7  4992.4  253.73    4997  252.41  4999.8  251.91
    5003  252.41  5005.6  253.55  5025.9  253.47    5036  252.41  5061.1  253.55
  5167.5  254.22  5193.4  255.46  5198.5  254.98  5228.1  256.42  5319.2   258.3
  5325.7  259.07    5347  259.52  5369.8  260.38  5400.1  260.03  5440.6  261.53
  5463.1  261.01  5501.1  262.81  5572.3  264.34  5591.8  265.31  5788.5  267.35
#Mann= 4 ,-1 , 0
  4431.2      .1       0    4997     .07       0    5003      .1       0
    5347     .05       0
Bank Sta=4997,5003
XS Rating Curve= 0 ,0
Exp/Cntr=0.3,0.1

Type RM Length L Ch R = 1 ,40503   ,205,205,205
BEGIN DESCRIPTION:
ROCK QUARRY BRANCH 77.0
END DESCRIPTION:
XS GIS Cut Line= 3
      2244715.62     13380976.47      2243653.08     13380815.01
      2243372.25     13380846.21
#Sta/Elev= 30
  4431.2  262.81  4489.8  261.55  4499.9  261.82  4560.6  260.11  4641.5  259.27
  4843.8  254.53  4975.3  253.89  4985.4   252.7  4992.4  253.73  5015.7  253.59
  5025.9  253.47    5033  252.41  5035.7  251.91    5039  252.41  5061.1  253.55
  5167.5  254.22  5193.4  255.46  5198.5  254.98  5228.1  256.42  5319.2   258.3
  5325.7  259.07    5347  259.52  5369.8  260.38  5400.1  260.03  5440.6  261.53
  5463.1  261.01  5501.1  262.81  5572.3  264.34  5591.8  265.31  5788.5  267.35
#Mann= 4 ,-1 , 0
  4431.2      .1       0    5033     .07       0    5039      .1       0
    5347     .05       0
Bank Sta=4975.3,5061.1
XS Rating Curve= 0 ,0
Exp/Cntr=0.3,0.1

Type RM Length L Ch R = 1 ,40314   ,293,293,293
BEGIN DESCRIPTION:
ROCK QUARRY BRANCH 76.0
END DESCRIPTION:
XS GIS Cut Line= 2
      2244663.72     13380876.64      2243733.16     13380675.25
#Sta/Elev= 30
  4614.8  261.61  4784.6   257.8  4866.5  257.29  4897.2  254.65  4907.4  255.62
  4927.9  253.82  4938.1  256.19  4958.6  256.67  4971.1  255.97    4997  251.22
  4999.8  250.72    5003  251.22  5009.7   252.5  5020.3  256.73  5064.4  257.77
  5108.6  256.54  5122.3  258.94  5152.7  257.13  5163.2  258.53  5201.9  255.47
    5207  259.05  5245.1  256.63  5256.2   258.2  5295.2  255.92  5300.3  258.15
  5344.4  256.27  5349.5  257.38  5367.8  255.88  5483.6  258.21  5566.9  259.99
#Mann= 4 ,-1 , 0
  4614.8      .1       0    4997     .07       0    5003      .1       0
  5483.6     .05       0
Bank Sta=4997,5003
XS Rating Curve= 0 ,0
Exp/Cntr=0.3,0.1

Type RM Length L Ch R = 1 ,40298   ,294,294,294
BEGIN DESCRIPTION:
ROCK QUARRY BRANCH 76.0
END DESCRIPTION:
XS GIS Cut Line= 2
      2244663.72     13380876.64      2243733.16     13380675.25
#Sta/Elev= 30
  4614.8  261.61  4784.6   257.8  4866.5  257.29  4897.2  254.65  4907.4  255.62
  4927.9  253.82  4938.1  256.19    4966  256.37  4996.5  251.22  4999.3  250.72
  5002.5  251.22  5009.7   252.5  5020.3  256.73  5064.4  257.77  5108.6  256.54
  5122.3  258.94  5152.7  257.13  5157.8  258.63  5163.2  258.53  5201.9  255.47
    5207  259.05  5245.1  256.63  5256.2   258.2  5295.2  255.92  5300.3  258.15
  5344.4  256.27  5349.5  257.38  5367.8  255.88  5483.6  258.21  5566.9  259.99
#Mann= 4 ,-1 , 0
  4614.8      .1       0  4996.5     .07       0  5002.5      .1       0
  5483.6     .05       0
Bank Sta=4966,5020.3
XS Rating Curve= 0 ,0
Exp/Cntr=0.3,0.1

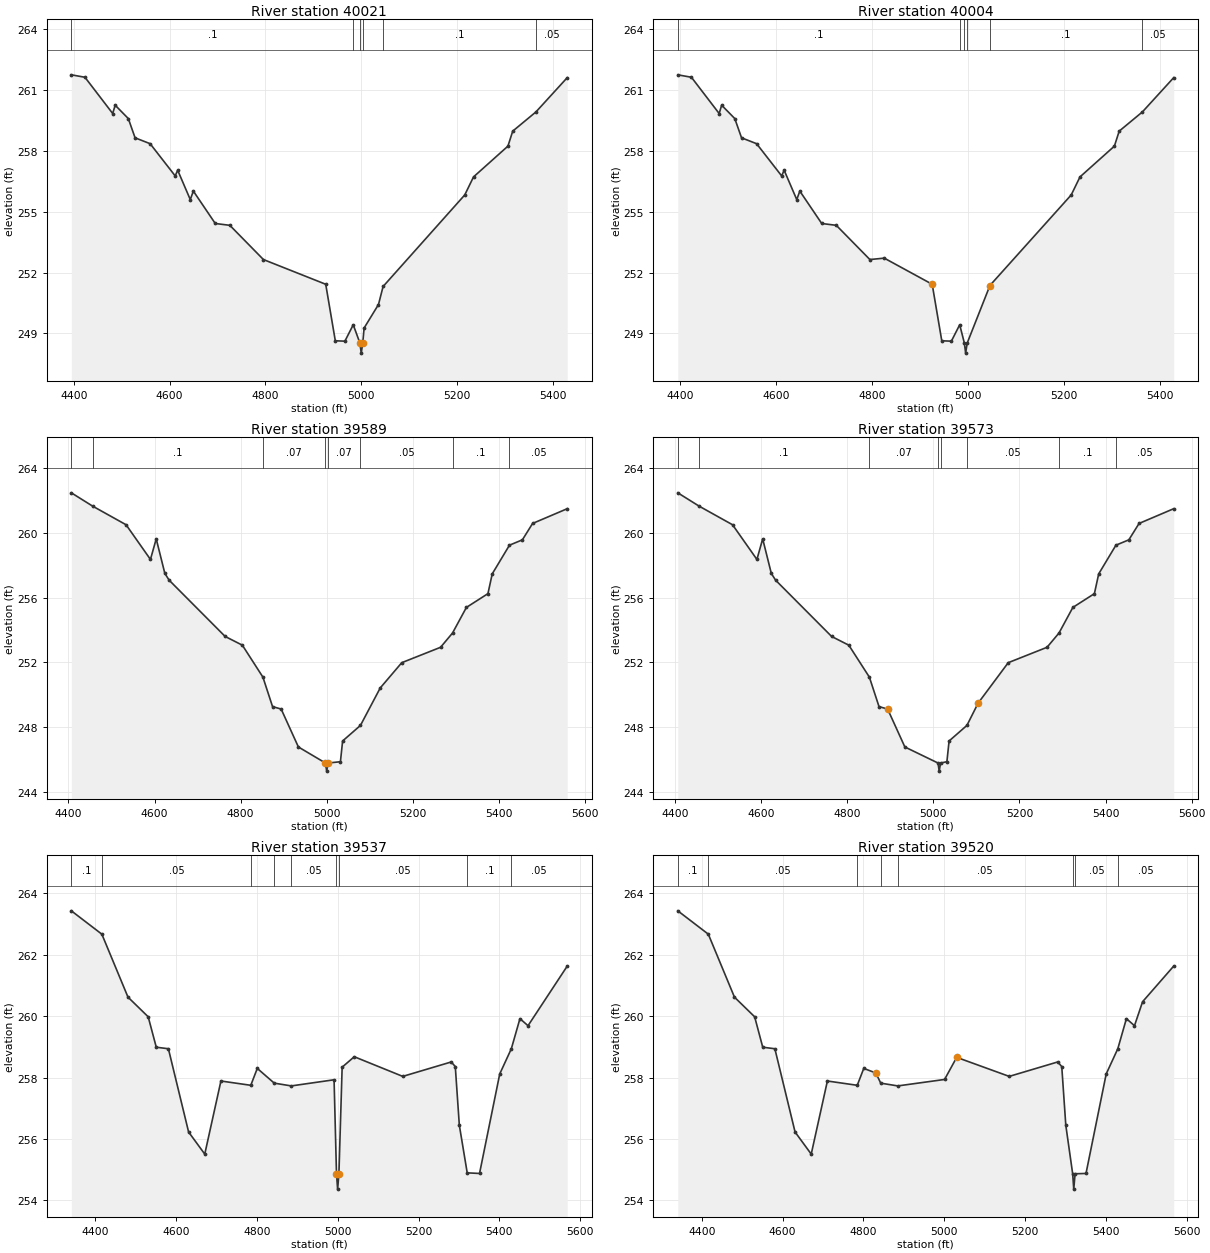
Type RM Length L Ch R = 1 ,40021   ,432,432,432
BEGIN DESCRIPTION:
Mapping XS 2a92bc2e
END DESCRIPTION:
XS GIS Cut Line= 3
       2244774.8     13380647.46      2244483.18      13380557.2
      2243754.05     13380536.36
#Sta/Elev= 30
  4394.9  261.76  4423.3  261.64  4481.2  259.85  4486.4  260.26  4513.8   259.6
  4527.9  258.65  4559.3  258.36  4611.6  256.77  4616.8  257.05  4643.1   255.6
  4649.5  256.02  4695.2  254.42  4725.6  254.33  4795.7  252.64  4925.7  251.42
  4945.7  248.63  4965.7  248.61  4983.1  249.42    4997  248.52  4999.8  248.02
    5003  248.52  5005.8  249.26  5035.8  250.42  5045.4  251.31  5215.8  255.83
  5234.1  256.72  5305.9  258.24  5315.9  258.98  5364.4  259.93  5429.6  261.62
#Mann= 6 ,-1 , 0
  4394.9      .1       0  4983.1     .05       0    4997    .035       0
    5003     .05       0  5045.4      .1       0  5364.4     .05       0
Bank Sta=4997,5003
XS Rating Curve= 0 ,0
Exp/Cntr=0.3,0.1

Type RM Length L Ch R = 1 ,40004   ,431,431,431
BEGIN DESCRIPTION:
Mapping XS 2a92bc2e
END DESCRIPTION:
XS GIS Cut Line= 3
       2244774.8     13380647.46      2244483.18      13380557.2
      2243754.05     13380536.36
#Sta/Elev= 30
  4394.9  261.76  4423.3  261.64  4481.2  259.85  4486.4  260.26  4513.8   259.6
  4527.9  258.65  4559.3  258.36  4611.6  256.77  4616.8  257.05  4643.1   255.6
  4649.5  256.02  4695.2  254.42  4725.6  254.33  4795.7  252.64  4825.7  252.71
  4925.7  251.42  4945.7  248.63  4965.7  248.61  4983.1  249.42  4992.8  248.52
  4995.5  248.02  4998.8  248.52  5045.4  251.31  5045.8  251.35  5215.8  255.83
  5234.1  256.72  5305.9  258.24  5315.9  258.98  5364.4  259.93  5429.6  261.62
#Mann= 6 ,-1 , 0
  4394.9      .1       0  4983.1     .05       0  4992.8    .035       0
  4998.8     .05       0  5045.4      .1       0  5364.4     .05       0
Bank Sta=4925.7,5045.8
XS Rating Curve= 0 ,0
Exp/Cntr=0.3,0.1

Type RM Length L Ch R = 1 ,39589   ,52,52,52
BEGIN DESCRIPTION:
ROCK QUARRY BRANCH 75.0
END DESCRIPTION:
XS GIS Cut Line= 2
      2244944.76     13380216.05      2243793.66       13380190.
#Sta/Elev= 30
  4406.9  262.46  4456.3  261.64    4534  260.49  4590.6  258.35    4604  259.62
    4624  257.49    4634  257.07    4764   253.6    4804  253.06  4851.7  251.09
  4874.1  249.27  4894.1  249.12  4934.1  246.78    4997  245.79  4999.8  245.29
    5003  245.79  5031.7  245.87  5036.8  247.15  5078.2  248.11  5124.1  250.42
  5174.1  251.98  5264.2  252.93    5292  253.81  5324.2  255.39  5374.2  256.24
  5384.2  257.46  5424.2  259.23  5454.2  259.56  5477.9  260.57  5558.3  261.48
#Mann= 8 ,-1 , 0
  4406.9     .05       0  4456.3      .1       0  4851.7     .07       0
    4997     .07       0    5003     .07       0  5078.2     .05       0
    5292      .1       0  5424.2     .05       0
Bank Sta=4997,5003
XS Rating Curve= 0 ,0
Exp/Cntr=0.3,0.1

Type RM Length L Ch R = 1 ,39573   ,53,53,53
BEGIN DESCRIPTION:
ROCK QUARRY BRANCH 75.0
END DESCRIPTION:
XS GIS Cut Line= 2
      2244944.76     13380216.05      2243793.66       13380190.
#Sta/Elev= 30
  4406.9  262.46  4456.3  261.64    4534  260.49  4590.6  258.35    4604  259.62
    4624  257.49    4634  257.07    4764   253.6    4804  253.06  4851.7  251.09
  4874.1  249.27  4894.1  249.12  4934.1  246.78  5011.1  245.79  5013.8  245.29
  5017.1  245.79  5031.7  245.87  5036.8  247.15  5078.2  248.11  5104.1  249.48
  5174.1  251.98  5264.2  252.93    5292  253.81  5324.2  255.39  5374.2  256.24
  5384.2  257.46  5424.2  259.23  5454.2  259.56  5477.9  260.57  5558.3  261.48
#Mann= 8 ,-1 , 0
  4406.9     .05       0  4456.3      .1       0  4851.7     .07       0
  5011.1     .07       0  5017.1     .07       0  5078.2     .05       0
    5292      .1       0  5424.2     .05       0
Bank Sta=4894.1,5104.1
XS Rating Curve= 0 ,0
Exp/Cntr=0.3,0.1

Type RM Length L Ch R = 1 ,39537   ,107,107,107
BEGIN DESCRIPTION:
Mapping XS 08f20c38
END DESCRIPTION:
XS GIS Cut Line= 2
      2245017.88     13380154.42       2243790.7     13380147.49
#Sta/Elev= 30
  4340.8  263.43  4416.3  262.67    4481  260.62    4531  259.98    4551  258.99
    4581  258.94    4631  256.23    4671  255.51    4711  257.89  4784.9  257.75
    4801   258.3    4843  257.82  4885.2  257.73    4991  257.93    4997  254.87
  4999.8  254.37    5003  254.87    5011  258.34    5041  258.68    5161  258.04
    5281  258.51    5291  258.36    5301  256.45  5320.5   254.9    5351  254.88
    5401  258.12  5429.7  258.94    5451  259.92    5471  259.69    5568  261.63
#Mann= 9 ,-1 , 0
  4340.8      .1       0  4416.3     .05       0  4784.9      .1       0
    4843     .07       0  4885.2     .05       0    4997    .035       0
    5003     .05       0  5320.5      .1       0  5429.7     .05       0
Bank Sta=4997,5003
XS Rating Curve= 0 ,0
Exp/Cntr=0.3,0.1

Type RM Length L Ch R = 1 ,39520   ,106,106,106
BEGIN DESCRIPTION:
Mapping XS 08f20c38
END DESCRIPTION:
XS GIS Cut Line= 2
      2245017.88     13380154.42       2243790.7     13380147.49
#Sta/Elev= 30
  4340.8  263.43  4416.3  262.67    4481  260.62    4531  259.98    4551  258.99
    4581  258.94    4631  256.23    4671  255.51    4711  257.89  4784.9  257.75
    4801   258.3    4831  258.15    4843  257.82  4885.2  257.73    5001  257.94
    5031  258.66    5161  258.04    5281  258.51    5291  258.36    5301  256.45
    5318  254.87  5320.7  254.37    5324  254.87    5351  254.88    5401  258.12
  5429.7  258.94    5451  259.92    5471  259.69    5491  260.47    5568  261.63
#Mann= 8 ,-1 , 0
  4340.8      .1       0  4416.3     .05       0  4784.9      .1       0
    4843     .07       0  4885.2     .05       0    5318    .035       0
    5324     .05       0  5429.7     .05       0
Bank Sta=4831,5031
XS Rating Curve= 0 ,0
Exp/Cntr=0.3,0.1

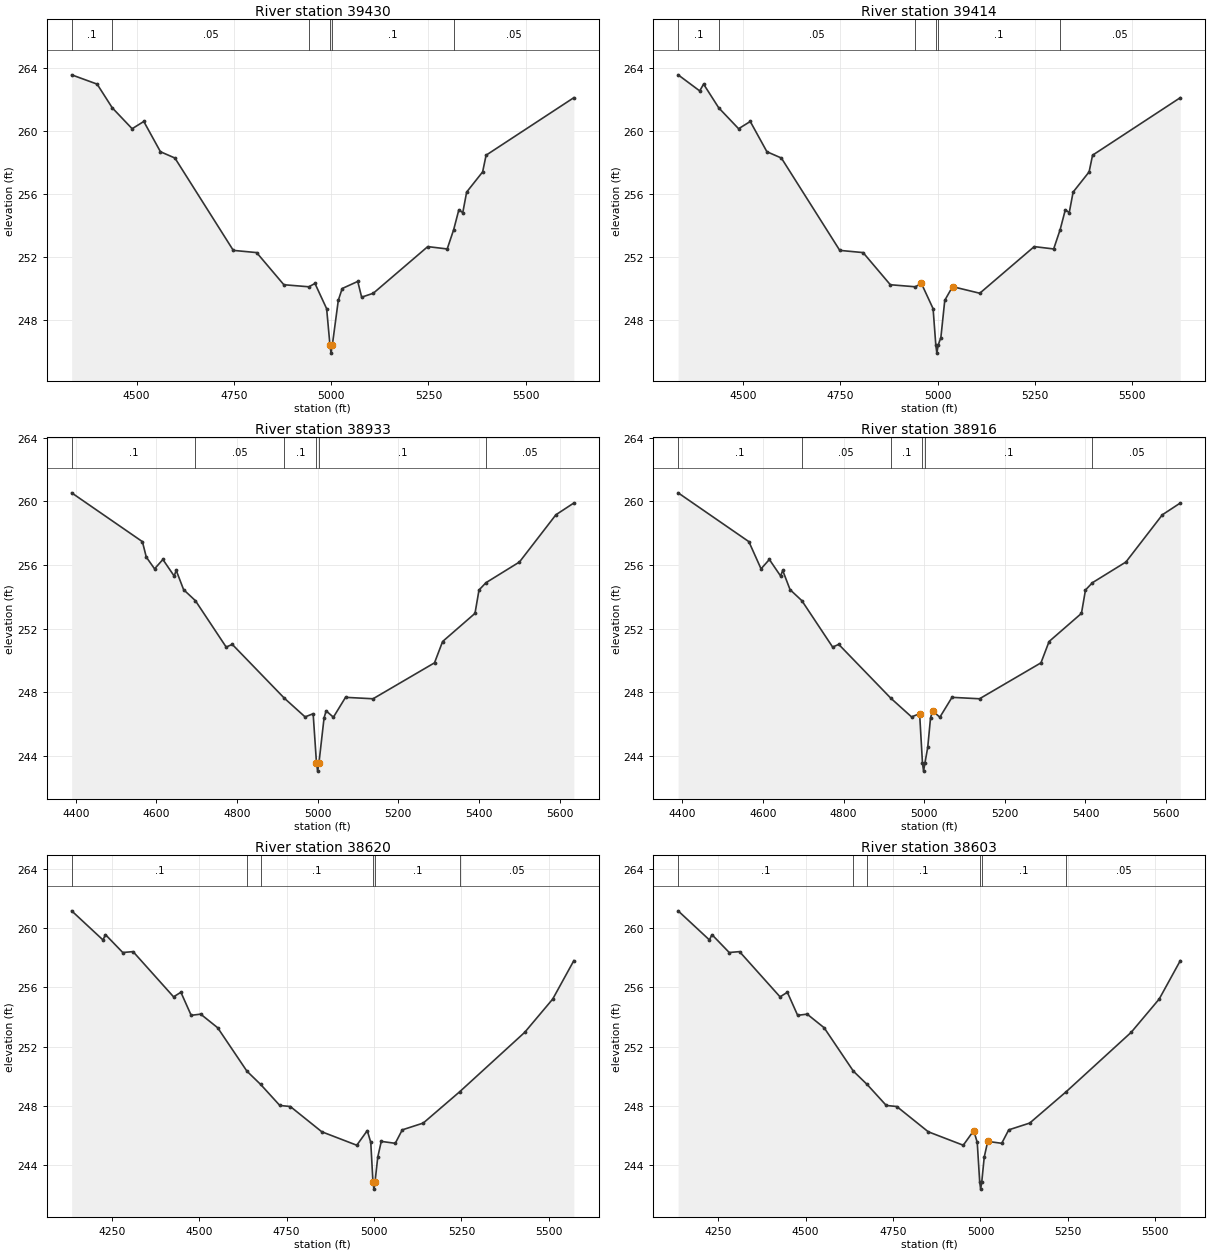
Type RM Length L Ch R = 1 ,39430   ,497,497,497
BEGIN DESCRIPTION:
ROCK QUARRY BRANCH 74.0
END DESCRIPTION:
XS GIS Cut Line= 2
      2245033.24     13380054.59      2243742.14     13380038.97
#Sta/Elev= 30
  4332.8  263.57  4398.3  262.98  4437.1  261.48  4488.3  260.15  4518.3  260.61
  4561.1  258.69  4598.3  258.29  4748.4  252.43  4808.4  252.29  4878.4  250.25
  4942.6  250.12  4958.4  250.33  4988.4  248.73    4997  246.41  4999.8  245.91
    5003  246.41  5018.4  249.26  5028.4  250.01  5068.4  250.46  5078.4  249.46
  5108.4  249.71  5248.4  252.67  5298.4  252.52  5315.1  253.75  5328.4  255.01
  5338.4  254.82  5348.4  256.13  5389.5  257.41  5398.4  258.47    5624  262.12
#Mann= 6 ,-1 , 0
  4332.8      .1       0  4437.1     .05       0  4942.6      .1       0
    4997     .07       0    5003      .1       0  5315.1     .05       0
Bank Sta=4997,5003
XS Rating Curve= 0 ,0
Exp/Cntr=0.3,0.1

Type RM Length L Ch R = 1 ,39414   ,498,498,498
BEGIN DESCRIPTION:
ROCK QUARRY BRANCH 74.0
END DESCRIPTION:
XS GIS Cut Line= 2
      2245033.24     13380054.59      2243742.14     13380038.97
#Sta/Elev= 30
  4332.8  263.57  4388.3  262.55  4398.3  262.98  4437.1  261.48  4488.3  260.15
  4518.3  260.61  4561.1  258.69  4598.3  258.29  4748.4  252.43  4808.4  252.29
  4878.4  250.25  4942.6  250.12  4958.4  250.33  4988.4  248.73  4995.4  246.41
  4998.1  245.91  5001.4  246.41  5008.4   246.9  5018.4  249.26  5038.4  250.13
  5108.4  249.71  5248.4  252.67  5298.4  252.52  5315.1  253.75  5328.4  255.01
  5338.4  254.82  5348.4  256.13  5389.5  257.41  5398.4  258.47    5624  262.12
#Mann= 6 ,-1 , 0
  4332.8      .1       0  4437.1     .05       0  4942.6      .1       0
  4995.4     .07       0  5001.4      .1       0  5315.1     .05       0
Bank Sta=4958.4,5038.4
XS Rating Curve= 0 ,0
Exp/Cntr=0.3,0.1

Type RM Length L Ch R = 1 ,38933   ,313,313,313
BEGIN DESCRIPTION:
ROCK QUARRY BRANCH 73.0
END DESCRIPTION:
XS GIS Cut Line= 3
      2245017.69     13379611.89      2244736.41     13379544.17
      2243783.32     13379622.29
#Sta/Elev= 30
  4389.7  260.54  4565.2  257.47  4574.8   256.5  4595.4  255.76    4616  256.35
  4643.9  255.31  4649.1  255.66  4667.4  254.45  4696.6  253.76    4773  250.84
  4788.1  251.01  4917.1  247.63  4968.7  246.45  4988.7  246.65    4997  243.54
  4999.8  243.04    5003  243.54  5015.8  246.39  5020.9  246.83  5038.9  246.43
    5069  247.68  5137.3  247.59  5289.7  249.85  5309.8  251.19  5390.1  252.96
  5400.1  254.43  5417.4  254.89  5500.4  256.19  5590.8  259.16  5635.3   259.9
#Mann= 6 ,-1 , 0
  4389.7      .1       0  4696.6     .05       0  4917.1      .1       0
    4997     .07       0    5003      .1       0  5417.4     .05       0
Bank Sta=4997,5003
XS Rating Curve= 0 ,0
Exp/Cntr=0.3,0.1

Type RM Length L Ch R = 1 ,38916   ,313,313,313
BEGIN DESCRIPTION:
ROCK QUARRY BRANCH 73.0
END DESCRIPTION:
XS GIS Cut Line= 3
      2245017.69     13379611.89      2244736.41     13379544.17
      2243783.32     13379622.29
#Sta/Elev= 30
  4389.7  260.54  4565.2  257.47  4595.4  255.76    4616  256.35  4643.9  255.31
  4649.1  255.66  4667.4  254.45  4696.6  253.76    4773  250.84  4788.1  251.01
  4917.1  247.63  4968.7  246.45  4988.7  246.65  4995.8  243.54  4998.5  243.04
  5001.8  243.54  5008.8  244.53  5015.8  246.39  5020.9  246.83  5038.9  246.43
    5069  247.68  5137.3  247.59  5289.7  249.85  5309.8  251.19  5390.1  252.96
  5400.1  254.43  5417.4  254.89  5500.4  256.19  5590.8  259.16  5635.3   259.9
#Mann= 6 ,-1 , 0
  4389.7      .1       0  4696.6     .05       0  4917.1      .1       0
  4995.8     .07       0  5001.8      .1       0  5417.4     .05       0
Bank Sta=4988.7,5020.9
XS Rating Curve= 0 ,0
Exp/Cntr=0.3,0.1

Type RM Length L Ch R = 1 ,38620   ,453,453,453
BEGIN DESCRIPTION:
ROCK QUARRY BRANCH 72.0
END DESCRIPTION:
XS GIS Cut Line= 3
      2245116.63     13379512.93      2244778.08     13379273.34
      2243757.29     13379283.76
#Sta/Elev= 30
  4135.7  261.18  4225.2  259.21  4232.4  259.57  4281.8  258.36  4311.3  258.42
  4427.1  255.36    4448  255.67  4477.4  254.11  4504.6  254.19  4553.1  253.27
  4636.8  250.33  4676.1  249.43  4730.8  248.01  4760.8  247.94  4850.8  246.23
  4950.8  245.32  4980.8  246.31  4990.8  245.51    4997  242.85  4999.8  242.35
    5003  242.85  5010.8  244.52  5020.8  245.58  5060.8  245.45  5080.8  246.36
  5140.8  246.82  5245.5  248.95  5430.9  252.96  5510.9  255.21  5571.3  257.81
#Mann= 6 ,-1 , 0
  4135.7      .1       0  4636.8     .05       0  4676.1      .1       0
    4997     .07       0    5003      .1       0  5245.5     .05       0
Bank Sta=4997,5003
XS Rating Curve= 0 ,0
Exp/Cntr=0.3,0.1

Type RM Length L Ch R = 1 ,38603   ,452,452,452
BEGIN DESCRIPTION:
ROCK QUARRY BRANCH 72.0
END DESCRIPTION:
XS GIS Cut Line= 3
      2245116.63     13379512.93      2244778.08     13379273.34
      2243757.29     13379283.76
#Sta/Elev= 30
  4135.7  261.18  4225.2  259.21  4232.4  259.57  4281.8  258.36  4311.3  258.42
  4427.1  255.36    4448  255.67  4477.4  254.11  4504.6  254.19  4553.1  253.27
  4636.8  250.33  4676.1  249.43  4730.8  248.01  4760.8  247.94  4850.8  246.23
  4950.8  245.32  4980.8  246.31  4990.8  245.51  4997.8  242.85  5000.6  242.35
  5003.8  242.85  5010.8  244.52  5020.8  245.58  5060.8  245.45  5080.8  246.36
  5140.8  246.82  5245.5  248.95  5430.9  252.96  5510.9  255.21  5571.3  257.81
#Mann= 6 ,-1 , 0
  4135.7      .1       0  4636.8     .05       0  4676.1      .1       0
  4997.8     .07       0  5003.8      .1       0  5245.5     .05       0
Bank Sta=4980.8,5020.8
XS Rating Curve= 0 ,0
Exp/Cntr=0.3,0.1