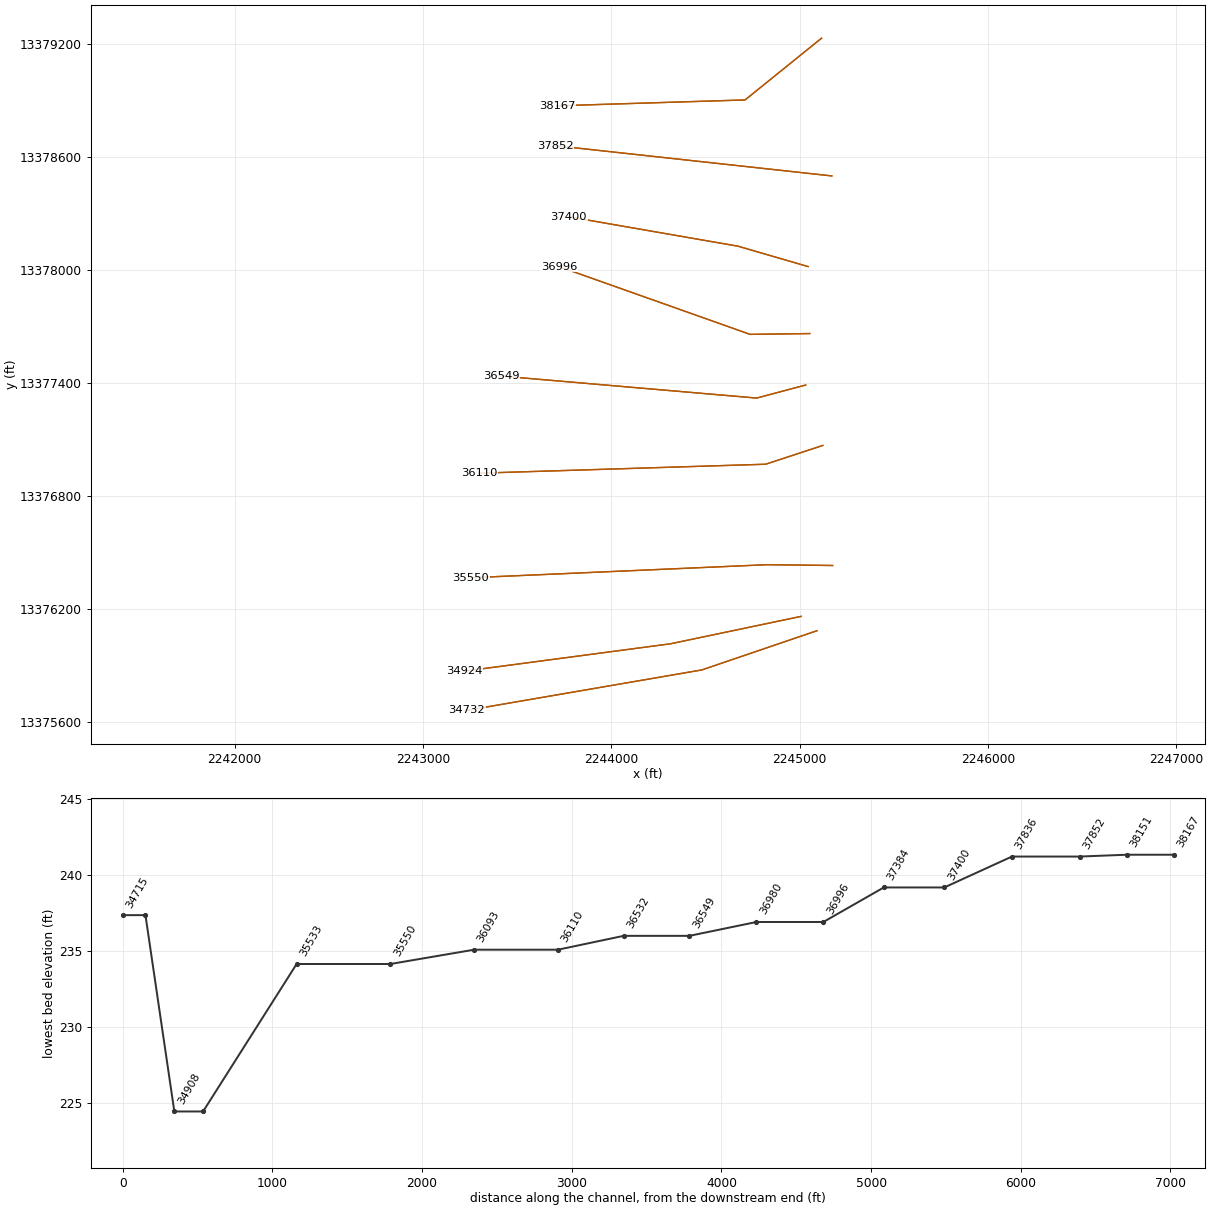
HEC-RAS study ROCK QUARRY BRANCH.prj: ROCK QUARRY BRANCH Base Level Engineering

--- ROCK QUARRY BRANCH.g01 (geometry) --- (continued)

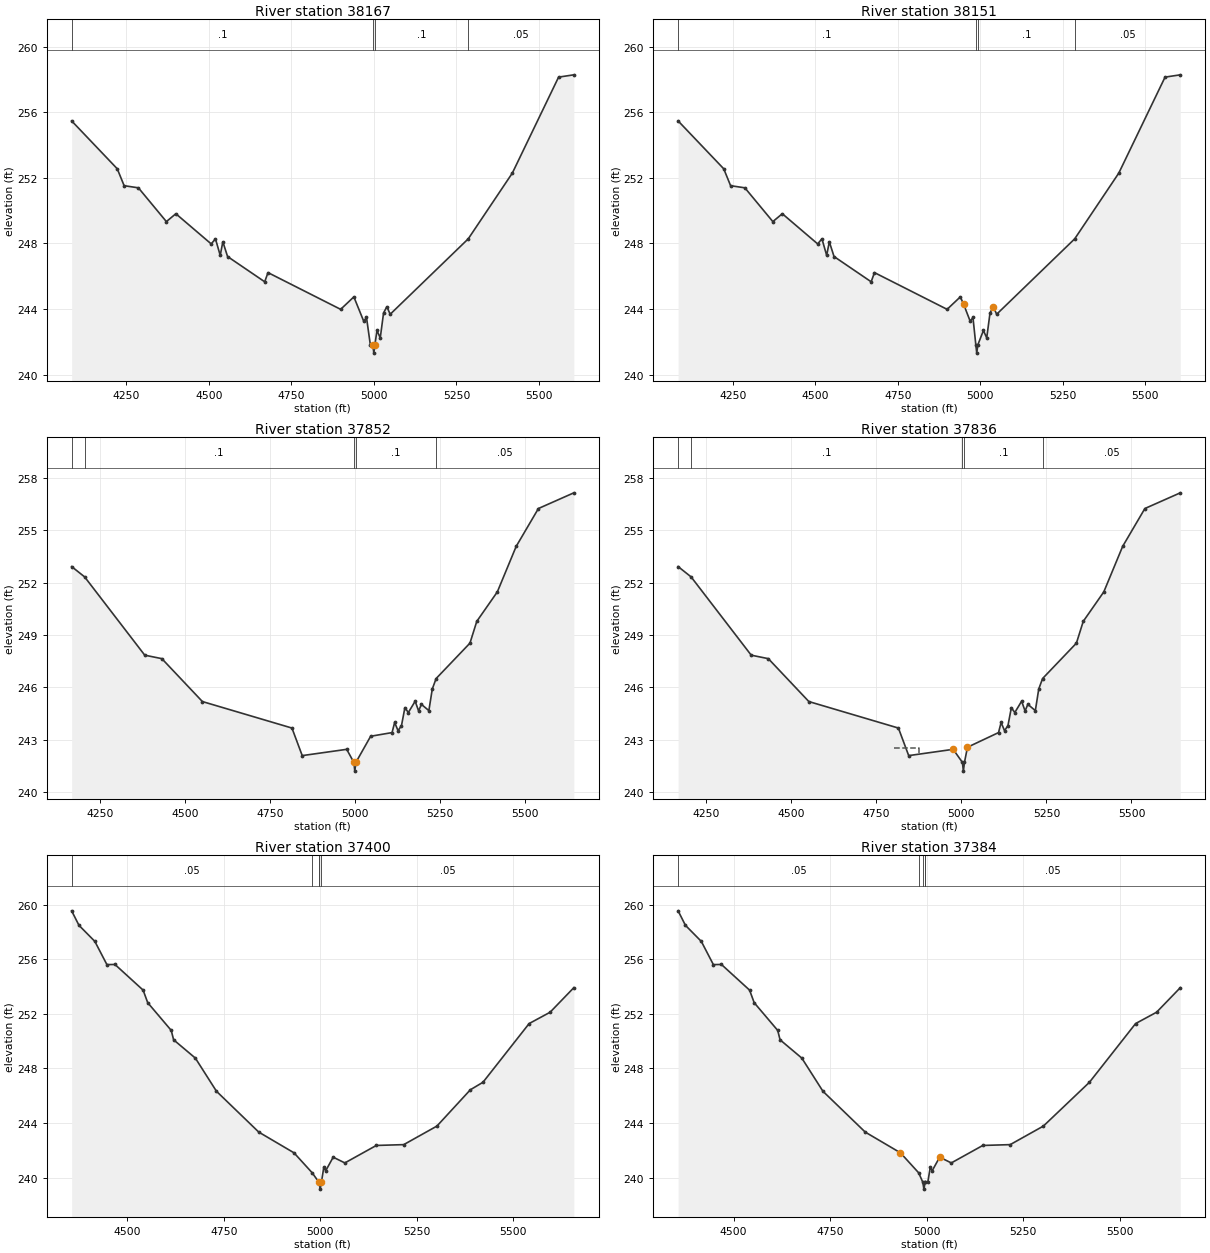
Type RM Length L Ch R = 1 ,38167   ,315,315,315
BEGIN DESCRIPTION:
ROCK QUARRY BRANCH 71.0
END DESCRIPTION:
XS GIS Cut Line= 3
       2245116.6     13379231.66      2244710.37     13378903.55
      2243711.54     13378872.33
#Sta/Elev= 30
  4084.3  255.47  4222.5  252.55  4243.3  251.52  4286.5  251.39  4371.3  249.33
    4400  249.81  4507.1  247.97    4520  248.28  4534.4  247.27  4542.4   248.1
  4556.7   247.2  4669.2  245.66  4679.2  246.22  4899.3  243.98  4939.3  244.74
  4969.3  243.25  4977.6  243.49  4989.3  241.81    4997  241.81  4999.8  241.31
    5003  241.81  5009.3  242.69  5019.3  242.24  5029.3  243.76  5039.3  244.14
  5049.4  243.68  5285.9  248.28  5419.5  252.29  5559.6  258.14  5605.8  258.28
#Mann= 4 ,-1 , 0
  4084.3      .1       0    4997     .07       0    5003      .1       0
  5285.9     .05       0
Bank Sta=4997,5003
XS Rating Curve= 0 ,0
Exp/Cntr=0.3,0.1

Type RM Length L Ch R = 1 ,38151   ,315,315,315
BEGIN DESCRIPTION:
ROCK QUARRY BRANCH 71.0
END DESCRIPTION:
XS GIS Cut Line= 3
       2245116.6     13379231.66      2244710.37     13378903.55
      2243711.54     13378872.33
#Sta/Elev= 30
  4084.3  255.47  4222.5  252.55  4243.3  251.52  4286.5  251.39  4371.3  249.33
    4400  249.81  4507.1  247.97    4520  248.28  4534.4  247.27  4542.4   248.1
  4556.7   247.2  4669.2  245.66  4679.2  246.22  4899.3  243.98  4939.3  244.74
  4949.3  244.29  4969.3  243.25  4977.6  243.49  4986.3  241.81  4989.1  241.31
  4992.3  241.81  5009.3  242.69  5019.3  242.24  5029.3  243.76  5039.3  244.14
  5049.4  243.68  5285.9  248.28  5419.5  252.29  5559.6  258.14  5605.8  258.28
#Mann= 4 ,-1 , 0
  4084.3      .1       0  4986.3     .07       0  4992.3      .1       0
  5285.9     .05       0
Bank Sta=4949.3,5039.3
XS Rating Curve= 0 ,0
Exp/Cntr=0.3,0.1

Type RM Length L Ch R = 1 ,37852   ,452,452,452
BEGIN DESCRIPTION:
Mapping XS 973083d7
END DESCRIPTION:
XS GIS Cut Line= 2
      2245171.25     13378499.68      2243704.21     13378660.27
#Sta/Elev= 30
  4167.7  252.92  4205.8  252.33  4382.5  247.84  4432.8  247.64  4551.9  245.18
  4815.1  243.66  4845.3  242.08    4976  242.44    4997  241.69  4999.8  241.19
    5003  241.69  5046.4  243.19  5109.3   243.4  5116.9  243.98  5126.9  243.51
    5137   243.8    5147  244.83  5157.1  244.55  5177.2   245.2  5187.3  244.64
  5195.5  245.02  5217.5  244.66  5227.5   245.9  5238.8   246.5  5338.2  248.53
  5358.3  249.78  5418.7  251.47  5474.1  254.08  5539.4  256.25  5643.5  257.15
#Mann= 5 ,-1 , 0
  4167.7     .05       0  4205.8      .1       0    4997     .07       0
    5003      .1       0  5238.8     .05       0
Bank Sta=4997,5003
XS Rating Curve= 0 ,0
Exp/Cntr=0.3,0.1

Type RM Length L Ch R = 1 ,37836   ,452,452,452
BEGIN DESCRIPTION:
Mapping XS 973083d7
END DESCRIPTION:
XS GIS Cut Line= 2
      2245171.25     13378499.68      2243704.21     13378660.27
#Sta/Elev= 30
  4167.7  252.92  4205.8  252.33  4382.5  247.84  4432.8  247.64  4551.9  245.18
  4815.1  243.66  4845.3  242.08    4976  242.44  5003.2  241.69    5006  241.19
  5009.2  241.69    5018  242.56  5109.3   243.4  5116.9  243.98  5126.9  243.51
    5137   243.8    5147  244.83  5157.1  244.55  5177.2   245.2  5187.3  244.64
  5195.5  245.02  5217.5  244.66  5227.5   245.9  5238.8   246.5  5338.2  248.53
  5358.3  249.78  5418.7  251.47  5474.1  254.08  5539.4  256.25  5643.5  257.15
#Mann= 5 ,-1 , 0
  4167.7     .05       0  4205.8      .1       0  5003.2     .07       0
  5009.2      .1       0  5238.8     .05       0
#XS Ineff= 1 ,-1
 4801.82 4875.45  242.52
Permanent Ineff=
       F
Bank Sta=4976,5018
XS Rating Curve= 0 ,0
Exp/Cntr=0.3,0.1

Type RM Length L Ch R = 1 ,37400   ,404,404,404
BEGIN DESCRIPTION:
ROCK QUARRY BRANCH 70.0
END DESCRIPTION:
XS GIS Cut Line= 3
      2245045.42      13378017.9      2244672.12     13378126.41
      2243773.66     13378282.67
#Sta/Elev= 30
  4356.1  259.55    4375  258.49  4416.2  257.31  4447.4  255.61  4468.3  255.62
  4541.2  253.74  4553.1  252.82    4614  250.79  4620.2   250.1  4676.5  248.76
  4731.2  246.33  4840.7  243.34    4932  241.82  4979.3  240.35  4996.6  239.66
    4997  239.66  4999.8  239.16    5003  239.66  5009.1  240.75  5014.2  240.51
  5033.5   241.5  5063.7  241.08  5145.2  242.36  5216.2  242.42  5302.2  243.78
  5388.8  246.44  5421.5  246.99    5541  251.29  5595.3  252.12  5656.8  253.92
#Mann= 5 ,-1 , 0
  4356.1     .05       0  4979.3      .1       0  4996.6     .05       0
    4997     .03       0    5003     .05       0
Bank Sta=4997,5003
XS Rating Curve= 0 ,0
Exp/Cntr=0.3,0.1

Type RM Length L Ch R = 1 ,37384   ,404,404,404
BEGIN DESCRIPTION:
ROCK QUARRY BRANCH 70.0
END DESCRIPTION:
XS GIS Cut Line= 3
      2245045.42      13378017.9      2244672.12     13378126.41
      2243773.66     13378282.67
#Sta/Elev= 30
  4356.1  259.55    4375  258.49  4416.2  257.31  4447.4  255.61  4468.3  255.62
  4541.2  253.74  4553.1  252.82    4614  250.79  4620.2   250.1  4676.5  248.76
  4731.2  246.33  4840.7  243.34    4932  241.82  4979.3  240.35  4989.9  239.66
  4992.7  239.16  4995.9  239.66  4996.6  239.66  5003.1  239.71  5009.1  240.75
  5014.2  240.51  5033.5   241.5  5063.7  241.08  5145.2  242.36  5216.2  242.42
  5302.2  243.78  5421.5  246.99    5541  251.29  5595.3  252.12  5656.8  253.92
#Mann= 5 ,-1 , 0
  4356.1     .05       0  4979.3      .1       0  4989.9     .03       0
  4995.9      .1       0  4996.6     .05       0
Bank Sta=4932,5033.5
XS Rating Curve= 0 ,0
Exp/Cntr=0.3,0.1

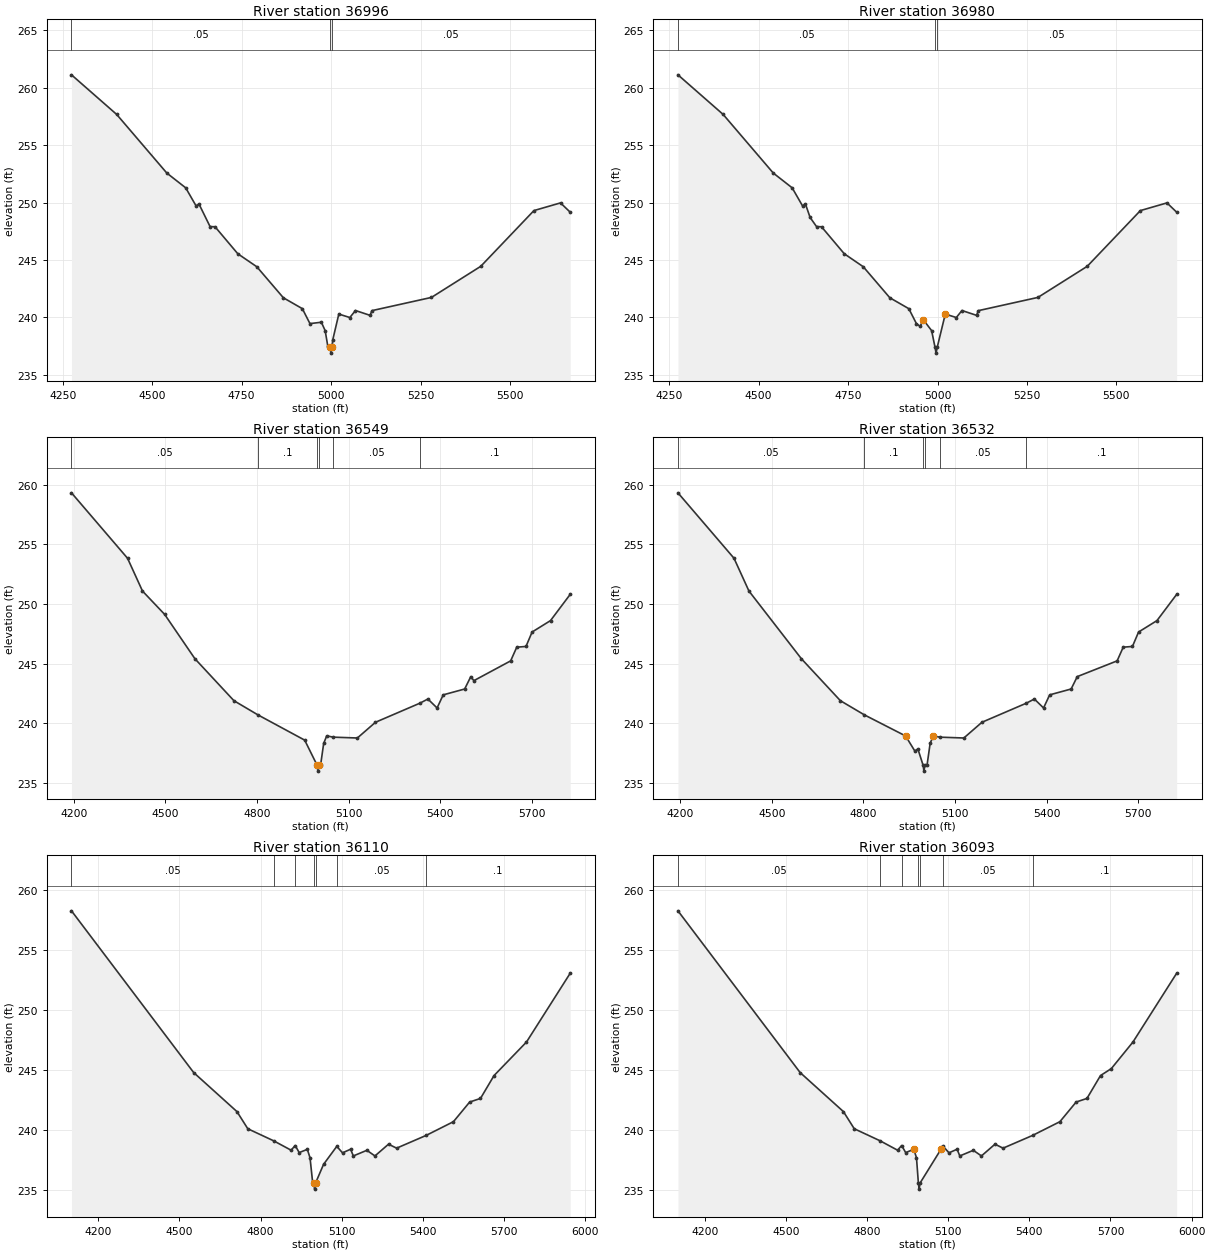
Type RM Length L Ch R = 1 ,36996   ,447,447,447
BEGIN DESCRIPTION:
ROCK QUARRY BRANCH 69.0
END DESCRIPTION:
XS GIS Cut Line= 3
       2245054.1       13377662.      2244737.23     13377657.66
      2243722.19      13378017.7
#Sta/Elev= 30
  4274.5  261.12  4400.9  257.67  4540.9  252.57  4593.8  251.28  4622.7  249.71
  4630.9  249.87  4661.8  247.91  4675.8  247.89  4739.4  245.54  4792.5  244.41
  4866.7  241.71  4919.8  240.76    4941  239.46  4972.9  239.58  4983.5  238.85
  4990.8  237.52    4997  237.39  4999.8  236.89    5003  237.39  5004.7  238.04
  5021.7  240.29  5052.5  239.99  5068.3   240.6    5109  240.18  5114.3  240.59
  5280.6  241.74  5418.5  244.45    5567   249.3  5641.3  249.97  5668.4  249.16
#Mann= 3 ,-1 , 0
  4274.5     .05       0    4997     .03       0    5003     .05       0
Bank Sta=4997,5003
XS Rating Curve= 0 ,0
Exp/Cntr=0.3,0.1

Type RM Length L Ch R = 1 ,36980   ,448,448,448
BEGIN DESCRIPTION:
ROCK QUARRY BRANCH 69.0
END DESCRIPTION:
XS GIS Cut Line= 3
       2245054.1       13377662.      2244737.23     13377657.66
      2243722.19      13378017.7
#Sta/Elev= 30
  4274.5  261.12  4400.9  257.67  4540.9  252.57  4593.8  251.28  4622.7  249.71
  4630.9  249.87  4643.9   248.7  4661.8  247.91  4675.8  247.89  4739.4  245.54
  4792.5  244.41  4866.7  241.71  4919.8  240.76    4941  239.46  4951.6  239.22
  4959.9  239.81  4983.5  238.85  4993.1  237.39  4995.9  236.89  4999.1  237.39
  5021.7  240.29  5052.5  239.99  5068.3   240.6    5109  240.18  5114.3  240.59
  5280.6  241.74  5418.5  244.45    5567   249.3  5641.3  249.97  5668.4  249.16
#Mann= 3 ,-1 , 0
  4274.5     .05       0  4993.1     .03       0  4999.1     .05       0
Bank Sta=4959.9,5021.7
XS Rating Curve= 0 ,0
Exp/Cntr=0.3,0.1

Type RM Length L Ch R = 1 ,36549   ,439,439,439
BEGIN DESCRIPTION:
ROCK QUARRY BRANCH 68.0
END DESCRIPTION:
XS GIS Cut Line= 3
      2245032.37     13377388.57      2244771.95     13377319.12
      2243413.42     13377436.31
#Sta/Elev= 30
  4192.8  259.33  4376.4  253.84  4425.3  251.09  4497.9  249.13    4597  245.41
  4724.7  241.89  4803.3   240.7  4956.5  238.58    4997  236.48  4999.8  235.98
    5003  236.48  5008.6   236.5  5018.6   238.3  5028.6  238.94  5050.1  238.83
    5129  238.76  5188.3  240.08  5333.6  241.68  5359.9  242.03    5390  241.28
  5410.1  242.38  5480.3  242.87  5500.4  243.91  5510.4  243.57  5630.9  245.23
  5650.9  246.38  5681.1  246.44  5701.1  247.65  5761.4  248.61  5825.9  250.81
#Mann= 6 ,-1 , 0
  4192.8     .05       0  4803.3      .1       0    4997     .07       0
    5003      .1       0  5050.1     .05       0  5333.6      .1       0
Bank Sta=4997,5003
XS Rating Curve= 0 ,0
Exp/Cntr=0.3,0.1

Type RM Length L Ch R = 1 ,36532   ,439,439,439
BEGIN DESCRIPTION:
ROCK QUARRY BRANCH 68.0
END DESCRIPTION:
XS GIS Cut Line= 3
      2245032.37     13377388.57      2244771.95     13377319.12
      2243413.42     13377436.31
#Sta/Elev= 30
  4192.8  259.33  4376.4  253.84  4425.3  251.09    4597  245.41  4724.7  241.89
  4803.3   240.7  4938.3  238.93  4968.4  237.67  4978.5  237.84  4995.5  236.48
  4998.3  235.98  5001.5  236.48  5008.6   236.5  5018.6   238.3  5028.6  238.94
  5050.1  238.83    5129  238.76  5188.3  240.08  5333.6  241.68  5359.9  242.03
    5390  241.28  5410.1  242.38  5480.3  242.87  5500.4  243.91  5630.9  245.23
  5650.9  246.38  5681.1  246.44  5701.1  247.65  5761.4  248.61  5825.9  250.81
#Mann= 6 ,-1 , 0
  4192.8     .05       0  4803.3      .1       0  4995.5     .07       0
  5001.5      .1       0  5050.1     .05       0  5333.6      .1       0
Bank Sta=4938.3,5028.6
XS Rating Curve= 0 ,0
Exp/Cntr=0.3,0.1

Type RM Length L Ch R = 1 ,36110   ,560,560,560
BEGIN DESCRIPTION:
ROCK QUARRY BRANCH 67.0
END DESCRIPTION:
XS GIS Cut Line= 3
       2245123.5     13377067.38      2244819.69     13376967.56
      2243296.22     13376919.81
#Sta/Elev= 30
  4100.7   258.3  4552.5   244.8  4712.6  241.54  4752.6  240.11  4848.5   239.1
  4912.7  238.32  4927.9  238.71  4942.7  238.12  4972.7  238.39  4982.7  237.69
  4992.7  235.57    4997  235.57  4999.8  235.07    5003  235.57  5032.8  237.14
  5081.7  238.64  5102.8   238.1  5132.8   238.4  5142.8  237.84  5192.8  238.31
  5222.8  237.84  5272.9  238.82  5302.9  238.49  5411.7  239.55    5513   240.7
    5573  242.34    5613  242.64  5663.1  244.55  5783.1  247.35  5944.7  253.09
#Mann= 7 ,-1 , 0
  4100.7     .05       0  4848.5      .1       0  4927.9     .07       0
    4997     .07       0    5003     .07       0  5081.7     .05       0
  5411.7      .1       0
Bank Sta=4997,5003
XS Rating Curve= 0 ,0
Exp/Cntr=0.3,0.1

Type RM Length L Ch R = 1 ,36093   ,560,560,560
BEGIN DESCRIPTION:
ROCK QUARRY BRANCH 67.0
END DESCRIPTION:
XS GIS Cut Line= 3
       2245123.5     13377067.38      2244819.69     13376967.56
      2243296.22     13376919.81
#Sta/Elev= 30
  4100.7   258.3  4552.5   244.8  4712.6  241.54  4752.6  240.11  4848.5   239.1
  4912.7  238.32  4927.9  238.71  4942.7  238.12  4972.7  238.39  4982.7  237.69
  4989.7  235.57  4992.5  235.07  4995.7  235.57  5072.8  238.38  5081.7  238.64
  5102.8   238.1  5132.8   238.4  5142.8  237.84  5192.8  238.31  5222.8  237.84
  5272.9  238.82  5302.9  238.49  5411.7  239.55    5513   240.7    5573  242.34
    5613  242.64  5663.1  244.55  5703.1  245.13  5783.1  247.35  5944.7  253.09
#Mann= 7 ,-1 , 0
  4100.7     .05       0  4848.5      .1       0  4927.9     .07       0
  4989.7     .07       0  4995.7     .07       0  5081.7     .05       0
  5411.7      .1       0
Bank Sta=4972.7,5072.8
XS Rating Curve= 0 ,0
Exp/Cntr=0.3,0.1

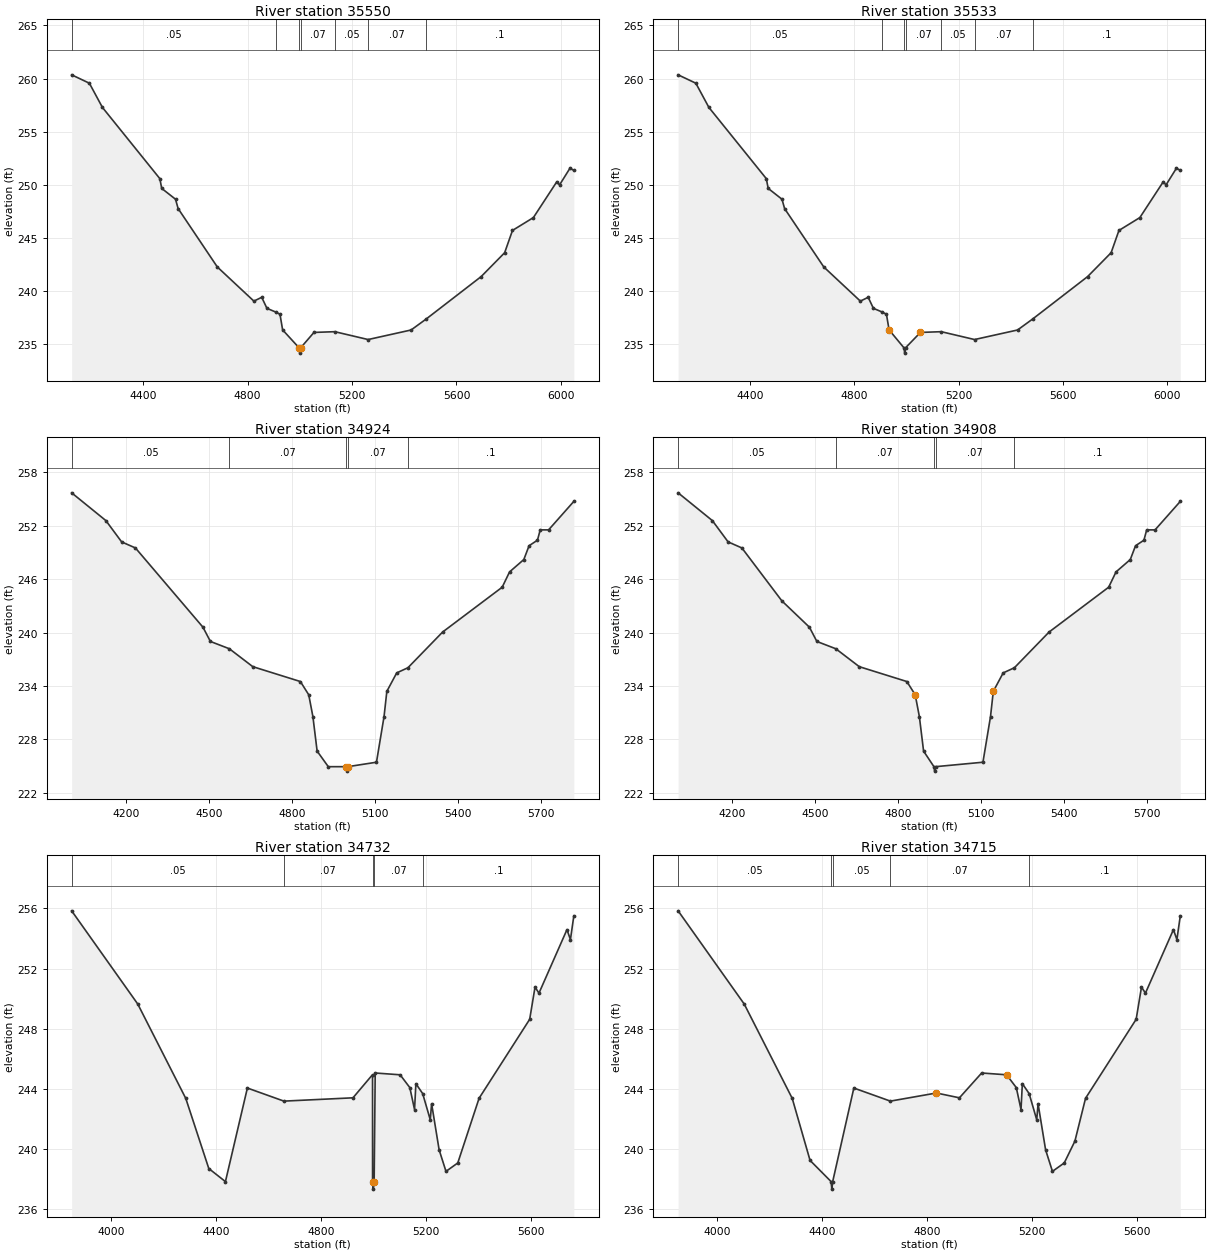
Type RM Length L Ch R = 1 ,35550   ,626,626,626
BEGIN DESCRIPTION:
ROCK QUARRY BRANCH 66.0
END DESCRIPTION:
XS GIS Cut Line= 3
       2245175.6     13376429.36      2244828.37      13376433.7
      2243252.86     13376364.26
#Sta/Elev= 30
  4125.5  260.35  4193.4  259.56  4243.4  257.28  4463.4  250.57  4470.6  249.65
  4523.5  248.63  4533.5  247.75  4683.6  242.25  4823.8  239.03  4853.8  239.39
  4873.8  238.35  4908.6  237.99  4923.8  237.79  4933.9  236.32    4997  234.63
  4999.8  234.13    5003  234.63    5054  236.08  5133.8  236.15  5261.5  235.41
  5426.2  236.31  5483.8  237.34  5694.6  241.34  5784.7  243.59  5814.7  245.69
  5894.8   246.9  5984.9  250.29  5994.9  249.97  6034.9  251.55  6049.8  251.35
#Mann= 7 ,-1 , 0
  4125.5     .05       0  4908.6     .07       0    4997     .07       0
    5003     .07       0  5133.8     .05       0  5261.5     .07       0
  5483.8      .1       0
Bank Sta=4997,5003
XS Rating Curve= 0 ,0
Exp/Cntr=0.3,0.1

Type RM Length L Ch R = 1 ,35533   ,625,625,625
BEGIN DESCRIPTION:
ROCK QUARRY BRANCH 66.0
END DESCRIPTION:
XS GIS Cut Line= 3
       2245175.6     13376429.36      2244828.37      13376433.7
      2243252.86     13376364.26
#Sta/Elev= 30
  4125.5  260.35  4193.4  259.56  4243.4  257.28  4463.4  250.57  4470.6  249.65
  4523.5  248.63  4533.5  247.75  4683.6  242.25  4823.8  239.03  4853.8  239.39
  4873.8  238.35  4908.6  237.99  4923.8  237.79  4933.9  236.32  4990.9  234.63
  4993.7  234.13  4996.9  234.63    5054  236.08  5133.8  236.15  5261.5  235.41
  5426.2  236.31  5483.8  237.34  5694.6  241.34  5784.7  243.59  5814.7  245.69
  5894.8   246.9  5984.9  250.29  5994.9  249.97  6034.9  251.55  6049.8  251.35
#Mann= 7 ,-1 , 0
  4125.5     .05       0  4908.6     .07       0  4990.9     .07       0
  4996.9     .07       0  5133.8     .05       0  5261.5     .07       0
  5483.8      .1       0
Bank Sta=4933.9,5054
XS Rating Curve= 0 ,0
Exp/Cntr=0.3,0.1

Type RM Length L Ch R = 1 ,34924   ,192,192,192
BEGIN DESCRIPTION:
ROCK QUARRY BRANCH 65.0
END DESCRIPTION:
XS GIS Cut Line= 3
      2245008.93     13376159.17      2244314.49     13376013.34
      2243217.22      13375867.5
#Sta/Elev= 30
  4003.9  255.69  4127.8  252.57  4184.7  250.18  4234.6   249.5  4478.9   240.6
  4505.8     239  4574.4  238.18  4659.1  236.17  4831.3   234.5  4861.5  233.01
  4876.6  230.55  4891.8  226.69  4932.2  224.94    4997  224.94  4999.8  224.44
    5003  224.94  5106.5  225.44  5133.9  230.57    5144   233.4  5179.7  235.47
  5220.3  236.05  5345.8  240.06  5561.2  245.09  5587.9  246.81  5639.5   248.2
  5658.5  249.75  5688.8  250.37  5698.8  251.53  5729.1  251.53  5820.4  254.73
#Mann= 5 ,-1 , 0
  4003.9     .05       0  4574.4     .07       0    4997     .07       0
    5003     .07       0  5220.3      .1       0
Bank Sta=4997,5003
XS Rating Curve= 0 ,0
Exp/Cntr=0.3,0.1

Type RM Length L Ch R = 1 ,34908   ,193,193,193
BEGIN DESCRIPTION:
ROCK QUARRY BRANCH 65.0
END DESCRIPTION:
XS GIS Cut Line= 3
      2245008.93     13376159.17      2244314.49     13376013.34
      2243217.22      13375867.5
#Sta/Elev= 30
  4003.9  255.69  4127.8  252.57  4184.7  250.18  4234.6   249.5  4379.1  243.56
  4478.9   240.6  4505.8     239  4574.4  238.18  4659.1  236.17  4831.3   234.5
  4861.5  233.01  4876.6  230.55  4891.8  226.69  4929.2  224.94  4931.9  224.44
  4935.2  224.94  5106.5  225.44  5133.9  230.57    5144   233.4  5179.7  235.47
  5220.3  236.05  5345.8  240.06  5561.2  245.09  5587.9  246.81  5639.5   248.2
  5658.5  249.75  5688.8  250.37  5698.8  251.53  5729.1  251.53  5820.4  254.73
#Mann= 5 ,-1 , 0
  4003.9     .05       0  4574.4     .07       0  4929.2     .07       0
  4935.2     .07       0  5220.3      .1       0
Bank Sta=4861.5,5144
XS Rating Curve= 0 ,0
Exp/Cntr=0.3,0.1

Type RM Length L Ch R = 1 ,34732   ,152,152,152
BEGIN DESCRIPTION:
ROCK QUARRY BRANCH 64.0
END DESCRIPTION:
XS GIS Cut Line= 3
       2245092.3      13376082.8      2244481.16     13375874.45
      2243231.92     13375659.31
#Sta/Elev= 30
  3850.5  255.84  4102.5  249.64  4285.3  243.37    4373  238.71  4436.4  237.84
    4520  244.06  4659.2  243.19  4922.3  243.41  4996.9  244.95    4997  237.84
  4999.8  237.34    5003  237.84    5007  245.06    5102  244.94  5138.9  244.09
  5156.9  242.63    5162  244.35  5187.9  243.69  5216.8  241.95  5221.9  243.02
  5250.6  239.95  5276.7  238.52  5321.6  239.08  5402.8  243.38  5595.6  248.63
  5615.9  250.77    5631  250.37  5737.6  254.59  5750.8  253.93  5763.8  255.51
#Mann= 5 ,-1 , 0
  3850.5     .05       0  4659.2     .07       0    4997     .07       0
    5003     .07       0  5187.9      .1       0
Bank Sta=4997,5003
XS Rating Curve= 0 ,0
Exp/Cntr=0.3,0.1

Type RM Length L Ch R = 1 ,34715   ,152,152,152
BEGIN DESCRIPTION:
ROCK QUARRY BRANCH 64.0
END DESCRIPTION:
XS GIS Cut Line= 3
       2245092.3      13376082.8      2244481.16     13375874.45
      2243231.92     13375659.31
#Sta/Elev= 30
  3850.5  255.84  4102.5  249.64  4285.3  243.37  4353.2  239.25  4433.4  237.84
  4436.2  237.34  4439.4  237.84    4520  244.06  4659.2  243.19  4834.5  243.73
  4922.3  243.41    5007  245.06    5102  244.94  5138.9  244.09  5156.9  242.63
    5162  244.35  5187.9  243.69  5216.8  241.95  5221.9  243.02  5250.6  239.95
  5276.7  238.52  5321.6  239.08  5362.2  240.53  5402.8  243.38  5595.6  248.63
  5615.9  250.77    5631  250.37  5737.6  254.59  5750.8  253.93  5763.8  255.51
#Mann= 5 ,-1 , 0
  3850.5     .05       0  4433.4     .07       0  4439.4     .05       0
  4659.2     .07       0  5187.9      .1       0
Bank Sta=4834.5,5102
XS Rating Curve= 0 ,0
Exp/Cntr=0.3,0.1