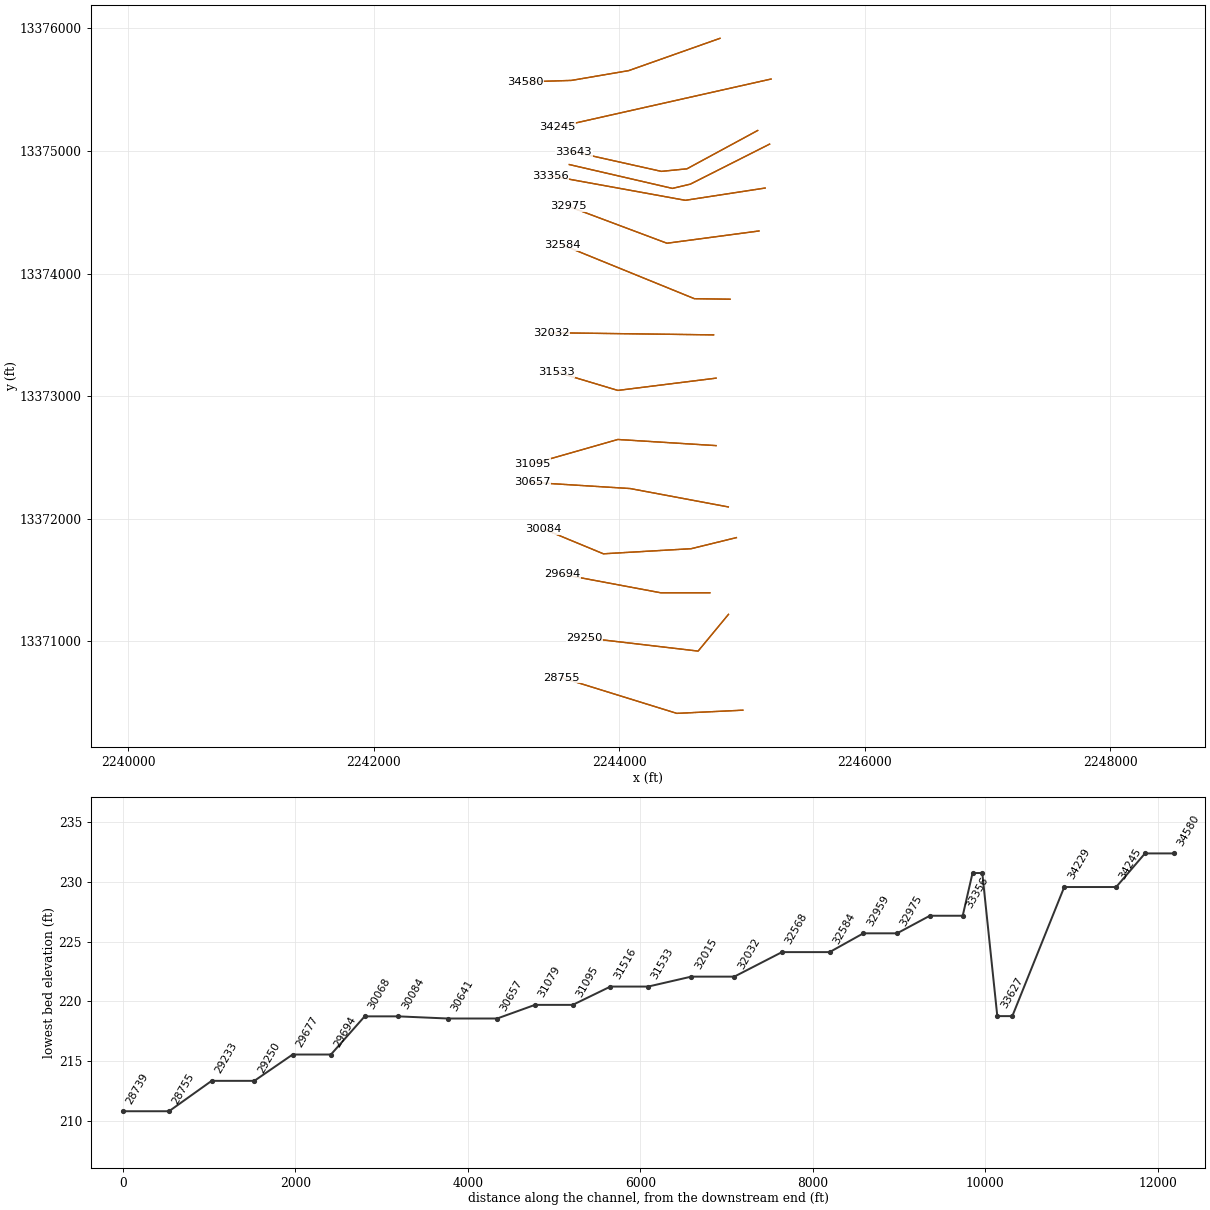
HEC-RAS study ROCK QUARRY BRANCH.prj: ROCK QUARRY BRANCH Base Level Engineering

--- ROCK QUARRY BRANCH.g01 (geometry) --- (continued)

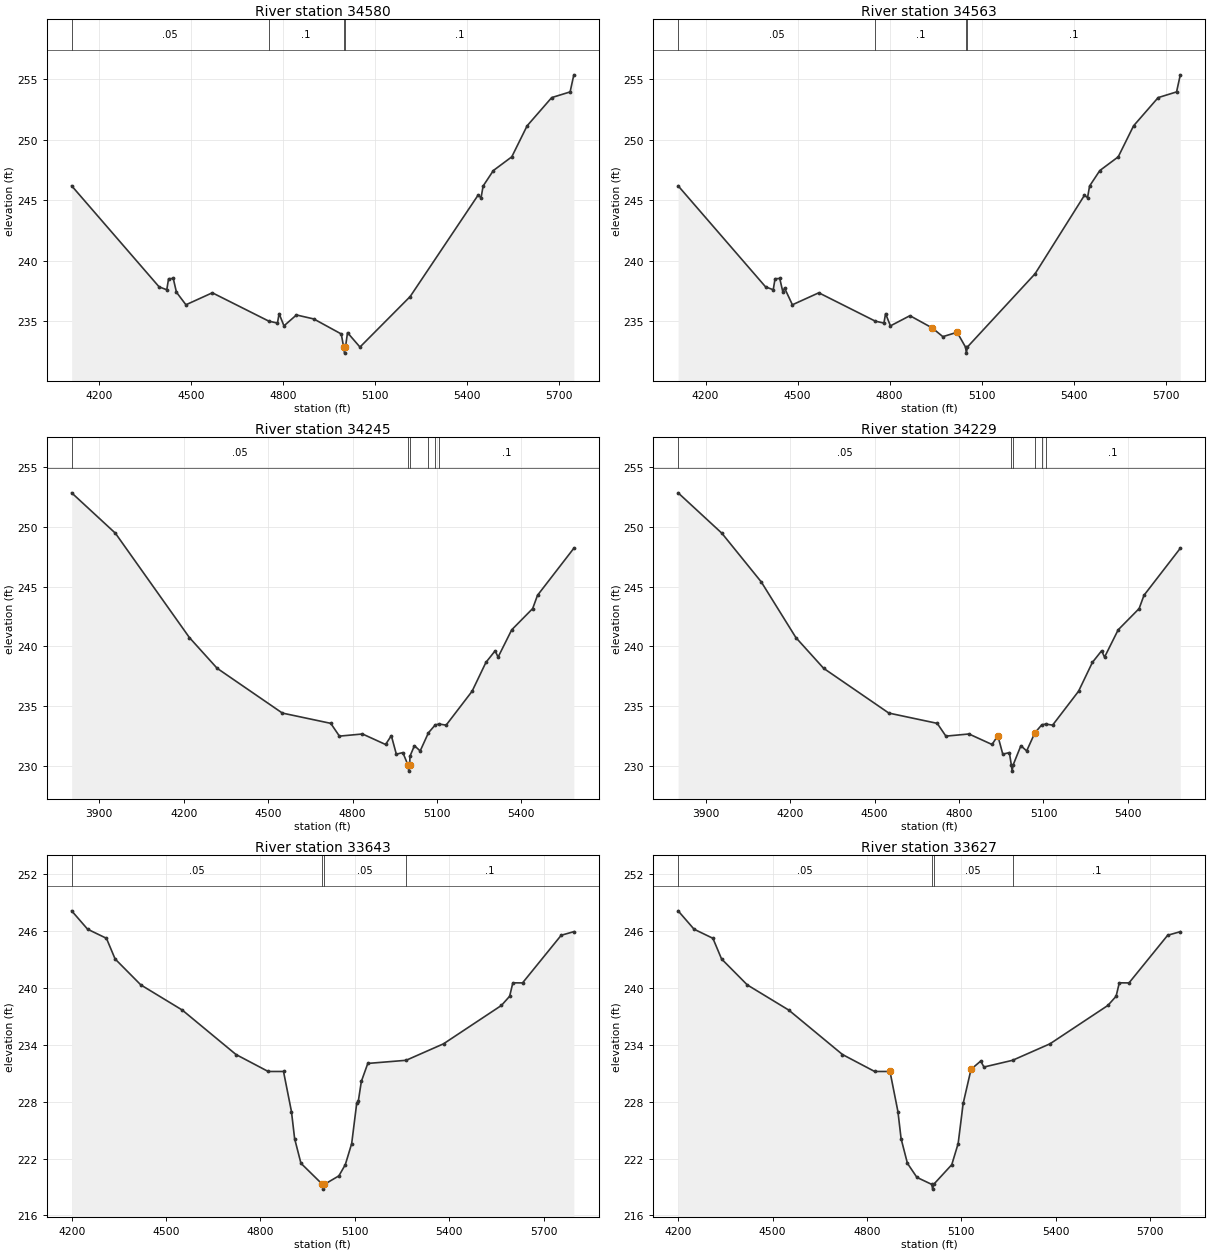
Type RM Length L Ch R = 1 ,34580   ,335,335,335
BEGIN DESCRIPTION:
Mapping XS 69c3c86b
END DESCRIPTION:
XS GIS Cut Line= 4
      2244819.97     13375917.43      2244076.04     13375654.15
      2243609.88     13375574.45      2243235.55     13375562.37
#Sta/Elev= 30
  4110.6  246.18  4395.6  237.84  4420.6   237.6  4426.5  238.51  4441.8  238.53
  4452.1   237.4    4483  236.36  4569.1  237.35  4753.1  235.01  4781.3  234.85
  4786.7  235.63  4802.5  234.62  4843.2  235.52  4899.8  235.19  4989.3  233.95
    4997  232.87  4999.8  232.37    5003  232.87  5009.6  234.06  5050.2  232.87
  5213.8  237.04  5434.9   245.4  5444.9   245.2  5451.5  246.16  5484.9  247.44
  5544.9  248.57  5594.9  251.13    5675  253.46    5735  253.93  5747.2  255.34
#Mann= 4 ,-1 , 0
  4110.6     .05       0  4753.1      .1       0    4997     .07       0
    5003      .1       0
Bank Sta=4997,5003
XS Rating Curve= 0 ,0
Exp/Cntr=0.3,0.1

Type RM Length L Ch R = 1 ,34563   ,334,334,334
BEGIN DESCRIPTION:
Mapping XS 69c3c86b
END DESCRIPTION:
XS GIS Cut Line= 4
      2244819.97     13375917.43      2244076.04     13375654.15
      2243609.88     13375574.45      2243235.55     13375562.37
#Sta/Elev= 30
  4110.6  246.18  4395.6  237.84  4420.6   237.6  4426.5  238.51  4441.8  238.53
  4452.1   237.4  4457.4  237.75    4483  236.36  4569.1  237.35  4753.1  235.01
  4781.3  234.85  4786.7  235.63  4802.5  234.62  4866.1  235.46  4938.6  234.45
  4973.4  233.73  5019.8  234.09  5047.2  232.87    5050  232.37  5053.2  232.87
  5273.9  238.92  5434.9   245.4  5444.9   245.2  5451.5  246.16  5484.9  247.44
  5544.9  248.57  5594.9  251.13    5675  253.46    5735  253.93  5747.2  255.34
#Mann= 4 ,-1 , 0
  4110.6     .05       0  4753.1      .1       0  5047.2     .07       0
  5053.2      .1       0
Bank Sta=4938.6,5019.8
XS Rating Curve= 0 ,0
Exp/Cntr=0.3,0.1

Type RM Length L Ch R = 1 ,34245   ,602,602,602
BEGIN DESCRIPTION:
ROCK QUARRY BRANCH 63.0
END DESCRIPTION:
XS GIS Cut Line= 2
      2245236.01     13375585.59      2243495.03     13375193.89
#Sta/Elev= 30
  3801.8  252.86  3957.2  249.48  4220.3  240.74  4318.8  238.17  4550.6  234.42
  4722.5  233.56  4753.3  232.49  4835.3  232.67  4917.3  231.79  4937.8  232.53
  4955.5  230.98  4978.8  231.11    4997  230.06  4999.8  229.56    5003  230.06
  5003.9   230.8  5019.8  231.69  5040.3  231.25  5069.6  232.77  5094.2  233.44
  5108.4   233.5  5132.5  233.41  5224.8  236.25  5273.8  238.66  5306.8  239.64
    5317   239.1  5365.5  241.39    5440  243.17  5457.2  244.28  5586.3  248.22
#Mann= 6 ,-1 , 0
  3801.8     .05       0    4997     .03       0    5003     .05       0
  5069.6      .1       0  5094.2     .05       0  5108.4      .1       0
Bank Sta=4997,5003
XS Rating Curve= 0 ,0
Exp/Cntr=0.3,0.1

Type RM Length L Ch R = 1 ,34229   ,602,602,602
BEGIN DESCRIPTION:
ROCK QUARRY BRANCH 63.0
END DESCRIPTION:
XS GIS Cut Line= 2
      2245236.01     13375585.59      2243495.03     13375193.89
#Sta/Elev= 30
  3801.8  252.86  3957.2  249.48  4097.3   245.4  4220.3  240.74  4318.8  238.17
  4550.6  234.42  4722.5  233.56  4753.3  232.49  4835.3  232.67  4917.3  231.79
  4937.8  232.53  4955.5  230.98  4978.8  231.11    4986  230.06  4988.8  229.56
    4992  230.06  5019.8  231.69  5040.3  231.25  5069.6  232.77  5094.2  233.44
  5108.4   233.5  5132.5  233.41  5224.8  236.25  5273.8  238.66  5306.8  239.64
    5317   239.1  5365.5  241.39    5440  243.17  5457.2  244.28  5586.3  248.22
#Mann= 6 ,-1 , 0
  3801.8     .05       0    4986     .03       0    4992     .05       0
  5069.6      .1       0  5094.2     .05       0  5108.4      .1       0
Bank Sta=4937.8,5069.6
XS Rating Curve= 0 ,0
Exp/Cntr=0.3,0.1

Type RM Length L Ch R = 1 ,33643   ,174,174,174
BEGIN DESCRIPTION:
ROCK QUARRY BRANCH 62.0
END DESCRIPTION:
XS GIS Cut Line= 4
      2245127.01     13375166.13       2244550.6     13374853.62
      2244342.27     13374832.79       2243628.5     13374992.17
#Sta/Elev= 30
  4199.7  248.15  4250.4  246.21  4310.3  245.25  4337.8  243.07  4419.6  240.33
  4551.5  237.67  4722.2  232.98  4824.5  231.19  4873.2  231.19  4898.5  226.95
  4908.5   224.1  4928.6   221.5    4997  219.27  4999.8  218.77    5003  219.27
  5049.2  220.17  5069.6  221.35  5089.9  223.58  5105.8  227.81  5110.9  228.04
  5120.6  230.14  5141.1  232.04  5262.8  232.37  5381.8  234.11  5565.8  238.16
    5592  239.13  5602.2  240.55    5633  240.54  5755.9  245.57  5796.1  245.95
#Mann= 4 ,-1 , 0
  4199.7     .05       0    4997     .03       0    5003     .05       0
  5262.8      .1       0
Bank Sta=4997,5003
XS Rating Curve= 0 ,0
Exp/Cntr=0.3,0.1

Type RM Length L Ch R = 1 ,33627   ,174,174,174
BEGIN DESCRIPTION:
ROCK QUARRY BRANCH 62.0
END DESCRIPTION:
XS GIS Cut Line= 4
      2245127.01     13375166.13       2244550.6     13374853.62
      2244342.27     13374832.79       2243628.5     13374992.17
#Sta/Elev= 30
  4199.7  248.15  4250.4  246.21  4310.3  245.25  4337.8  243.07  4419.6  240.33
  4551.5  237.67  4722.2  232.98  4824.5  231.19  4873.2  231.19  4898.5  226.95
  4908.5   224.1  4928.6   221.5  4958.8  220.01    5006  219.27  5008.8  218.77
    5012  219.27  5069.6  221.35  5089.9  223.58  5105.8  227.81  5130.9  231.42
  5161.6  232.29  5171.9  231.66  5262.8  232.37  5381.8  234.11  5565.8  238.16
    5592  239.13  5602.2  240.55    5633  240.54  5755.9  245.57  5796.1  245.95
#Mann= 4 ,-1 , 0
  4199.7     .05       0    5006     .03       0    5012     .05       0
  5262.8      .1       0
Bank Sta=4873.2,5130.9
XS Rating Curve= 0 ,0
Exp/Cntr=0.3,0.1

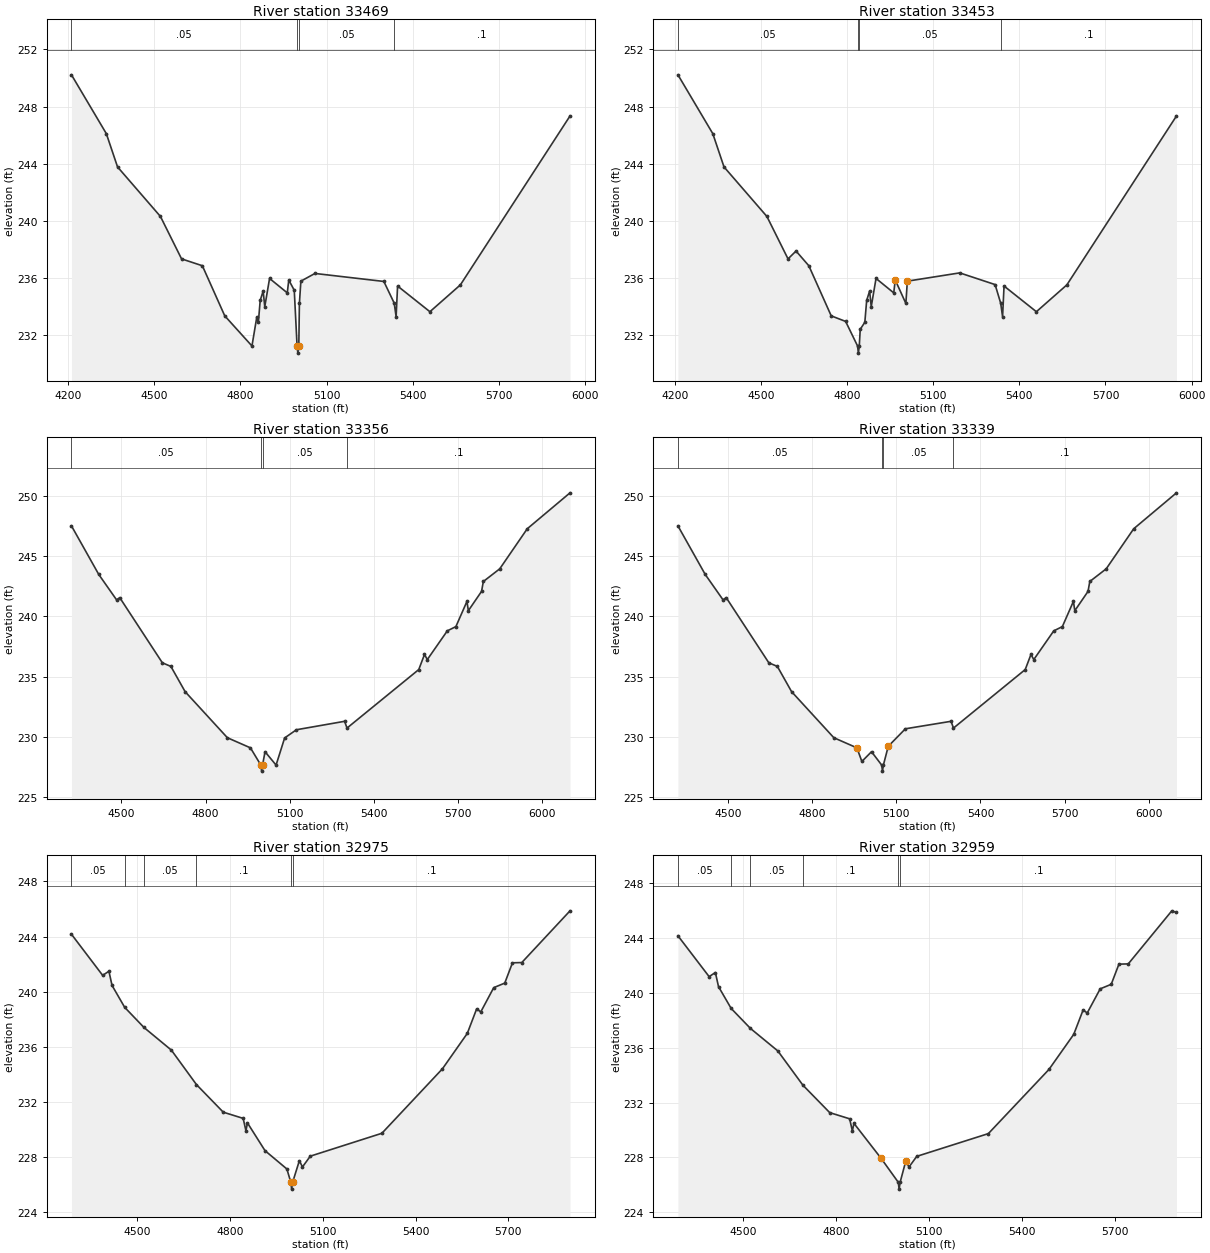
Type RM Length L Ch R = 1 ,33469   ,113,113,113
BEGIN DESCRIPTION:
Mapping XS 2e796d4d
END DESCRIPTION:
XS GIS Cut Line= 4
      2245224.22     13375055.01      2244578.38     13374728.62
      2244432.55      13374693.9      2243592.48     13374888.29
#Sta/Elev= 30
  4211.5  250.22  4332.9   246.1  4371.9  243.77  4521.3   240.3  4594.8  237.33
  4667.2  236.85  4745.2  233.34  4839.9  231.23  4856.6  233.24  4862.2  232.89
  4868.6  234.42  4878.9  235.08  4884.5  233.98  4901.2  235.96  4962.9  234.95
  4968.1  235.85  4987.2  235.13    4997  231.23  4999.8  230.73    5003  231.23
  5005.1  234.21  5010.2  235.77  5059.2  236.31  5299.1  235.75  5335.2  234.23
  5341.8  233.28  5346.9  235.43  5459.5  233.63  5565.6  235.51  5947.3  247.34
#Mann= 4 ,-1 , 0
  4211.5     .05       0    4997     .03       0    5003     .05       0
  5335.2      .1       0
Bank Sta=4997,5003
XS Rating Curve= 0 ,0
Exp/Cntr=0.3,0.1

Type RM Length L Ch R = 1 ,33453   ,114,114,114
BEGIN DESCRIPTION:
Mapping XS 2e796d4d
END DESCRIPTION:
XS GIS Cut Line= 4
      2245224.22     13375055.01      2244578.38     13374728.62
      2244432.55      13374693.9      2243592.48     13374888.29
#Sta/Elev= 30
  4211.5  250.22  4332.9   246.1  4371.9  243.77  4521.3   240.3  4594.8  237.33
  4622.7  237.88  4667.2  236.85  4745.2  233.34  4795.4  232.95  4836.9  231.23
  4839.7  230.73  4842.9  231.23  4846.2   232.4  4862.2  232.89  4868.6  234.42
  4878.9  235.08  4884.5  233.98  4901.2  235.96  4962.9  234.95  4968.1  235.85
  5005.1  234.21  5010.2  235.77  5192.6  236.35  5315.8  235.53  5335.2  234.23
  5341.8  233.28  5346.9  235.43  5459.5  233.63  5565.6  235.51  5947.3  247.34
#Mann= 4 ,-1 , 0
  4211.5     .05       0  4836.9     .03       0  4842.9     .05       0
  5335.2      .1       0
Bank Sta=4968.1,5010.2
XS Rating Curve= 0 ,0
Exp/Cntr=0.3,0.1

Type RM Length L Ch R = 1 ,33356   ,381,381,381
BEGIN DESCRIPTION:
ROCK QUARRY BRANCH 61.0
END DESCRIPTION:
XS GIS Cut Line= 3
      2245187.67     13374696.85      2244537.72     13374596.85
      2243437.75     13374796.85
#Sta/Elev= 30
  4322.5  247.49  4419.8  243.46  4483.1  241.36  4494.5  241.54  4646.2  236.14
  4676.6  235.84  4727.2  233.75  4877.7  229.93  4959.9  229.09    4997  227.66
  4999.8  227.16    5003  227.66  5011.9  228.77  5051.2  227.66  5081.7  229.91
  5123.7  230.59  5295.2  231.29  5303.9  230.73  5559.4  235.58  5579.8  236.83
  5589.9  236.41  5661.1  238.79  5691.6  239.14    5731  241.23    5736  240.46
    5783  242.06  5789.4  242.88  5847.8  243.93  5945.7  247.25  6098.1  250.23
#Mann= 4 ,-1 , 0
  4322.5     .05       0    4997     .03       0    5003     .05       0
  5303.9      .1       0
Bank Sta=4997,5003
XS Rating Curve= 0 ,0
Exp/Cntr=0.3,0.1

Type RM Length L Ch R = 1 ,33339   ,380,380,380
BEGIN DESCRIPTION:
ROCK QUARRY BRANCH 61.0
END DESCRIPTION:
XS GIS Cut Line= 3
      2245187.67     13374696.85      2244537.72     13374596.85
      2243437.75     13374796.85
#Sta/Elev= 30
  4322.5  247.49  4419.8  243.46  4483.1  241.36  4494.5  241.54  4646.2  236.14
  4676.6  235.84  4727.2  233.75  4877.7  229.93  4959.9  229.09  4977.6  227.96
  5011.9  228.77  5048.2  227.66    5051  227.16  5054.2  227.66  5071.6  229.22
  5132.6  230.67  5295.2  231.29  5303.9  230.73  5559.4  235.58  5579.8  236.83
  5589.9  236.41  5661.1  238.79  5691.6  239.14    5731  241.23    5736  240.46
    5783  242.06  5789.4  242.88  5847.8  243.93  5945.7  247.25  6098.1  250.23
#Mann= 4 ,-1 , 0
  4322.5     .05       0  5048.2     .03       0  5054.2     .05       0
  5303.9      .1       0
Bank Sta=4959.9,5071.6
XS Rating Curve= 0 ,0
Exp/Cntr=0.3,0.1

Type RM Length L Ch R = 1 ,32975   ,391,391,391
BEGIN DESCRIPTION:
ROCK QUARRY BRANCH 60.0
END DESCRIPTION:
XS GIS Cut Line= 3
      2245137.68     13374346.85      2244387.72     13374246.85
      2243587.72     13374546.86
#Sta/Elev= 30
  4288.3  244.17  4389.1  241.19  4409.3  241.49  4419.4  240.46  4460.3  238.87
  4522.7  237.41  4611.1  235.77  4692.2  233.27  4778.8  231.27  4843.1  230.82
    4852  229.93    4857  230.49  4913.7  228.48  4984.4  227.15    4997  226.19
  4999.8  225.69    5003  226.19  5024.7  227.75  5034.8   227.3    5060  228.08
  5291.4  229.74  5487.2  234.42  5567.3  236.98  5597.6  238.76  5610.9  238.54
  5652.8   240.3  5688.4  240.63  5713.3   242.1  5743.5  242.12  5899.3  245.87
#Mann= 6 ,-1 , 0
  4288.3     .05       0  4460.3      .1       0  4522.7     .05       0
  4692.2      .1       0    4997     .07       0    5003      .1       0
Bank Sta=4997,5003
XS Rating Curve= 0 ,0
Exp/Cntr=0.3,0.1

Type RM Length L Ch R = 1 ,32959   ,391,391,391
BEGIN DESCRIPTION:
ROCK QUARRY BRANCH 60.0
END DESCRIPTION:
XS GIS Cut Line= 3
      2245137.68     13374346.85      2244387.72     13374246.85
      2243587.72     13374546.86
#Sta/Elev= 30
  4288.3  244.17  4389.1  241.19  4409.3  241.49  4419.4  240.46  4460.3  238.87
  4522.7  237.41  4611.1  235.77  4692.2  233.27  4778.8  231.27  4843.1  230.82
    4852  229.93    4857  230.49    4944  227.96  5000.3  226.19    5003  225.69
  5006.3  226.19  5024.7  227.75  5034.8   227.3    5060  228.08  5291.4  229.74
  5487.2  234.42  5567.3  236.98  5597.6  238.76  5610.9  238.54  5652.8   240.3
  5688.4  240.63  5713.3   242.1  5743.5  242.12  5884.2  245.99  5899.3  245.87
#Mann= 6 ,-1 , 0
  4288.3     .05       0  4460.3      .1       0  4522.7     .05       0
  4692.2      .1       0  5000.3     .07       0  5006.3      .1       0
Bank Sta=4944,5024.7
XS Rating Curve= 0 ,0
Exp/Cntr=0.3,0.1

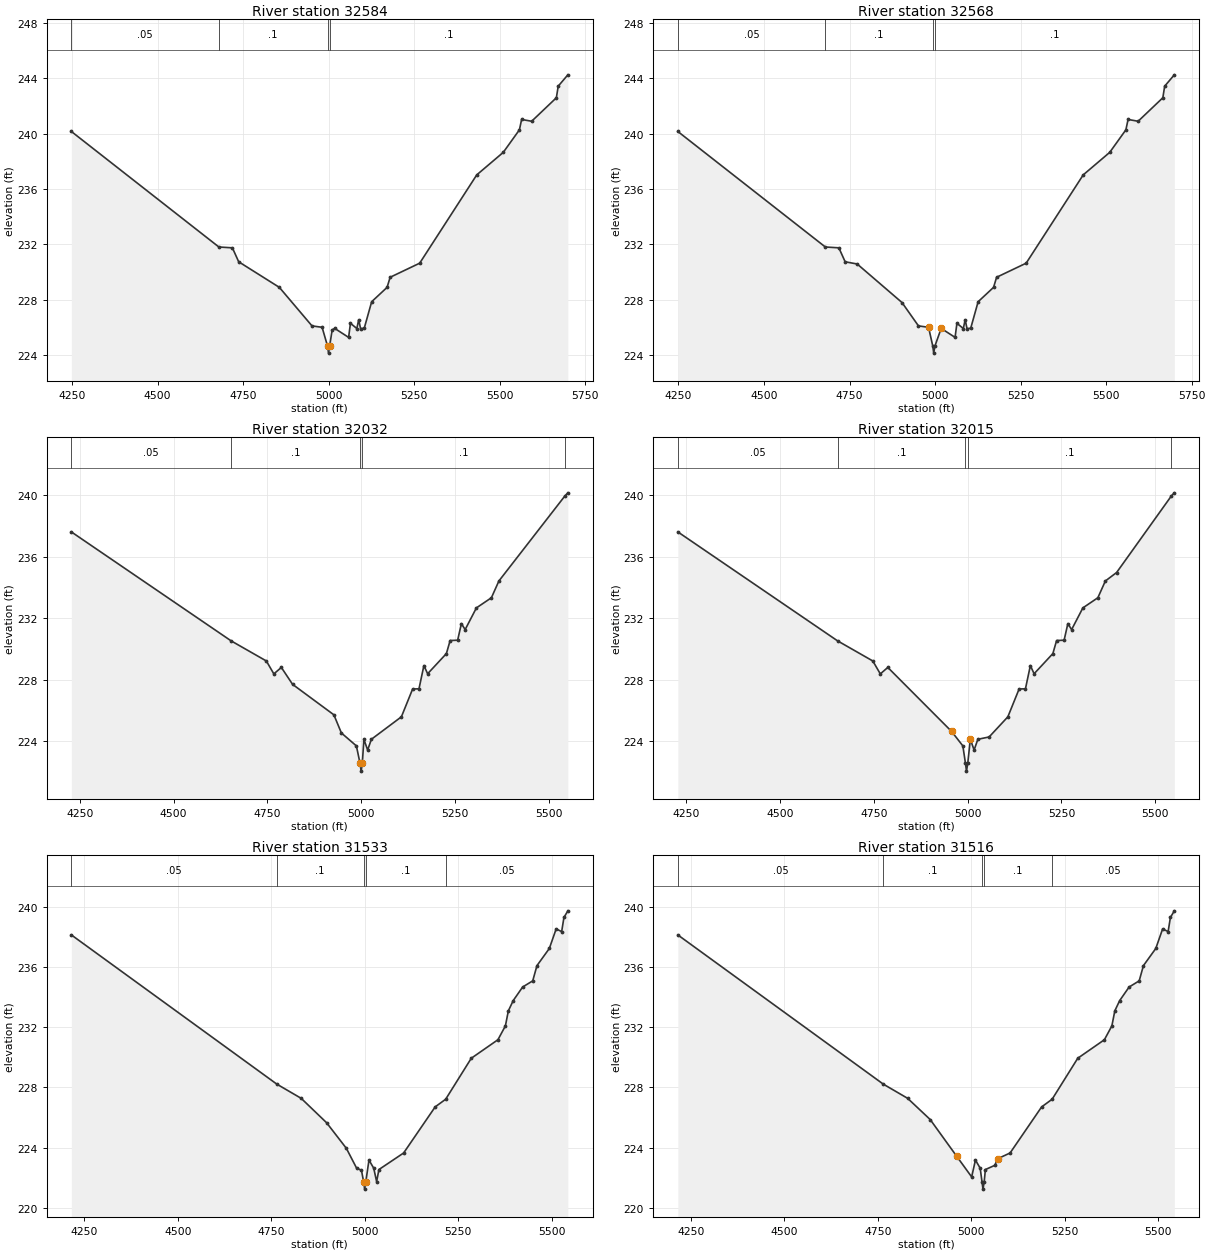
Type RM Length L Ch R = 1 ,32584   ,552,552,552
BEGIN DESCRIPTION:
ROCK QUARRY BRANCH 59.0
END DESCRIPTION:
XS GIS Cut Line= 3
      2244902.16     13373790.47      2244611.36     13373794.81
       2243536.6     13374232.52
#Sta/Elev= 30
  4248.1  240.16  4679.3   231.8  4718.8  231.74  4737.2  230.73    4856  228.88
  4951.5  226.09    4981  225.99    4997  224.62  4999.8  224.12    5003  224.62
  5010.4   225.8  5017.9  225.91  5058.5  225.26  5063.9  226.28  5082.6   225.9
    5088  226.54  5093.5  225.88  5104.3  225.93  5125.9  227.84    5171  228.88
  5179.9  229.61  5266.3  230.63  5433.1  237.02  5510.6  238.65  5557.8  240.28
  5564.2  241.03  5593.6   240.9  5665.8   242.6  5671.2  243.44  5699.4  244.26
#Mann= 4 ,-1 , 0
  4248.1     .05       0  4679.3      .1       0    4997     .07       0
    5003      .1       0
Bank Sta=4997,5003
XS Rating Curve= 0 ,0
Exp/Cntr=0.3,0.1

Type RM Length L Ch R = 1 ,32568   ,553,553,553
BEGIN DESCRIPTION:
ROCK QUARRY BRANCH 59.0
END DESCRIPTION:
XS GIS Cut Line= 3
      2244902.16     13373790.47      2244611.36     13373794.81
       2243536.6     13374232.52
#Sta/Elev= 30
  4248.1  240.16  4679.3   231.8  4718.8  231.74  4737.2  230.73  4772.4  230.57
  4903.4  227.78  4951.5  226.09    4981  225.99  4993.4  224.62  4996.1  224.12
  4999.4  224.62  5017.9  225.91  5058.5  225.26  5063.9  226.28  5082.6   225.9
    5088  226.54  5093.5  225.88  5104.3  225.93  5125.9  227.84    5171  228.88
  5179.9  229.61  5266.3  230.63  5433.1  237.02  5510.6  238.65  5557.8  240.28
  5564.2  241.03  5593.6   240.9  5665.8   242.6  5671.2  243.44  5699.4  244.26
#Mann= 4 ,-1 , 0
  4248.1     .05       0  4679.3      .1       0  4993.4     .07       0
  4999.4      .1       0
Bank Sta=4981,5017.9
XS Rating Curve= 0 ,0
Exp/Cntr=0.3,0.1

Type RM Length L Ch R = 1 ,32032   ,499,499,499
BEGIN DESCRIPTION:
ROCK QUARRY BRANCH 58.0
END DESCRIPTION:
XS GIS Cut Line= 2
      2244767.62     13373499.68      2243443.83     13373517.04
#Sta/Elev= 30
  4227.2  237.62    4653  230.54  4747.1  229.23  4767.1  228.39  4787.1  228.81
  4817.1  227.71  4927.2  225.73  4947.2  224.55  4987.2  223.71    4997  222.57
  4999.8  222.07    5003  222.57  5007.2  224.14  5017.2  223.44  5027.2  224.14
  5107.2   225.6  5137.2  227.41  5154.1  227.42  5167.2  228.93  5177.2   228.4
  5227.2  229.71  5237.2  230.56  5257.2  230.58  5267.2  231.66  5277.2  231.27
  5307.2  232.68  5347.2  233.34  5367.2  234.43  5543.3  239.96  5551.1  240.16
#Mann= 5 ,-1 , 0
  4227.2     .05       0    4653      .1       0    4997     .07       0
    5003      .1       0  5543.3     .05       0
Bank Sta=4997,5003
XS Rating Curve= 0 ,0
Exp/Cntr=0.3,0.1

Type RM Length L Ch R = 1 ,32015   ,499,499,499
BEGIN DESCRIPTION:
ROCK QUARRY BRANCH 58.0
END DESCRIPTION:
XS GIS Cut Line= 2
      2244767.62     13373499.68      2243443.83     13373517.04
#Sta/Elev= 30
  4227.2  237.62    4653  230.54  4747.1  229.23  4767.1  228.39  4787.1  228.81
  4957.2  224.65  4987.2  223.71  4994.2  222.57  4996.9  222.07  5000.2  222.57
  5007.2  224.14  5017.2  223.44  5027.2  224.14  5057.2  224.29  5107.2   225.6
  5137.2  227.41  5154.1  227.42  5167.2  228.93  5177.2   228.4  5227.2  229.71
  5237.2  230.56  5257.2  230.58  5267.2  231.66  5277.2  231.27  5307.2  232.68
  5347.2  233.34  5367.2  234.43  5397.2  234.98  5543.3  239.96  5551.1  240.16
#Mann= 5 ,-1 , 0
  4227.2     .05       0    4653      .1       0  4994.2     .07       0
  5000.2      .1       0  5543.3     .05       0
Bank Sta=4957.2,5007.2
XS Rating Curve= 0 ,0
Exp/Cntr=0.3,0.1

Type RM Length L Ch R = 1 ,31533   ,438,438,438
BEGIN DESCRIPTION:
ROCK QUARRY BRANCH 57.0
END DESCRIPTION:
XS GIS Cut Line= 3
      2244787.75     13373146.86      2243987.72     13373046.85
      2243487.69     13373196.86
#Sta/Elev= 30
  4215.2  238.12    4765  228.21    4830  227.27    4898  225.65  4950.9  223.95
  4978.6  222.62  4991.2   222.5    4997  221.74  4999.8  221.24    5003  221.74
  5011.4  223.17  5024.1  222.63  5031.9  221.74    5038  222.54  5104.1  223.64
  5188.5   226.7  5216.6  227.21  5285.1  229.93  5356.4  231.16  5376.4  232.08
  5384.3  233.08  5397.3  233.76  5422.5  234.66  5449.5  235.07  5460.8  236.08
  5493.9  237.22  5512.2  238.52  5526.9  238.34    5533  239.28  5543.5  239.72
#Mann= 5 ,-1 , 0
  4215.2     .05       0    4765      .1       0    4997     .07       0
    5003      .1       0  5216.6     .05       0
Bank Sta=4997,5003
XS Rating Curve= 0 ,0
Exp/Cntr=0.3,0.1

Type RM Length L Ch R = 1 ,31516   ,437,437,437
BEGIN DESCRIPTION:
ROCK QUARRY BRANCH 57.0
END DESCRIPTION:
XS GIS Cut Line= 3
      2244787.75     13373146.86      2243987.72     13373046.85
      2243487.69     13373196.86
#Sta/Elev= 30
  4215.2  238.12    4765  228.21    4830  227.27  4890.4  225.86    4961  223.43
  5001.3  222.05  5011.4  223.17  5024.1  222.63  5028.9  221.74  5031.6  221.24
  5034.9  221.74    5038  222.54  5063.2  222.82    5071  223.26  5104.1  223.64
  5188.5   226.7  5216.6  227.21  5285.1  229.93  5356.4  231.16  5376.4  232.08
  5384.3  233.08  5397.3  233.76  5422.5  234.66  5449.5  235.07  5460.8  236.08
  5493.9  237.22  5512.2  238.52  5526.9  238.34    5533  239.28  5543.5  239.72
#Mann= 5 ,-1 , 0
  4215.2     .05       0    4765      .1       0  5028.9     .07       0
  5034.9      .1       0  5216.6     .05       0
Bank Sta=4961,5071
XS Rating Curve= 0 ,0
Exp/Cntr=0.3,0.1

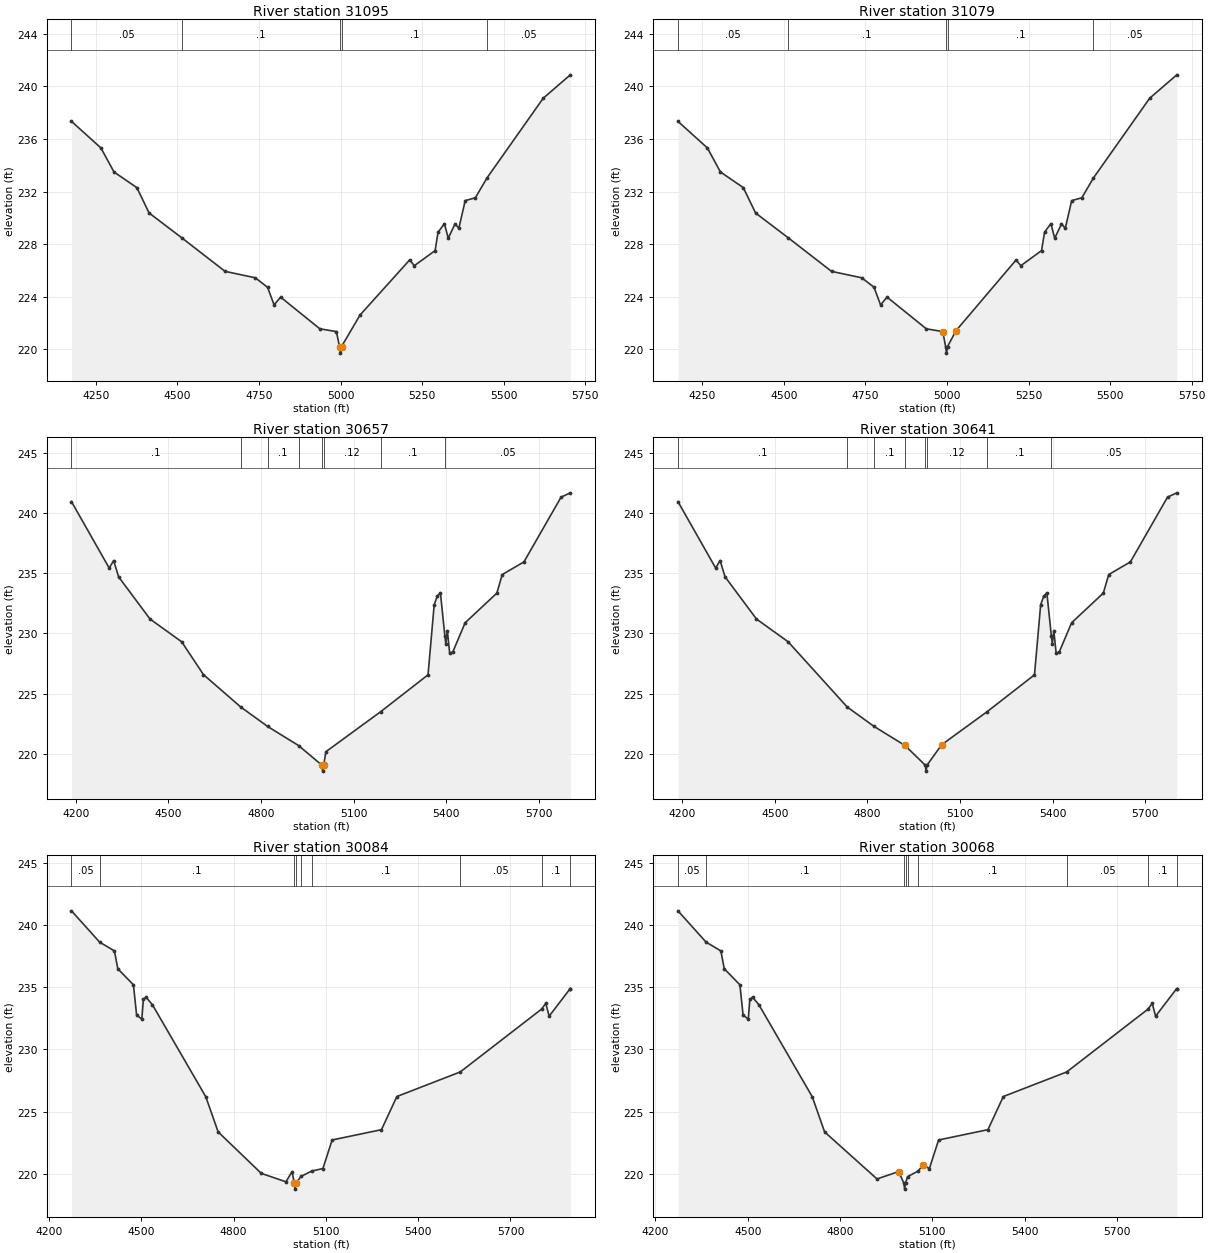
Type RM Length L Ch R = 1 ,31095   ,438,438,438
BEGIN DESCRIPTION:
ROCK QUARRY BRANCH 56.0
END DESCRIPTION:
XS GIS Cut Line= 3
      2244787.74     13372596.85      2243987.72     13372646.85
      2243287.71     13372446.85
#Sta/Elev= 30
    4175  237.34  4265.2  235.32  4305.3  233.49  4375.4   232.3    4413  230.37
  4513.8  228.47  4645.9  225.93  4738.6  225.44  4776.2  224.72  4796.2  223.38
  4816.3  223.97  4936.5  221.56    4987  221.35    4997  220.21  4999.8  219.71
    5003  220.21  5059.8  222.61  5211.9   226.8  5226.2  226.36  5289.9  227.51
    5299  228.91  5318.5  229.56  5330.2  228.45    5351  229.54  5362.7  229.21
  5382.2  231.31  5413.4  231.53  5449.1  233.04  5621.4   239.1  5704.6  240.88
#Mann= 5 ,-1 , 0
    4175     .05       0  4513.8      .1       0    4997     .07       0
    5003      .1       0  5449.1     .05       0
Bank Sta=4997,5003
XS Rating Curve= 0 ,0
Exp/Cntr=0.3,0.1

Type RM Length L Ch R = 1 ,31079   ,438,438,438
BEGIN DESCRIPTION:
ROCK QUARRY BRANCH 56.0
END DESCRIPTION:
XS GIS Cut Line= 3
      2244787.74     13372596.85      2243987.72     13372646.85
      2243287.71     13372446.85
#Sta/Elev= 30
    4175  237.34  4265.2  235.32  4305.3  233.49  4375.4   232.3    4413  230.37
  4513.8  228.47  4645.9  225.93  4738.6  225.44  4776.2  224.72  4796.2  223.38
  4816.3  223.97  4936.5  221.56    4987  221.35  4995.7  220.21  4998.4  219.71
  5001.7  220.21  5027.3  221.41  5211.9   226.8  5226.2  226.36  5289.9  227.51
    5299  228.91  5318.5  229.56  5330.2  228.45    5351  229.54  5362.7  229.21
  5382.2  231.31  5413.4  231.53  5449.1  233.04  5621.4   239.1  5704.6  240.88
#Mann= 5 ,-1 , 0
    4175     .05       0  4513.8      .1       0  4995.7     .07       0
  5001.7      .1       0  5449.1     .05       0
Bank Sta=4987,5027.3
XS Rating Curve= 0 ,0
Exp/Cntr=0.3,0.1

Type RM Length L Ch R = 1 ,30657   ,573,573,573
BEGIN DESCRIPTION:
ROCK QUARRY BRANCH 55.0
END DESCRIPTION:
XS GIS Cut Line= 3
      2244887.69     13372096.86      2244087.72     13372246.85
      2243287.69     13372296.86
#Sta/Elev= 30
  4186.3  240.93  4308.4  235.42  4322.8  236.04  4338.9  234.69  4440.6  231.19
  4543.2   229.3  4613.6  226.58  4734.4  223.89  4821.3  222.28  4921.8  220.69
    4997  219.07  4999.8  218.57    5003  219.07  5010.2  220.18  5187.5   223.5
  5340.9  226.56  5360.9  232.38  5370.9  233.09    5381  233.37  5395.6  229.75
  5398.5  229.14  5403.5  230.22    5411  228.36    5421  228.45  5461.1  230.88
  5563.8  233.34  5581.3  234.88  5651.5  235.93  5771.7   241.3  5801.8  241.66
#Mann= 8 ,-1 , 0
  4186.3      .1       0  4734.4     .12       0  4821.3      .1       0
  4921.8     .12       0    4997     .07       0    5003     .12       0
  5187.5      .1       0  5395.6     .05       0
Bank Sta=4997,5003
XS Rating Curve= 0 ,0
Exp/Cntr=0.3,0.1

Type RM Length L Ch R = 1 ,30641   ,573,573,573
BEGIN DESCRIPTION:
ROCK QUARRY BRANCH 55.0
END DESCRIPTION:
XS GIS Cut Line= 3
      2244887.69     13372096.86      2244087.72     13372246.85
      2243287.69     13372296.86
#Sta/Elev= 30
  4186.3  240.93  4308.4  235.42  4322.8  236.04  4338.9  234.69  4440.6  231.19
  4543.2   229.3  4734.4  223.89  4821.3  222.28  4921.4   220.7  4921.8  220.69
    4987  219.07  4989.8  218.57    4993  219.07  5040.3  220.76  5187.5   223.5
  5340.9  226.56  5360.9  232.38  5370.9  233.09    5381  233.37  5395.6  229.75
  5398.5  229.14  5403.5  230.22    5411  228.36    5421  228.45  5461.1  230.88
  5563.8  233.34  5581.3  234.88  5651.5  235.93  5771.7   241.3  5801.8  241.66
#Mann= 8 ,-1 , 0
  4186.3      .1       0  4734.4     .12       0  4821.3      .1       0
  4921.8     .12       0    4987     .07       0    4993     .12       0
  5187.5      .1       0  5395.6     .05       0
Bank Sta=4921.4,5040.3
XS Rating Curve= 0 ,0
Exp/Cntr=0.3,0.1

Type RM Length L Ch R = 1 ,30084   ,390,390,390
BEGIN DESCRIPTION:
ROCK QUARRY BRANCH 54.0
END DESCRIPTION:
XS GIS Cut Line= 4
      2244953.34     13371846.67      2244585.33      13371756.4
      2243870.05     13371714.73      2243383.93     13371916.12
#Sta/Elev= 30
    4273  241.17  4364.4  238.65  4412.6  237.94  4423.6   236.5  4474.4  235.21
  4484.7  232.77  4501.6  232.45  4506.8  234.05  4515.6  234.21  4536.2   233.6
  4709.6  226.19  4749.7  223.36  4889.9  220.02  4970.1  219.34  4990.1  220.16
    4997  219.25  4999.8  218.75    5003  219.25  5019.5  219.78  5053.5   220.2
  5090.3  220.41  5120.3  222.71  5280.6  223.54  5330.7  226.21  5536.7  228.19
  5800.9  233.25  5814.7  233.72  5825.6  232.68  5894.3  234.91  5894.6  234.91
#Mann= 9 ,-1 , 0
    4273     .05       0  4364.4      .1       0    4997     .07       0
    5003      .1       0  5019.5     .12       0  5053.5      .1       0
  5536.7     .05       0  5800.9      .1       0  5894.3     .05       0
Bank Sta=4997,5003
XS Rating Curve= 0 ,0
Exp/Cntr=0.3,0.1

Type RM Length L Ch R = 1 ,30068   ,391,391,391
BEGIN DESCRIPTION:
ROCK QUARRY BRANCH 54.0
END DESCRIPTION:
XS GIS Cut Line= 4
      2244953.34     13371846.67      2244585.33      13371756.4
      2243870.05     13371714.73      2243383.93     13371916.12
#Sta/Elev= 30
    4273  241.17  4364.4  238.65  4412.6  237.94  4423.6   236.5  4474.4  235.21
  4484.7  232.77  4501.6  232.45  4506.8  234.05  4515.6  234.21  4536.2   233.6
  4709.6  226.19  4749.7  223.36    4920  219.57  4990.1  220.16  5007.1  219.25
  5009.9  218.75  5013.1  219.25  5019.5  219.76  5053.5   220.2  5069.6  220.69
  5090.3  220.41  5120.3  222.71  5280.6  223.54  5330.7  226.21  5536.7  228.19
  5800.9  233.25  5814.7  233.72  5825.6  232.68  5894.3  234.91  5894.6  234.91
#Mann= 9 ,-1 , 0
    4273     .05       0  4364.4      .1       0  5007.1     .07       0
  5013.1      .1       0  5019.5     .12       0  5053.5      .1       0
  5536.7     .05       0  5800.9      .1       0  5894.3     .05       0
Bank Sta=4990.1,5069.6
XS Rating Curve= 0 ,0
Exp/Cntr=0.3,0.1

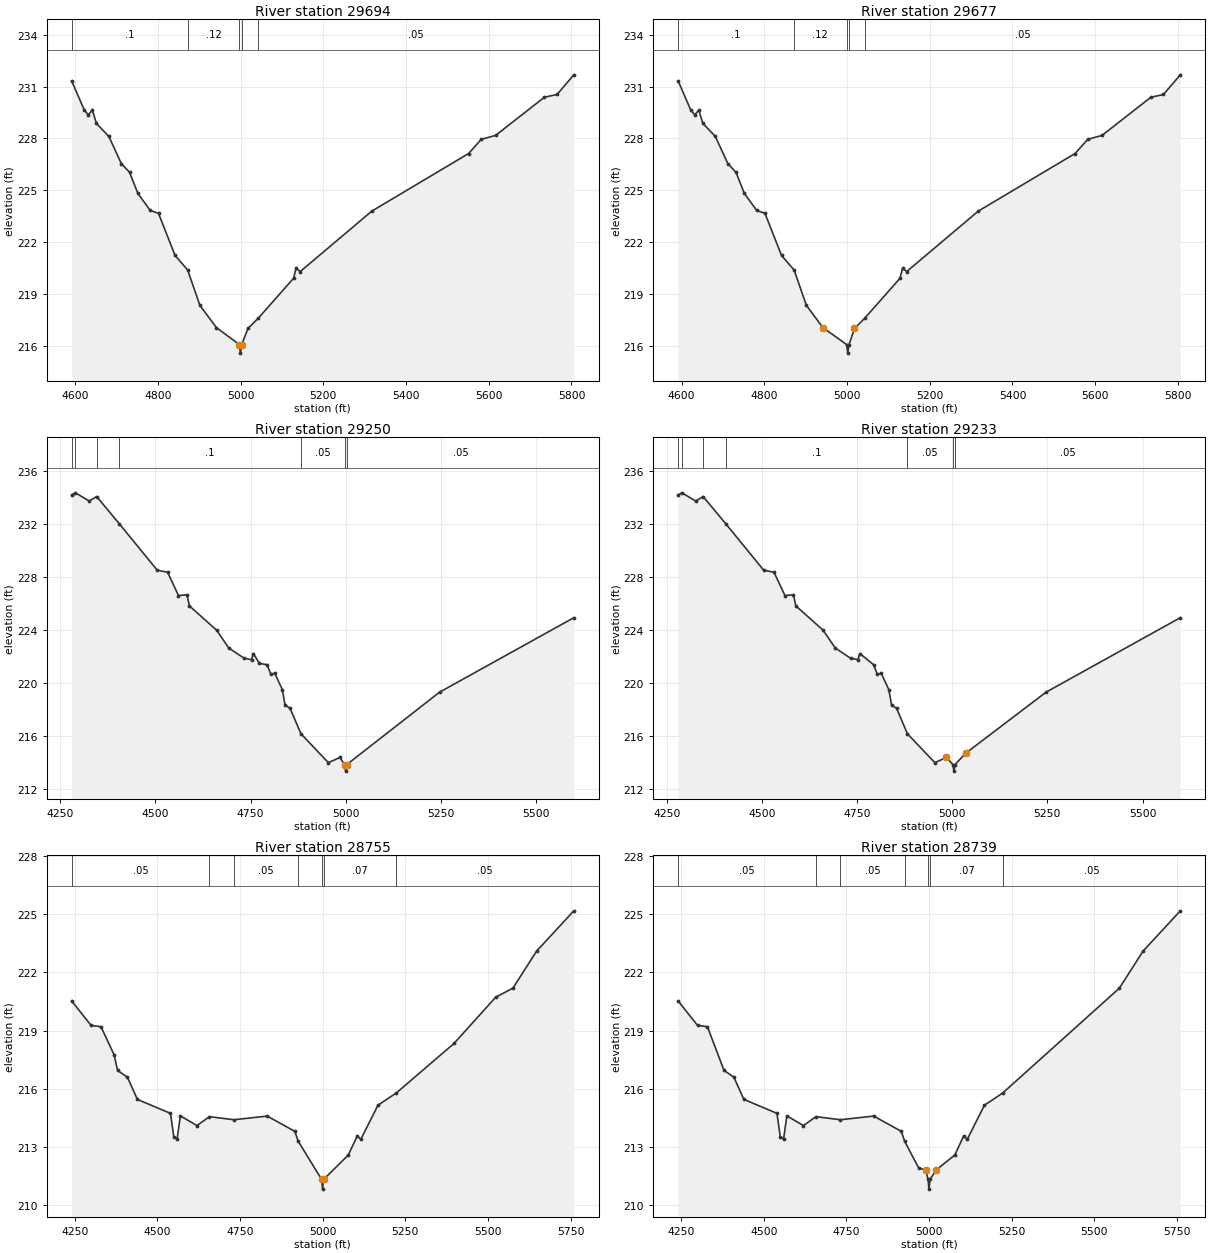
Type RM Length L Ch R = 1 ,29694   ,444,444,444
BEGIN DESCRIPTION:
ROCK QUARRY BRANCH 53.0
END DESCRIPTION:
XS GIS Cut Line= 3
      2244737.76     13371396.85      2244337.72     13371396.85
      2243537.71     13371546.86
#Sta/Elev= 30
  4591.8  231.34  4621.8  229.68  4631.8  229.37  4641.8  229.64  4651.8  228.87
  4681.8  228.12  4711.8  226.55  4731.8  226.04  4751.8  224.82  4781.8  223.83
  4801.8  223.66  4841.8  221.22  4872.2  220.38  4901.8  218.33  4941.8  217.04
    4997  216.06  4999.8  215.56    5003  216.06  5018.1  216.99  5042.8  217.58
  5128.3   219.9  5134.3  220.48  5144.5  220.29  5317.4  223.79  5551.4  227.13
    5582  227.95  5616.7  228.18  5734.6  230.39  5765.1  230.55  5805.8  231.69
#Mann= 5 ,-1 , 0
  4591.8      .1       0  4872.2     .12       0    4997     .07       0
    5003     .12       0  5042.8     .05       0
Bank Sta=4997,5003
XS Rating Curve= 0 ,0
Exp/Cntr=0.3,0.1

Type RM Length L Ch R = 1 ,29677   ,444,444,444
BEGIN DESCRIPTION:
ROCK QUARRY BRANCH 53.0
END DESCRIPTION:
XS GIS Cut Line= 3
      2244737.76     13371396.85      2244337.72     13371396.85
      2243537.71     13371546.86
#Sta/Elev= 30
  4591.8  231.34  4621.8  229.68  4631.8  229.37  4641.8  229.64  4651.8  228.87
  4681.8  228.12  4711.8  226.55  4731.8  226.04  4751.8  224.82  4781.8  223.83
  4801.8  223.66  4841.8  221.22  4872.2  220.38  4901.8  218.33  4941.8  217.04
    4999  216.06  5001.8  215.56    5005  216.06  5018.1  216.99  5042.8  217.58
  5128.3   219.9  5134.3  220.48  5144.5  220.29  5317.4  223.79  5551.4  227.13
    5582  227.95  5616.7  228.18  5734.6  230.39  5765.1  230.55  5805.8  231.69
#Mann= 5 ,-1 , 0
  4591.8      .1       0  4872.2     .12       0    4999     .07       0
    5005     .12       0  5042.8     .05       0
Bank Sta=4941.8,5018.1
XS Rating Curve= 0 ,0
Exp/Cntr=0.3,0.1

Type RM Length L Ch R = 1 ,29250   ,495,495,495
BEGIN DESCRIPTION:
ROCK QUARRY BRANCH 52.0
END DESCRIPTION:
XS GIS Cut Line= 3
      2244889.16     13371221.06      2244641.74     13370921.55
      2243717.27     13371030.06
#Sta/Elev= 30
    4280  234.22  4289.9  234.38  4326.2  233.76  4345.7   234.1  4405.3  232.04
  4504.7  228.54    4532  228.38  4560.7  226.62  4582.9  226.68  4589.4  225.84
    4661     224  4692.7  222.66  4732.9  221.89  4752.5  221.78  4757.5  222.24
  4773.2   221.5  4793.4   221.4  4803.4  220.67  4813.5  220.76  4833.6  219.51
  4840.7  218.35  4853.8  218.11  4882.4  216.18  4954.5     214  4984.7  214.39
    4997  213.86  4999.8  213.36    5003  213.86  5246.4  219.32  5599.3  224.95
#Mann= 7 ,-1 , 0
    4280     .05       0  4289.9      .1       0  4345.7     .05       0
  4405.3      .1       0  4882.4     .05       0    4997     .03       0
    5003     .05       0
Bank Sta=4997,5003
XS Rating Curve= 0 ,0
Exp/Cntr=0.3,0.1

Type RM Length L Ch R = 1 ,29233   ,494,494,494
BEGIN DESCRIPTION:
ROCK QUARRY BRANCH 52.0
END DESCRIPTION:
XS GIS Cut Line= 3
      2244889.16     13371221.06      2244641.74     13370921.55
      2243717.27     13371030.06
#Sta/Elev= 30
    4280  234.22  4289.9  234.38  4326.2  233.76  4345.7   234.1  4405.3  232.04
  4504.7  228.54    4532  228.38  4560.7  226.62  4582.9  226.68  4589.4  225.84
    4661     224  4692.7  222.66  4732.9  221.89  4752.5  221.78  4757.5  222.24
  4793.4   221.4  4803.4  220.67  4813.5  220.76  4833.6  219.51  4840.7  218.35
  4853.8  218.11  4882.4  216.18  4954.5     214  4984.7  214.39  5001.8  213.86
  5004.5  213.36  5007.8  213.86    5035   214.7  5246.4  219.32  5599.3  224.95
#Mann= 7 ,-1 , 0
    4280     .05       0  4289.9      .1       0  4345.7     .05       0
  4405.3      .1       0  4882.4     .05       0  5001.8     .03       0
  5007.8     .05       0
Bank Sta=4984.7,5035
XS Rating Curve= 0 ,0
Exp/Cntr=0.3,0.1

Type RM Length L Ch R = 1 ,28755   ,537,537,537
BEGIN DESCRIPTION:
ROCK QUARRY BRANCH 51.0
END DESCRIPTION:
XS GIS Cut Line= 3
      2245006.35     13370439.78      2244468.13     13370413.74
       2243531.7     13370704.21
#Sta/Elev= 30
  4240.7  220.53  4299.4  219.27  4329.4   219.2  4369.5  217.74  4379.5  216.95
  4409.6  216.59  4439.6  215.45  4539.7  214.73  4549.7  213.53  4559.7   213.4
  4569.7   214.6  4619.8   214.1  4657.7  214.56  4731.7   214.4  4832.3  214.59
  4916.1   213.8  4925.8   213.3    4997  211.32  4999.8  210.82    5003  211.32
  5077.7  212.58  5104.6  213.56  5115.5  213.39  5167.4  215.15  5222.8  215.78
  5397.7  218.34  5523.4  220.72  5575.7  221.19  5647.3   223.1    5760  225.18
#Mann= 7 ,-1 , 0
  4240.7     .05       0  4657.7      .1       0  4731.7     .05       0
  4925.8     .07       0    4997     .07       0    5003     .07       0
  5222.8     .05       0
Bank Sta=4997,5003
XS Rating Curve= 0 ,0
Exp/Cntr=0.3,0.1

Type RM Length L Ch R = 1 ,28739   ,537,537,537
BEGIN DESCRIPTION:
ROCK QUARRY BRANCH 51.0
END DESCRIPTION:
XS GIS Cut Line= 3
      2245006.35     13370439.78      2244468.13     13370413.74
       2243531.7     13370704.21
#Sta/Elev= 30
  4240.7  220.53  4299.4  219.27  4329.4   219.2  4379.5  216.95  4409.6  216.59
  4439.6  215.45  4539.7  214.73  4549.7  213.53  4559.7   213.4  4569.7   214.6
  4619.8   214.1  4657.7  214.56  4731.7   214.4  4832.3  214.59  4916.1   213.8
  4925.8   213.3  4968.4  211.91  4989.4  211.81  4996.9  211.32  4999.6  210.82
  5002.9  211.32  5020.8   211.8  5077.7  212.58  5104.6  213.56  5115.5  213.39
  5167.4  215.15  5222.8  215.78  5575.7  221.19  5647.3   223.1    5760  225.18
#Mann= 7 ,-1 , 0
  4240.7     .05       0  4657.7      .1       0  4731.7     .05       0
  4925.8     .07       0  4996.9     .07       0  5002.9     .07       0
  5222.8     .05       0
Bank Sta=4989.4,5020.8
XS Rating Curve= 0 ,0
Exp/Cntr=0.3,0.1