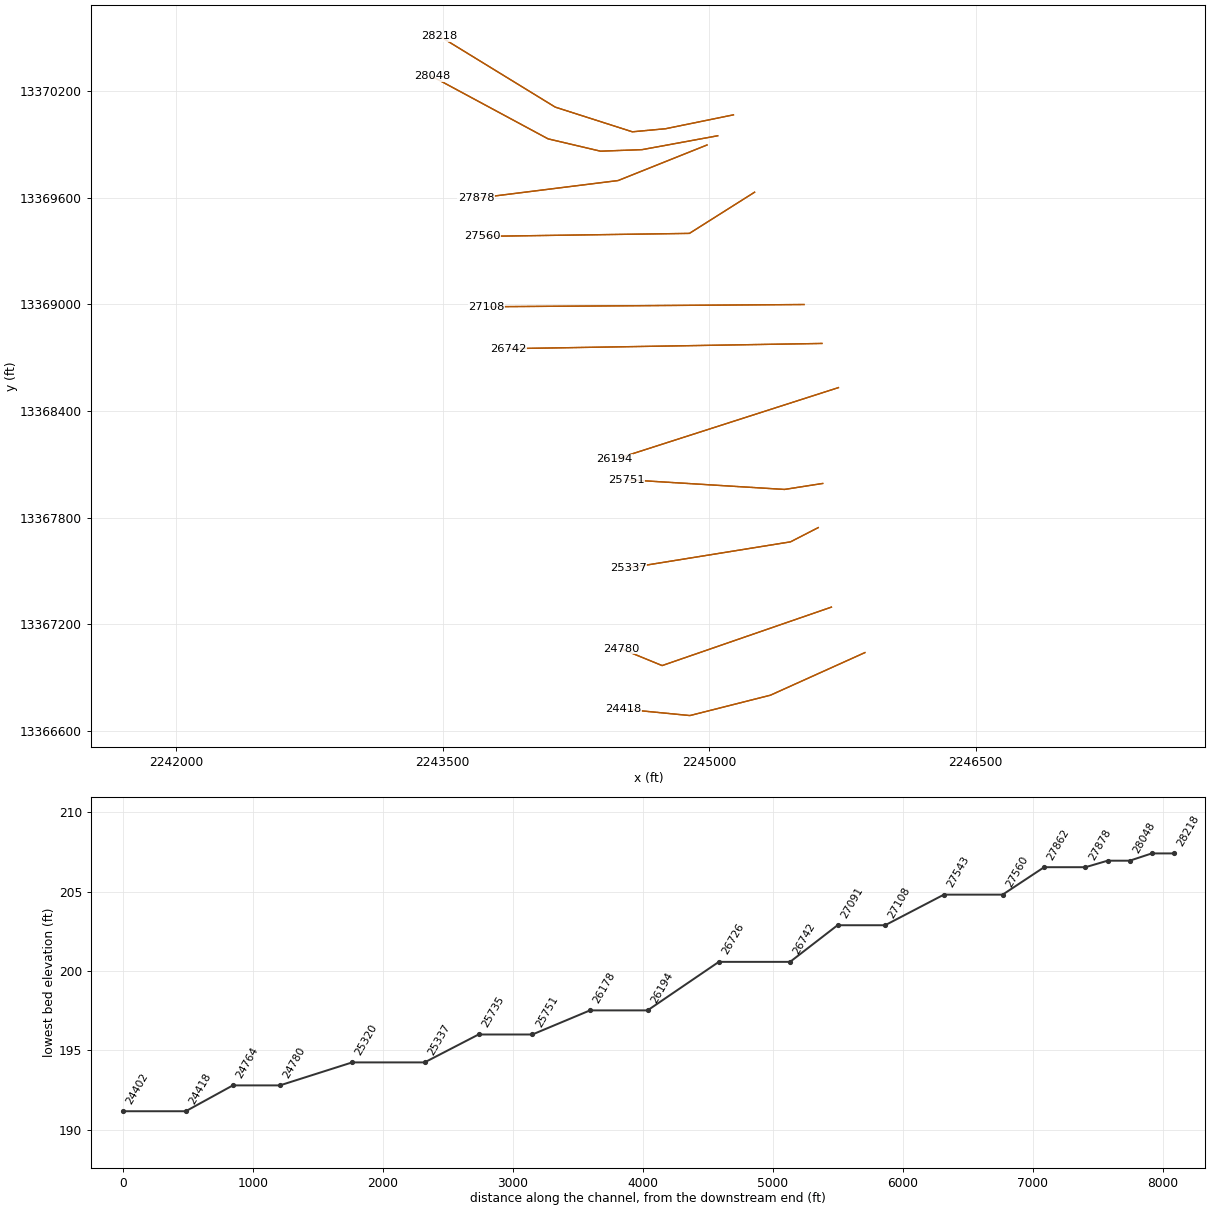
HEC-RAS study ROCK QUARRY BRANCH.prj: ROCK QUARRY BRANCH Base Level Engineering

--- ROCK QUARRY BRANCH.g01 (geometry) --- (continued)

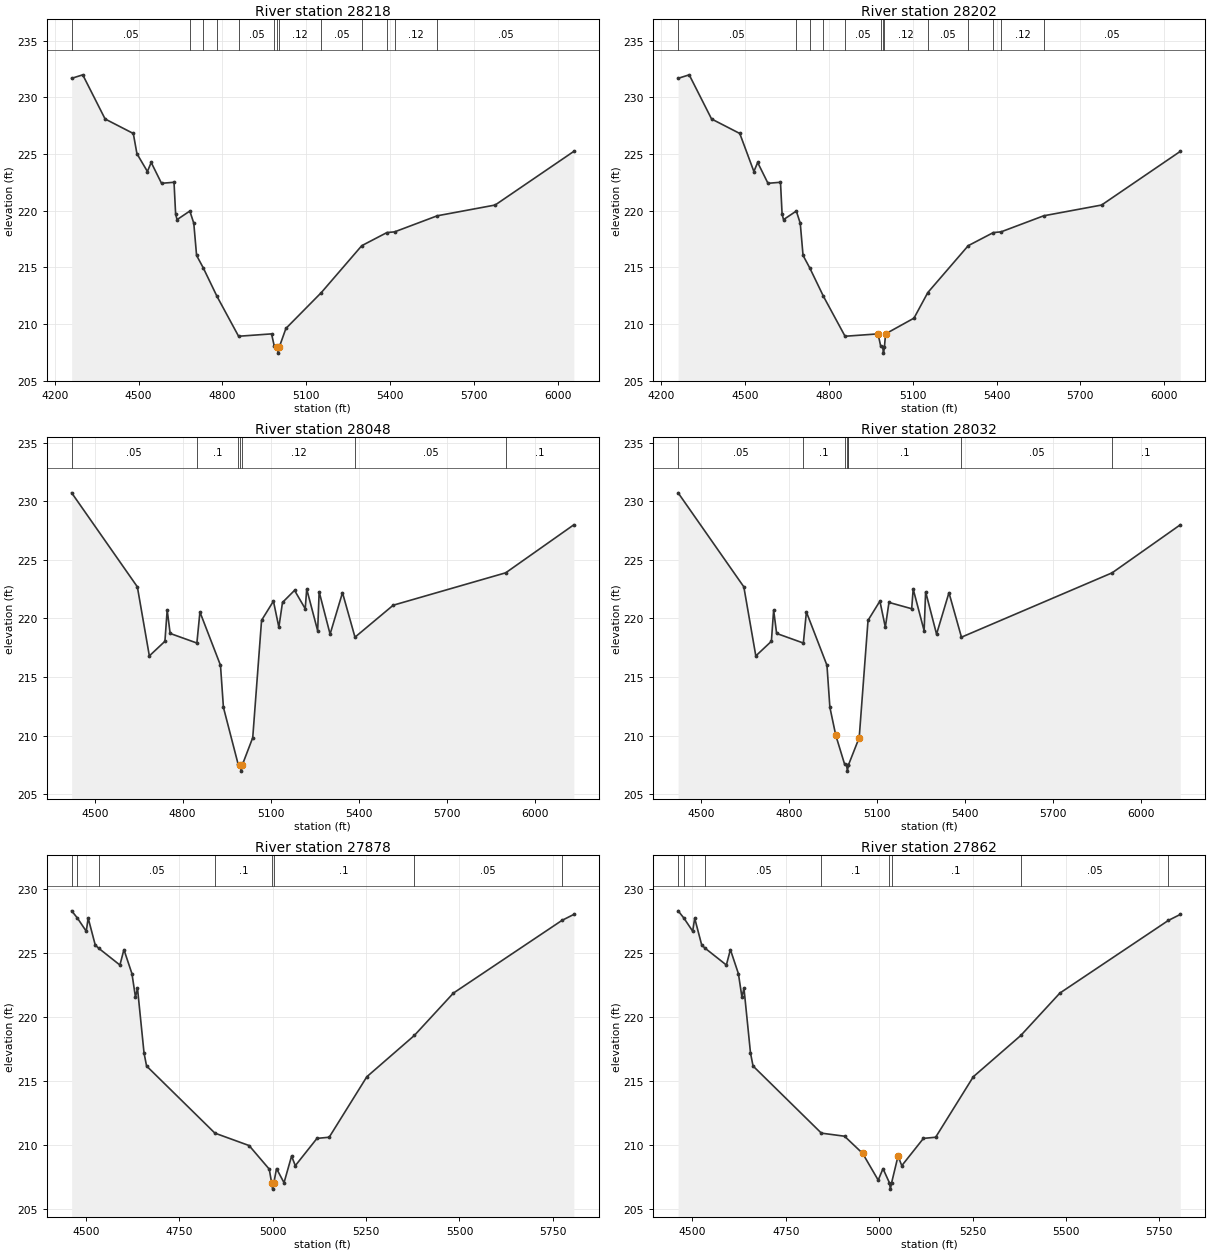
Type RM Length L Ch R = 1 ,28218   ,170,170,170
BEGIN DESCRIPTION:
ROCK QUARRY BRANCH 50.0
END DESCRIPTION:
XS GIS Cut Line= 5
      2245136.58     13370066.53      2244754.59     13369988.39
      2244567.95     13369971.03      2244133.93     13370109.92
      2243482.87     13370509.23
#Sta/Elev= 30
  4260.6  231.69  4300.3     232  4380.3   228.1  4481.2  226.82  4494.2  225.03
  4531.7  223.46  4545.2  224.26  4582.1  222.42  4626.9  222.51  4632.6  219.71
  4637.7  219.21  4683.5  219.97  4697.6  218.89  4707.6  216.05  4731.7  214.94
  4780.7  212.43  4857.9  208.91  4975.9  209.12  4985.6  208.03    4997  207.92
  4999.8  207.42    5003  207.92  5027.2   209.6    5154  212.77  5298.6  216.91
  5388.7  218.07    5416  218.13  5568.7  219.55  5775.8   220.5  6057.4  225.24
#Mann= 13 ,-1 , 0
  4260.6     .05       0  4683.5      .1       0  4731.7     .05       0
  4780.7      .1       0  4857.9     .05       0  4985.6     .12       0
    4997     .07       0    5003     .12       0    5154     .05       0
  5298.6     .12       0  5388.7     .05       0    5416     .12       0
  5568.7     .05       0
Bank Sta=4997,5003
XS Rating Curve= 0 ,0
Exp/Cntr=0.3,0.1

Type RM Length L Ch R = 1 ,28202   ,170,170,170
BEGIN DESCRIPTION:
ROCK QUARRY BRANCH 50.0
END DESCRIPTION:
XS GIS Cut Line= 5
      2245136.58     13370066.53      2244754.59     13369988.39
      2244567.95     13369971.03      2244133.93     13370109.92
      2243482.87     13370509.23
#Sta/Elev= 30
  4260.6  231.69  4300.3     232  4380.3   228.1  4481.2  226.82  4531.7  223.46
  4545.2  224.26  4582.1  222.42  4626.9  222.51  4632.6  219.71  4637.7  219.21
  4683.5  219.97  4697.6  218.89  4707.6  216.05  4731.7  214.94  4780.7  212.43
  4857.9  208.91  4975.9  209.12  4985.6  208.02  4992.7  207.92  4995.4  207.42
  4998.7  207.92  5002.8  209.12  5104.5  210.51    5154  212.77  5298.6  216.91
  5388.7  218.07    5416  218.13  5568.7  219.55  5775.8   220.5  6057.4  225.24
#Mann= 13 ,-1 , 0
  4260.6     .05       0  4683.5      .1       0  4731.7     .05       0
  4780.7      .1       0  4857.9     .05       0  4985.6     .12       0
  4992.7     .07       0  4998.7     .12       0    5154     .05       0
  5298.6     .12       0  5388.7     .05       0    5416     .12       0
  5568.7     .05       0
Bank Sta=4975.9,5002.8
XS Rating Curve= 0 ,0
Exp/Cntr=0.3,0.1

Type RM Length L Ch R = 1 ,28048   ,170,170,170
BEGIN DESCRIPTION:
Mapping XS ce08cd12
END DESCRIPTION:
XS GIS Cut Line= 5
      2245048.12     13369948.87      2244622.77     13369870.74
      2244388.39     13369862.06      2244093.25      13369931.5
      2243439.51     13370283.52
#Sta/Elev= 30
  4421.4  230.73  4645.5   222.7  4686.4   216.8  4739.5  218.05  4747.2  220.72
  4757.3  218.72  4848.5   217.9  4858.9  220.55    4929     216    4939  212.41
  4989.3  207.54    4997  207.46  4999.8  206.96    5003  207.46    5039  209.82
  5069.1  219.84  5109.6  221.48  5128.1  219.25  5140.5  221.37  5181.6   222.4
    5218  220.83  5223.1  222.51  5260.4  218.95  5265.5  222.28  5302.8  218.66
  5345.1   222.2  5387.7   218.4    5518  221.13  5901.8   223.9  6134.1     228
#Mann= 7 ,-1 , 0
  4421.4     .05       0  4848.5      .1       0  4989.3     .12       0
    4997     .07       0    5003     .12       0  5387.7     .05       0
  5901.8      .1       0
Bank Sta=4997,5003
XS Rating Curve= 0 ,0
Exp/Cntr=0.3,0.1

Type RM Length L Ch R = 1 ,28032   ,170,170,170
BEGIN DESCRIPTION:
Mapping XS ce08cd12
END DESCRIPTION:
XS GIS Cut Line= 5
      2245048.12     13369948.87      2244622.77     13369870.74
      2244388.39     13369862.06      2244093.25      13369931.5
      2243439.51     13370283.52
#Sta/Elev= 30
  4421.4  230.73  4645.5   222.7  4686.4   216.8  4739.5  218.05  4747.2  220.72
  4757.3  218.72  4848.5   217.9  4858.9  220.55    4929     216    4939  212.41
    4959  210.03  4989.3  207.54    4996  207.46  4998.8  206.96    5002  207.46
  5002.4  207.49    5039  209.82  5069.1  219.84  5109.6  221.48  5128.1  219.25
  5140.5  221.37    5218  220.83  5223.1  222.51  5260.4  218.95  5265.5  222.28
  5302.8  218.66  5345.1   222.2  5387.7   218.4  5901.8   223.9  6134.1     228
#Mann= 8 ,-1 , 0
  4421.4     .05       0  4848.5      .1       0  4989.3     .12       0
    4996     .07       0    5002     .12       0  5002.4      .1       0
  5387.7     .05       0  5901.8      .1       0
Bank Sta=4959,5039
XS Rating Curve= 0 ,0
Exp/Cntr=0.3,0.1

Type RM Length L Ch R = 1 ,27878   ,318,318,318
BEGIN DESCRIPTION:
ROCK QUARRY BRANCH 49.0
END DESCRIPTION:
XS GIS Cut Line= 3
      2244987.69     13369896.84      2244487.72     13369696.85
      2243687.73     13369596.86
#Sta/Elev= 30
  4461.6  228.27  4476.9  227.71  4500.6  226.68    4506  227.69  4524.8   225.6
  4534.4  225.34  4590.8  224.04  4601.6  225.24  4623.1  223.36  4632.5  221.53
  4637.9  222.23  4655.4  217.18  4662.2  216.16  4845.2  210.92  4936.8  209.95
  4990.7  208.11    4997  207.05  4999.8  206.55    5003  207.05  5010.2  208.15
  5030.3  207.05  5050.5  209.13  5060.5  208.38  5118.5  210.51  5151.2   210.6
    5252  215.32  5379.1  218.54  5483.8  221.85  5774.3  227.52  5806.3  227.99
#Mann= 8 ,-1 , 0
  4461.6     .05       0  4476.9      .1       0  4534.4     .05       0
  4845.2      .1       0    4997     .07       0    5003      .1       0
  5379.1     .05       0  5774.3      .1       0
Bank Sta=4997,5003
XS Rating Curve= 0 ,0
Exp/Cntr=0.3,0.1

Type RM Length L Ch R = 1 ,27862   ,319,319,319
BEGIN DESCRIPTION:
ROCK QUARRY BRANCH 49.0
END DESCRIPTION:
XS GIS Cut Line= 3
      2244987.69     13369896.84      2244487.72     13369696.85
      2243687.73     13369596.86
#Sta/Elev= 30
  4461.6  228.27  4476.9  227.71  4500.6  226.68    4506  227.69  4524.8   225.6
  4534.4  225.34  4590.8  224.04  4601.6  225.24  4623.1  223.36  4632.5  221.53
  4637.9  222.23  4655.4  217.18  4662.2  216.16  4845.2  210.92  4907.2  210.68
  4955.7  209.34  4997.4  207.25  5010.2  208.15  5027.3  207.05  5030.1  206.55
  5033.3  207.05  5050.5  209.13  5060.5  208.38  5118.5  210.51  5151.2   210.6
    5252  215.32  5379.1  218.54  5483.8  221.85  5774.3  227.52  5806.3  227.99
#Mann= 8 ,-1 , 0
  4461.6     .05       0  4476.9      .1       0  4534.4     .05       0
  4845.2      .1       0  5027.3     .07       0  5033.3      .1       0
  5379.1     .05       0  5774.3      .1       0
Bank Sta=4955.7,5050.5
XS Rating Curve= 0 ,0
Exp/Cntr=0.3,0.1

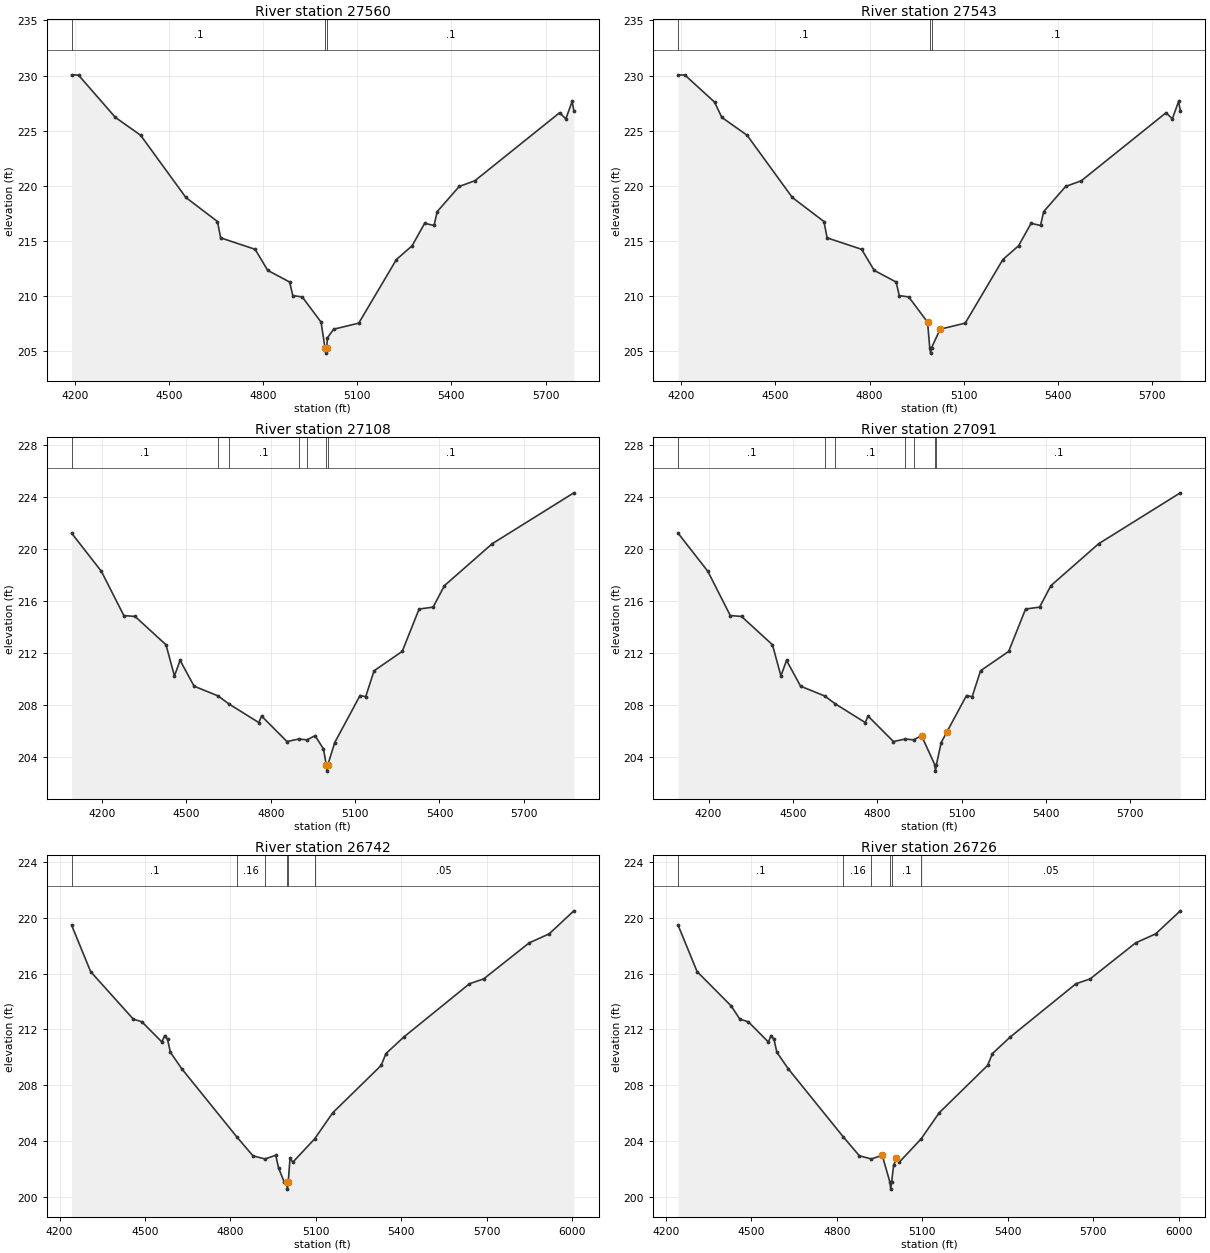
Type RM Length L Ch R = 1 ,27560   ,452,452,452
BEGIN DESCRIPTION:
ROCK QUARRY BRANCH 48.0
END DESCRIPTION:
XS GIS Cut Line= 3
      2245255.35     13369631.21      2244888.89     13369399.54
      2243722.36     13369382.69
#Sta/Elev= 30
  4189.9  230.07    4212  230.04  4329.1  226.21  4409.6  224.59  4553.9  218.94
  4654.6  216.76  4664.6  215.28  4774.6  214.24  4814.6  212.33  4884.6  211.27
  4894.6  210.04  4924.7  209.92  4984.7  207.63    4997  205.32  4999.8  204.82
    5003  205.32  5004.7   206.2  5024.7  206.99  5104.7  207.54  5224.7  213.31
  5274.7  214.56  5314.7   216.6  5344.7   216.4  5354.7  217.66  5424.7  219.94
  5474.7  220.46  5744.7  226.63  5764.7  226.08  5784.7  227.66  5790.1  226.83
#Mann= 3 ,-1 , 0
  4189.9      .1       0    4997     .07       0    5003      .1       0
Bank Sta=4997,5003
XS Rating Curve= 0 ,0
Exp/Cntr=0.3,0.1

Type RM Length L Ch R = 1 ,27543   ,452,452,452
BEGIN DESCRIPTION:
ROCK QUARRY BRANCH 48.0
END DESCRIPTION:
XS GIS Cut Line= 3
      2245255.35     13369631.21      2244888.89     13369399.54
      2243722.36     13369382.69
#Sta/Elev= 30
  4189.9  230.07    4212  230.04  4306.2  227.59  4329.1  226.21  4409.6  224.59
  4553.9  218.94  4654.6  216.76  4664.6  215.28  4774.6  214.24  4814.6  212.33
  4884.6  211.27  4894.6  210.04  4924.7  209.92  4984.7  207.63  4991.7  205.32
  4994.4  204.82  4997.7  205.32  5024.7  206.99  5104.7  207.54  5224.7  213.31
  5274.7  214.56  5314.7   216.6  5344.7   216.4  5354.7  217.66  5424.7  219.94
  5474.7  220.46  5744.7  226.63  5764.7  226.08  5784.7  227.66  5790.1  226.83
#Mann= 3 ,-1 , 0
  4189.9      .1       0  4991.7     .07       0  4997.7      .1       0
Bank Sta=4984.7,5024.7
XS Rating Curve= 0 ,0
Exp/Cntr=0.3,0.1

Type RM Length L Ch R = 1 ,27108   ,366,366,366
BEGIN DESCRIPTION:
ROCK QUARRY BRANCH 47.0
END DESCRIPTION:
XS GIS Cut Line= 2
      2245533.35     13368999.37       2243747.3     13368986.73
#Sta/Elev= 30
  4091.7  221.21  4197.3  218.28  4277.3  214.87  4317.3   214.8  4427.3  212.62
  4457.3  210.22  4477.3  211.42  4527.3  209.43  4612.7  208.68  4650.7  208.07
  4757.3  206.63  4767.3  207.13  4857.4  205.17  4899.7  205.36    4929   205.3
  4957.4  205.62  4987.4   204.6    4997  203.39  4999.8  202.89    5003  203.39
  5027.4  205.09  5117.4  208.71  5137.4  208.62  5167.4  210.62  5267.4  212.11
  5327.4  215.37  5377.4  215.52  5417.4  217.17  5587.4   220.4  5877.8  224.32
#Mann= 7 ,-1 , 0
  4091.7      .1       0  4612.7     .16       0  4650.7      .1       0
  4899.7     .16       0    4929      .1       0    4997     .07       0
    5003      .1       0
Bank Sta=4997,5003
XS Rating Curve= 0 ,0
Exp/Cntr=0.3,0.1

Type RM Length L Ch R = 1 ,27091   ,365,365,365
BEGIN DESCRIPTION:
ROCK QUARRY BRANCH 47.0
END DESCRIPTION:
XS GIS Cut Line= 2
      2245533.35     13368999.37       2243747.3     13368986.73
#Sta/Elev= 30
  4091.7  221.21  4197.3  218.28  4277.3  214.87  4317.3   214.8  4427.3  212.62
  4457.3  210.22  4477.3  211.42  4527.3  209.43  4612.7  208.68  4650.7  208.07
  4757.3  206.63  4767.3  207.13  4857.4  205.17  4899.7  205.36    4929   205.3
  4957.4  205.62  5004.4  203.39  5007.1  202.89  5010.4  203.39  5027.4  205.09
  5047.4   205.9  5117.4  208.71  5137.4  208.62  5167.4  210.62  5267.4  212.11
  5327.4  215.37  5377.4  215.52  5417.4  217.17  5587.4   220.4  5877.8  224.32
#Mann= 7 ,-1 , 0
  4091.7      .1       0  4612.7     .16       0  4650.7      .1       0
  4899.7     .16       0    4929      .1       0  5004.4     .07       0
  5010.4      .1       0
Bank Sta=4957.4,5047.4
XS Rating Curve= 0 ,0
Exp/Cntr=0.3,0.1

Type RM Length L Ch R = 1 ,26742   ,548,548,548
BEGIN DESCRIPTION:
ROCK QUARRY BRANCH 46.0
END DESCRIPTION:
XS GIS Cut Line= 2
      2245634.43     13368780.33      2243871.07     13368750.87
#Sta/Elev= 30
  4242.4  219.46  4309.1  216.14  4459.1  212.74  4489.1  212.55  4559.2  211.11
  4569.2  211.57  4579.2  211.29  4589.2  210.37  4629.2  209.19  4823.1   204.3
  4879.2  202.96  4921.3  202.74  4959.2     203  4969.2  202.08  4989.2  201.08
    4997  201.08  4999.8  200.58    5003  201.08  5009.2  202.79  5019.2  202.51
  5095.5  204.17  5159.2  206.04  5329.3  209.43  5346.2  210.28  5409.3  211.47
  5639.3  215.27  5689.3  215.62  5849.3   218.2  5919.3  218.84    6006  220.49
#Mann= 6 ,-1 , 0
  4242.4      .1       0  4823.1     .16       0  4921.3      .1       0
    4997     .07       0    5003      .1       0  5095.5     .05       0
Bank Sta=4997,5003
XS Rating Curve= 0 ,0
Exp/Cntr=0.3,0.1

Type RM Length L Ch R = 1 ,26726   ,548,548,548
BEGIN DESCRIPTION:
ROCK QUARRY BRANCH 46.0
END DESCRIPTION:
XS GIS Cut Line= 2
      2245634.43     13368780.33      2243871.07     13368750.87
#Sta/Elev= 30
  4242.4  219.46  4309.1  216.14  4429.1  213.68  4459.1  212.74  4489.1  212.55
  4559.2  211.11  4569.2  211.57  4579.2  211.29  4589.2  210.37  4629.2  209.19
  4823.1   204.3  4879.2  202.96  4921.3  202.74  4959.2     203  4986.2  201.08
    4989  200.58  4992.2  201.08  4999.2  202.29  5009.2  202.79  5019.2  202.51
  5095.5  204.17  5159.2  206.04  5329.3  209.43  5346.2  210.28  5409.3  211.47
  5639.3  215.27  5689.3  215.62  5849.3   218.2  5919.3  218.84    6006  220.49
#Mann= 6 ,-1 , 0
  4242.4      .1       0  4823.1     .16       0  4921.3      .1       0
  4986.2     .07       0  4992.2      .1       0  5095.5     .05       0
Bank Sta=4959.2,5009.2
XS Rating Curve= 0 ,0
Exp/Cntr=0.3,0.1

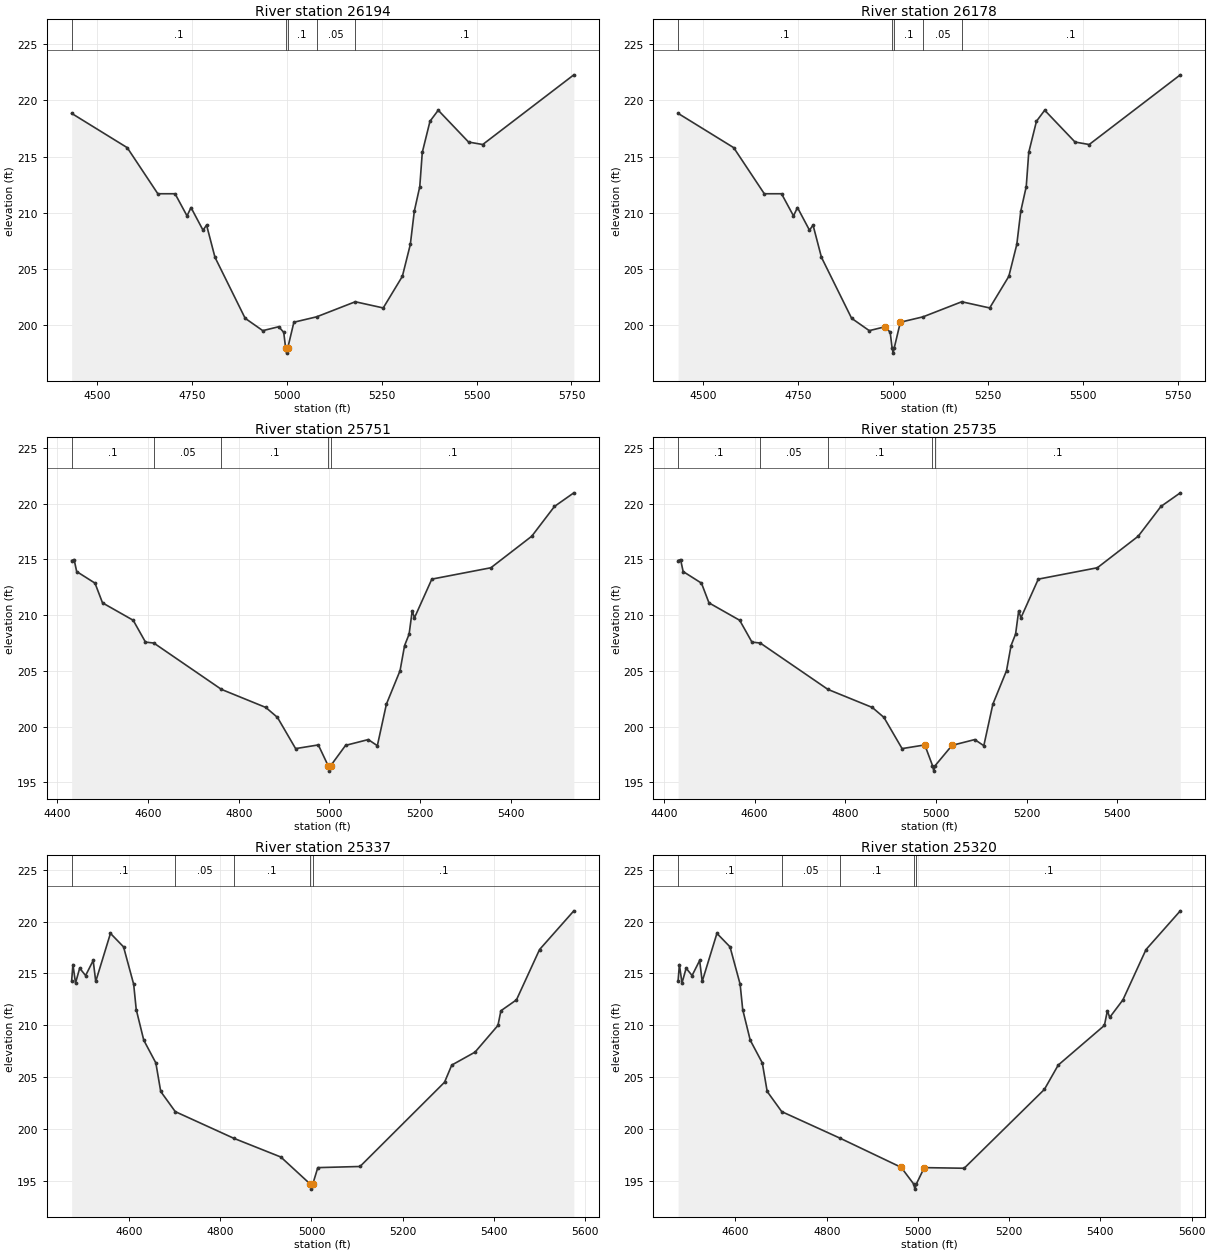
Type RM Length L Ch R = 1 ,26194   ,443,443,443
BEGIN DESCRIPTION:
ROCK QUARRY BRANCH 45.0
END DESCRIPTION:
XS GIS Cut Line= 2
      2245727.11     13368531.79      2244467.64     13368127.41
#Sta/Elev= 30
  4433.5  218.85  4579.9   215.8  4660.5   211.7  4705.9   211.7  4737.4  209.73
  4747.9  210.47  4779.5  208.46  4788.9  208.91    4811  206.05  4890.5  200.62
    4937  199.52    4979  199.87  4992.1  199.37    4997  198.02  4999.8  197.52
    5003  198.02  5018.9  200.27  5078.8  200.75  5180.6  202.09  5254.2  201.54
  5304.6  204.35  5325.6  207.19  5336.1  210.15  5350.5  212.34  5357.1  215.38
  5377.4  218.15  5399.1  219.13    5479   216.3  5516.3  216.08  5756.3  222.28
#Mann= 5 ,-1 , 0
  4433.5      .1       0    4997     .07       0    5003      .1       0
  5078.8     .05       0  5180.6      .1       0
Bank Sta=4997,5003
XS Rating Curve= 0 ,0
Exp/Cntr=0.3,0.1

Type RM Length L Ch R = 1 ,26178   ,443,443,443
BEGIN DESCRIPTION:
ROCK QUARRY BRANCH 45.0
END DESCRIPTION:
XS GIS Cut Line= 2
      2245727.11     13368531.79      2244467.64     13368127.41
#Sta/Elev= 30
  4433.5  218.85  4579.9   215.8  4660.5   211.7  4705.9   211.7  4737.4  209.73
  4747.9  210.47  4779.5  208.46  4788.9  208.91    4811  206.05  4890.5  200.62
    4937  199.52    4979  199.87  4992.1  199.37    4997  198.02  4999.8  197.52
    5003  198.02  5018.9  200.27  5078.8  200.75  5180.6  202.09  5254.2  201.54
  5304.6  204.35  5325.6  207.19  5336.1  210.15  5350.5  212.34  5357.1  215.38
  5377.4  218.15  5399.1  219.13    5479   216.3  5516.3  216.08  5756.3  222.28
#Mann= 5 ,-1 , 0
  4433.5      .1       0    4997     .07       0    5003      .1       0
  5078.8     .05       0  5180.6      .1       0
Bank Sta=4979,5018.9
XS Rating Curve= 0 ,0
Exp/Cntr=0.3,0.1

Type RM Length L Ch R = 1 ,25751   ,414,414,414
BEGIN DESCRIPTION:
ROCK QUARRY BRANCH 44.0
END DESCRIPTION:
XS GIS Cut Line= 3
      2245638.64     13367992.61      2245423.86     13367958.92
      2244535.05     13368013.68
#Sta/Elev= 30
  4431.3  214.89  4436.7  214.98  4442.4   213.9  4482.8  212.86  4499.4  211.09
  4567.1  209.53  4594.2  207.57  4612.5  207.49  4761.8  203.33  4859.7  201.71
  4885.3  200.82  4925.4  198.02  4975.5  198.35    4997   196.5  4999.8     196
    5003   196.5  5035.6  198.31  5085.7  198.83  5105.7  198.28  5125.7  202.01
  5155.8  205.01  5165.8  207.26  5175.8  208.29  5182.6  210.37  5187.6  209.75
  5225.9  213.22  5356.2  214.24  5446.4  217.07  5496.5  219.74  5539.2  220.96
#Mann= 5 ,-1 , 0
  4431.3      .1       0  4612.5     .05       0  4761.8      .1       0
    4997     .07       0    5003      .1       0
Bank Sta=4997,5003
XS Rating Curve= 0 ,0
Exp/Cntr=0.3,0.1

Type RM Length L Ch R = 1 ,25735   ,415,415,415
BEGIN DESCRIPTION:
ROCK QUARRY BRANCH 44.0
END DESCRIPTION:
XS GIS Cut Line= 3
      2245638.64     13367992.61      2245423.86     13367958.92
      2244535.05     13368013.68
#Sta/Elev= 30
  4431.3  214.89  4436.7  214.98  4442.4   213.9  4482.8  212.86  4499.4  211.09
  4567.1  209.53  4594.2  207.57  4612.5  207.49  4761.8  203.33  4859.7  201.71
  4885.3  200.82  4925.4  198.02  4975.5  198.35  4992.5   196.5  4995.3     196
  4998.5   196.5  5035.6  198.31  5085.7  198.83  5105.7  198.28  5125.7  202.01
  5155.8  205.01  5165.8  207.26  5175.8  208.29  5182.6  210.37  5187.6  209.75
  5225.9  213.22  5356.2  214.24  5446.4  217.07  5496.5  219.74  5539.2  220.96
#Mann= 5 ,-1 , 0
  4431.3      .1       0  4612.5     .05       0  4761.8      .1       0
  4992.5     .07       0  4998.5      .1       0
Bank Sta=4975.5,5035.6
XS Rating Curve= 0 ,0
Exp/Cntr=0.3,0.1

Type RM Length L Ch R = 1 ,25337   ,557,557,557
BEGIN DESCRIPTION:
ROCK QUARRY BRANCH 43.0
END DESCRIPTION:
XS GIS Cut Line= 3
      2245613.42     13367744.09      2245457.55     13367664.06
      2244543.48     13367516.62
#Sta/Elev= 30
  4474.2  214.29    4477  215.86  4482.7  214.08  4491.8  215.51  4504.8   214.8
  4521.4  216.25    4527  214.23  4559.3  218.86    4588  217.56  4610.2  213.96
  4615.8  211.53  4632.3  208.58  4658.8  206.39  4669.5  203.64  4701.4   201.7
  4829.9  199.13  4932.9  197.33    4997  194.74  4999.8  194.24    5003  194.74
  5013.9  196.31  5106.5  196.42  5291.8  204.53  5307.6  206.18  5358.7  207.43
  5408.9     210  5415.4  211.41  5449.5  212.46  5500.1   217.3  5575.3  221.03
#Mann= 5 ,-1 , 0
  4474.2      .1       0  4701.4     .05       0  4829.9      .1       0
    4997     .07       0    5003      .1       0
Bank Sta=4997,5003
XS Rating Curve= 0 ,0
Exp/Cntr=0.3,0.1

Type RM Length L Ch R = 1 ,25320   ,556,556,556
BEGIN DESCRIPTION:
ROCK QUARRY BRANCH 43.0
END DESCRIPTION:
XS GIS Cut Line= 3
      2245613.42     13367744.09      2245457.55     13367664.06
      2244543.48     13367516.62
#Sta/Elev= 30
  4474.2  214.29    4477  215.86  4482.7  214.08  4491.8  215.51  4504.8   214.8
  4521.4  216.25    4527  214.23  4559.3  218.86    4588  217.56  4610.2  213.96
  4615.8  211.53  4632.3  208.58  4658.8  206.39  4669.5  203.64  4701.4   201.7
  4829.9  199.13  4963.2  196.34  4990.6  194.74  4993.4  194.24  4996.6  194.74
  5013.9  196.31  5101.4  196.25  5277.3  203.84  5307.6  206.18  5408.9     210
  5415.4  211.41  5420.5  210.77  5449.5  212.46  5500.1   217.3  5575.3  221.03
#Mann= 5 ,-1 , 0
  4474.2      .1       0  4701.4     .05       0  4829.9      .1       0
  4990.6     .07       0  4996.6      .1       0
Bank Sta=4963.2,5013.9
XS Rating Curve= 0 ,0
Exp/Cntr=0.3,0.1

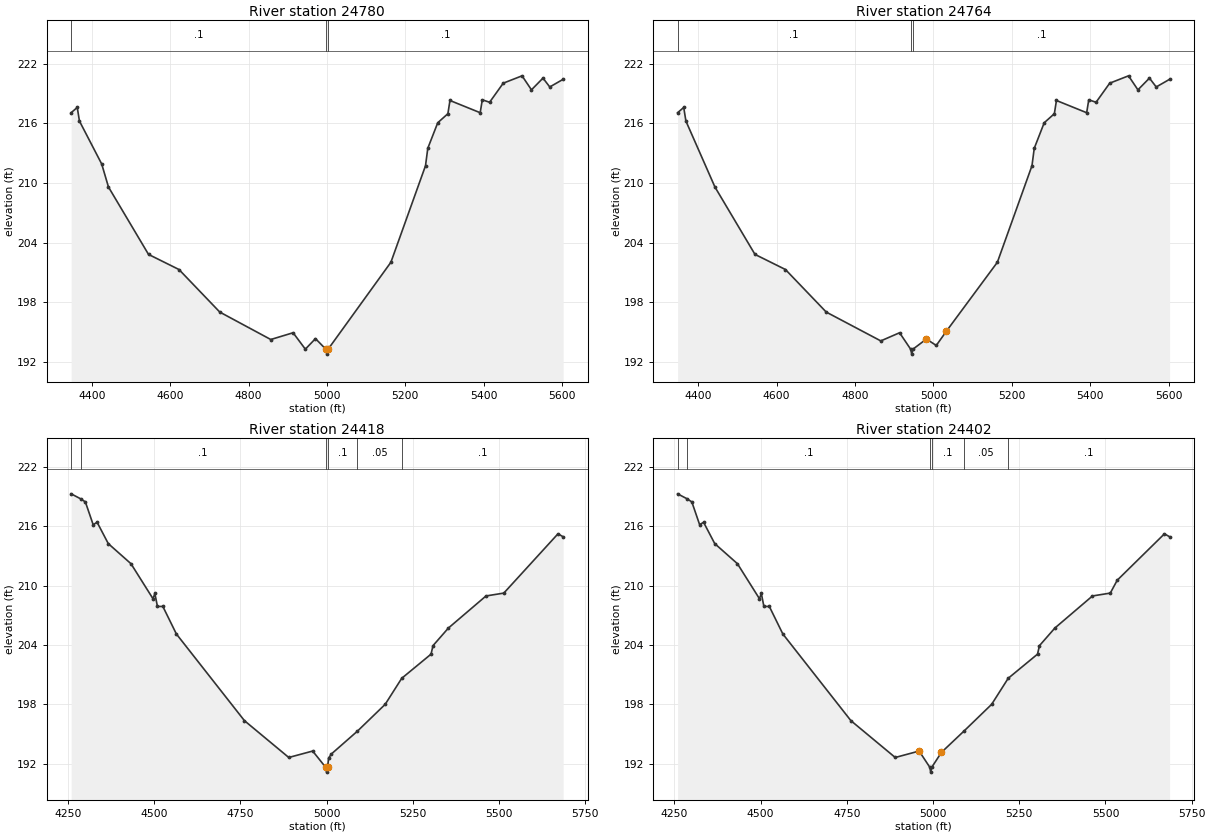
Type RM Length L Ch R = 1 ,24780   ,362,362,362
BEGIN DESCRIPTION:
ROCK QUARRY BRANCH 42.0
END DESCRIPTION:
XS GIS Cut Line= 4
      2245687.74     13367296.86      2244886.37     13367020.04
      2244735.33     13366967.96      2244506.17      13367061.7
#Sta/Elev= 30
  4347.3  217.07  4362.9   217.6  4368.5  216.23  4425.3  211.91  4442.5   209.6
  4544.7  202.82  4622.4   201.3  4726.5  197.02  4856.6  194.26  4913.6  194.94
  4944.8  193.29  4970.7  194.35    4997  193.29  4999.8  192.79    5003  193.29
  5163.1  202.03  5251.4  211.74  5257.2  213.49  5282.6  216.06  5308.5  216.97
  5313.8   218.3  5390.9  217.07  5396.3  218.37  5414.9  218.12  5449.7  220.04
  5497.7  220.78  5521.7  219.37  5551.1  220.55  5568.4  219.66  5602.5  220.43
#Mann= 3 ,-1 , 0
  4347.3      .1       0    4997     .07       0    5003      .1       0
Bank Sta=4997,5003
XS Rating Curve= 0 ,0
Exp/Cntr=0.3,0.1

Type RM Length L Ch R = 1 ,24764   ,362,362,362
BEGIN DESCRIPTION:
ROCK QUARRY BRANCH 42.0
END DESCRIPTION:
XS GIS Cut Line= 4
      2245687.74     13367296.86      2244886.37     13367020.04
      2244735.33     13366967.96      2244506.17      13367061.7
#Sta/Elev= 30
  4347.3  217.07  4362.9   217.6  4368.5  216.23  4442.5   209.6  4544.7  202.82
  4622.4   201.3  4726.5  197.02  4865.7  194.12  4913.6  194.94  4941.8  193.29
  4944.6  192.79  4947.8  193.29  4982.1  194.31  5007.2  193.66  5033.1   195.1
  5163.1  202.03  5251.4  211.74  5257.2  213.49  5282.6  216.06  5308.5  216.97
  5313.8   218.3  5390.9  217.07  5396.3  218.37  5414.9  218.12  5449.7  220.04
  5497.7  220.78  5521.7  219.37  5551.1  220.55  5568.4  219.66  5602.5  220.43
#Mann= 3 ,-1 , 0
  4347.3      .1       0  4941.8     .07       0  4947.8      .1       0
Bank Sta=4982.1,5033.1
XS Rating Curve= 0 ,0
Exp/Cntr=0.3,0.1

Type RM Length L Ch R = 1 ,24418   ,484,484,484
BEGIN DESCRIPTION:
ROCK QUARRY BRANCH 41.0
END DESCRIPTION:
XS GIS Cut Line= 4
      2245875.92     13367040.86       2245344.7     13366801.29
      2244891.58     13366686.71      2244516.57     13366723.17
#Sta/Elev= 30
  4259.1  219.28    4287  218.77  4300.4  218.46  4322.9  216.17  4334.5   216.4
  4366.8  214.25  4432.6  212.22  4496.5  208.68  4501.9  209.21  4509.4   207.9
  4525.1   207.9  4564.3  205.12  4761.7  196.36  4890.3  192.64  4959.6  193.29
    4997  191.66  4999.8  191.16    5003  191.66  5005.8  192.58  5014.1     193
  5089.4   195.3  5169.9  198.01  5217.9  200.64  5302.9  203.08  5308.6  203.94
  5353.3  205.72  5462.3  208.96    5514  209.25  5671.1  215.24    5686  214.94
#Mann= 6 ,-1 , 0
  4259.1     .05       0    4287      .1       0    4997     .07       0
    5003      .1       0  5089.4     .05       0  5217.9      .1       0
Bank Sta=4997,5003
XS Rating Curve= 0 ,0
Exp/Cntr=0.3,0.1

Type RM Length L Ch R = 1 ,24402   ,484,484,484
BEGIN DESCRIPTION:
ROCK QUARRY BRANCH 41.0
END DESCRIPTION:
XS GIS Cut Line= 4
      2245875.92     13367040.86       2245344.7     13366801.29
      2244891.58     13366686.71      2244516.57     13366723.17
#Sta/Elev= 30
  4259.1  219.28    4287  218.77  4300.4  218.46  4322.9  216.17  4334.5   216.4
  4366.8  214.25  4432.6  212.22  4496.5  208.68  4501.9  209.21  4509.4   207.9
  4525.1   207.9  4564.3  205.12  4761.7  196.36  4890.3  192.64  4959.6  193.29
  4990.4  191.66  4993.2  191.16  4996.4  191.66  5024.4  193.16  5089.4   195.3
  5169.9  198.01  5217.9  200.64  5302.9  203.08  5308.6  203.94  5353.3  205.72
  5462.3  208.96    5514  209.25  5534.1  210.55  5671.1  215.24    5686  214.94
#Mann= 6 ,-1 , 0
  4259.1     .05       0    4287      .1       0  4990.4     .07       0
  4996.4      .1       0  5089.4     .05       0  5217.9      .1       0
Bank Sta=4959.6,5024.4
XS Rating Curve= 0 ,0
Exp/Cntr=0.3,0.1