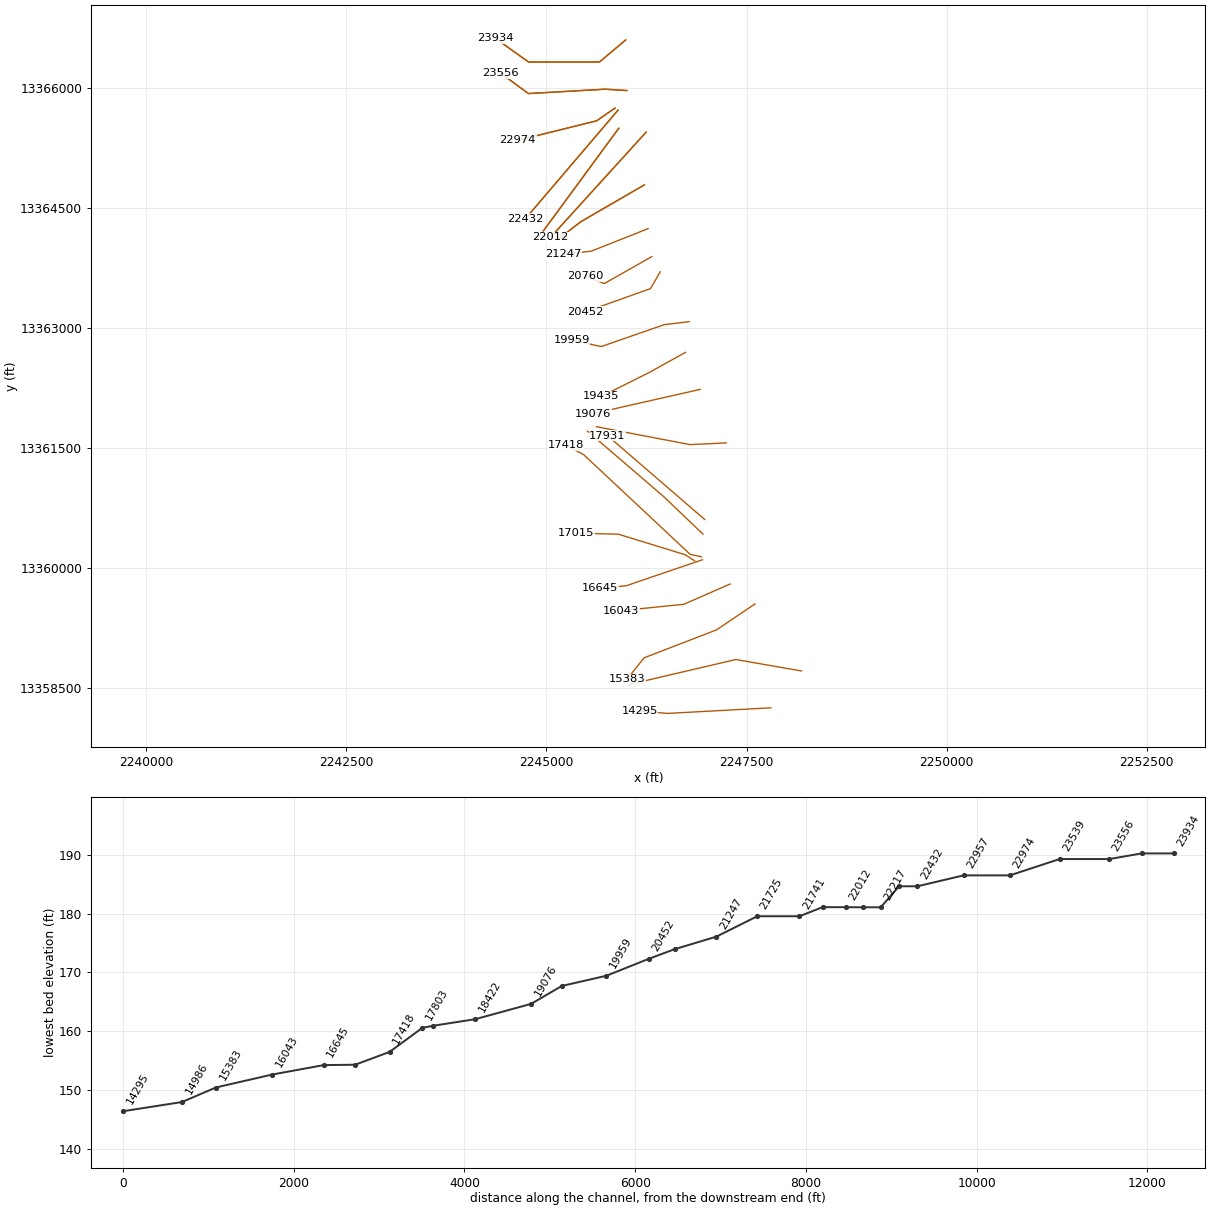
HEC-RAS study ROCK QUARRY BRANCH.prj: ROCK QUARRY BRANCH Base Level Engineering

--- ROCK QUARRY BRANCH.g01 (geometry) --- (continued)

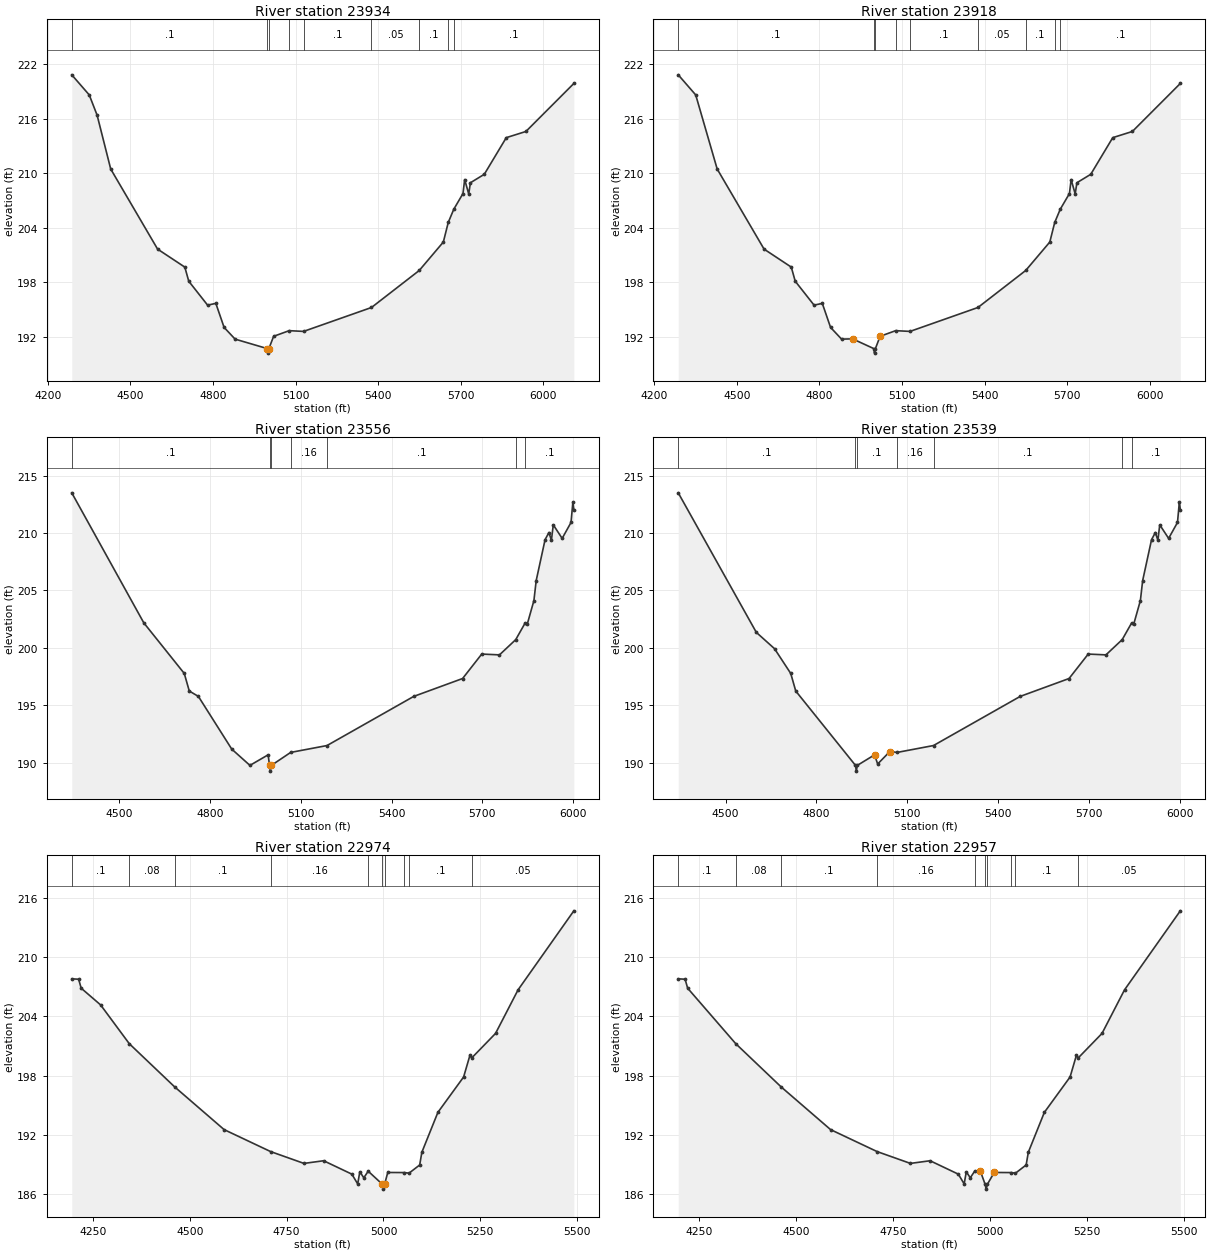
Type RM Length L Ch R = 1 ,23934   ,378,378,378
BEGIN DESCRIPTION:
ROCK QUARRY BRANCH 40.0
END DESCRIPTION:
XS GIS Cut Line= 4
      2245990.53     13366603.37      2245662.41     13366327.33
      2244776.99     13366327.33      2244361.48     13366623.38
#Sta/Elev= 30
  4286.7  220.82  4350.2  218.61  4378.8  216.38  4428.2  210.46  4598.6  201.65
  4697.5  199.67  4711.8  198.12  4780.2  195.49  4810.2  195.68  4840.2  193.04
  4880.2  191.75    4997  190.71  4999.8  190.21    5003  190.71  5020.2  192.06
  5076.7  192.68  5129.1   192.6  5375.8  195.23  5549.3   199.3  5636.9  202.43
  5654.7  204.58  5674.9  206.04  5708.2  207.76  5714.4   209.3  5729.1  207.72
  5735.3  208.95  5785.7  209.88  5865.6  213.91  5936.9  214.59  6111.1  219.87
#Mann= 9 ,-1 , 0
  4286.7      .1       0    4997     .07       0    5003      .1       0
  5076.7     .16       0  5129.1      .1       0  5375.8     .05       0
  5549.3      .1       0  5654.7     .05       0  5674.9      .1       0
Bank Sta=4997,5003
XS Rating Curve= 0 ,0
Exp/Cntr=0.3,0.1

Type RM Length L Ch R = 1 ,23918   ,379,379,379
BEGIN DESCRIPTION:
ROCK QUARRY BRANCH 40.0
END DESCRIPTION:
XS GIS Cut Line= 4
      2245990.53     13366603.37      2245662.41     13366327.33
      2244776.99     13366327.33      2244361.48     13366623.38
#Sta/Elev= 30
  4286.7  220.82  4350.2  218.61  4428.2  210.46  4598.6  201.65  4697.5  199.67
  4711.8  198.12  4780.2  195.49  4810.2  195.68  4840.2  193.04  4880.2  191.75
  4920.2  191.78  4997.2  190.71  4999.9  190.21  5003.2  190.71  5020.2  192.06
  5076.7  192.68  5129.1   192.6  5375.8  195.23  5549.3   199.3  5636.9  202.43
  5654.7  204.58  5674.9  206.04  5708.2  207.76  5714.4   209.3  5729.1  207.72
  5735.3  208.95  5785.7  209.88  5865.6  213.91  5936.9  214.59  6111.1  219.87
#Mann= 9 ,-1 , 0
  4286.7      .1       0  4997.2     .07       0  5003.2      .1       0
  5076.7     .16       0  5129.1      .1       0  5375.8     .05       0
  5549.3      .1       0  5654.7     .05       0  5674.9      .1       0
Bank Sta=4920.2,5020.2
XS Rating Curve= 0 ,0
Exp/Cntr=0.3,0.1

Type RM Length L Ch R = 1 ,23556   ,582,582,582
BEGIN DESCRIPTION:
ROCK QUARRY BRANCH 39.0
END DESCRIPTION:
XS GIS Cut Line= 4
      2246005.12      13365970.7      2245735.57     13365987.55
      2244775.16     13365932.79      2244431.24     13366184.43
#Sta/Elev= 30
  4343.8   213.5  4581.7  202.17  4715.4  197.76  4731.9  196.23    4762  195.76
  4872.1  191.17  4932.2  189.75  4992.3  190.67    4997  189.75  4999.8  189.25
    5003  189.75  5066.7  190.88  5186.9  191.48  5473.1  195.76  5634.6  197.32
  5697.8  199.45  5756.4  199.38  5810.1  200.71    5841  202.15  5848.4  202.08
  5870.1  204.11  5877.7  205.86    5907  209.42  5919.6  210.04  5927.9  209.37
  5934.1  210.71  5963.4  209.53  5992.7  210.92  5998.9  212.72    6002  212.04
#Mann= 7 ,-1 , 0
  4343.8      .1       0    4997     .07       0    5003      .1       0
  5066.7     .16       0  5186.9      .1       0  5810.1     .05       0
    5841      .1       0
Bank Sta=4997,5003
XS Rating Curve= 0 ,0
Exp/Cntr=0.3,0.1

Type RM Length L Ch R = 1 ,23539   ,582,582,582
BEGIN DESCRIPTION:
ROCK QUARRY BRANCH 39.0
END DESCRIPTION:
XS GIS Cut Line= 4
      2246005.12      13365970.7      2245735.57     13365987.55
      2244775.16     13365932.79      2244431.24     13366184.43
#Sta/Elev= 30
  4343.8   213.5  4601.7  201.34  4661.8  199.92  4715.4  197.76  4731.9  196.23
  4929.2  189.75    4932  189.25  4935.2  189.75  4992.3  190.67  5002.4  189.87
  5042.4  190.95  5066.7  190.88  5186.9  191.48  5473.1  195.76  5634.6  197.32
  5697.8  199.45  5756.4  199.38  5810.1  200.71    5841  202.15  5848.4  202.08
  5870.1  204.11  5877.7  205.86    5907  209.42  5919.6  210.04  5927.9  209.37
  5934.1  210.71  5963.4  209.53  5992.7  210.92  5998.9  212.72    6002  212.04
#Mann= 7 ,-1 , 0
  4343.8      .1       0  4929.2     .07       0  4935.2      .1       0
  5066.7     .16       0  5186.9      .1       0  5810.1     .05       0
    5841      .1       0
Bank Sta=4992.3,5042.4
XS Rating Curve= 0 ,0
Exp/Cntr=0.3,0.1

Type RM Length L Ch R = 1 ,22974   ,542,542,542
BEGIN DESCRIPTION:
ROCK QUARRY BRANCH 38.0
END DESCRIPTION:
XS GIS Cut Line= 3
      2245857.73     13365751.66      2245626.05     13365591.59
      2244641.54     13365347.56
#Sta/Elev= 30
  4195.5  207.82  4213.2  207.78  4219.8  206.87    4270  205.17  4343.9  201.24
  4460.9  196.86  4588.7  192.52  4708.8  190.29  4794.8  189.09  4845.6  189.36
  4918.4     188  4933.5  187.01    4939  188.24  4949.3  187.63  4960.6   188.3
    4997  186.98  4999.8  186.48    5003  186.98  5011.1  188.17  5054.3  188.16
    5066   188.1  5093.5  188.93  5099.1  190.22  5140.5  194.27  5206.9  197.86
  5223.2  200.06  5227.8  199.79  5289.3  202.28  5347.4   206.7  5491.4  214.72
#Mann= 10 ,-1 , 0
  4195.5      .1       0  4343.9     .08       0  4460.9      .1       0
  4708.8     .16       0  4960.6      .1       0    4997     .07       0
    5003      .1       0  5054.3     .16       0    5066      .1       0
  5227.8     .05       0
Bank Sta=4997,5003
XS Rating Curve= 0 ,0
Exp/Cntr=0.3,0.1

Type RM Length L Ch R = 1 ,22957   ,541,541,541
BEGIN DESCRIPTION:
ROCK QUARRY BRANCH 38.0
END DESCRIPTION:
XS GIS Cut Line= 3
      2245857.73     13365751.66      2245626.05     13365591.59
      2244641.54     13365347.56
#Sta/Elev= 30
  4195.5  207.82  4213.2  207.78  4219.8  206.87  4343.9  201.24  4460.9  196.86
  4588.7  192.52  4708.8  190.29  4794.8  189.09  4845.6  189.36  4918.4     188
  4933.5  187.01    4939  188.24  4949.3  187.63  4960.6   188.3  4974.9  188.35
  4987.5  186.98  4990.3  186.48  4993.5  186.98  5011.1  188.17  5054.3  188.16
    5066   188.1  5093.5  188.93  5099.1  190.22  5140.5  194.27  5206.9  197.86
  5223.2  200.06  5227.8  199.79  5289.3  202.28  5347.4   206.7  5491.4  214.72
#Mann= 10 ,-1 , 0
  4195.5      .1       0  4343.9     .08       0  4460.9      .1       0
  4708.8     .16       0  4960.6      .1       0  4987.5     .07       0
  4993.5      .1       0  5054.3     .16       0    5066      .1       0
  5227.8     .05       0
Bank Sta=4974.9,5011.1
XS Rating Curve= 0 ,0
Exp/Cntr=0.3,0.1

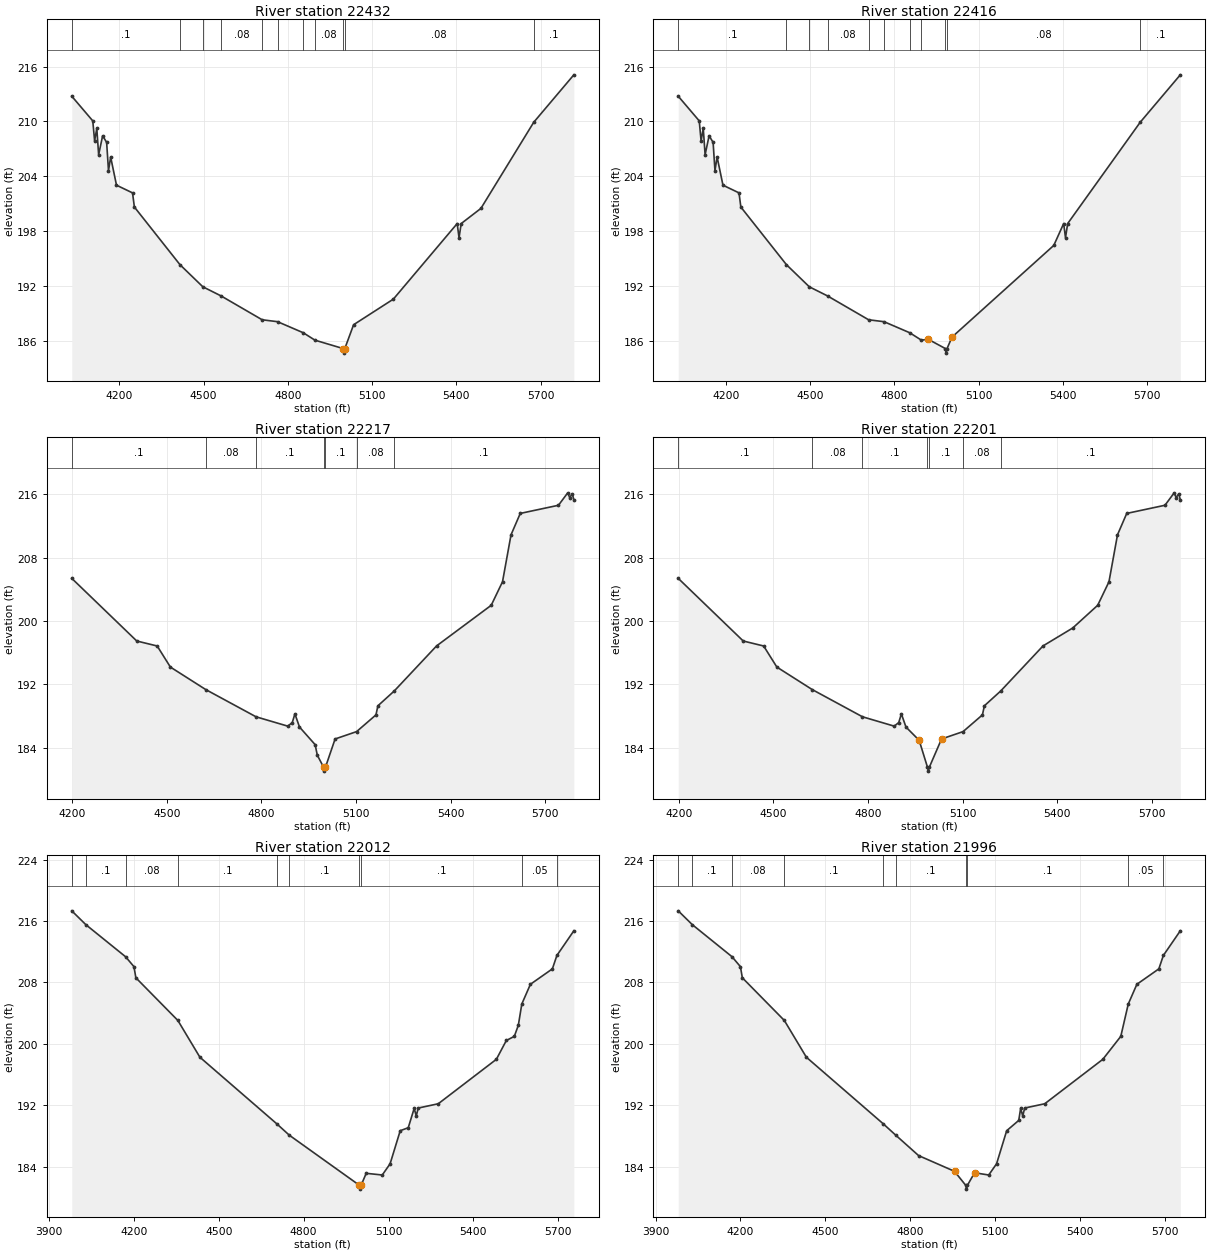
Type RM Length L Ch R = 1 ,22432   ,215,215,215
BEGIN DESCRIPTION:
ROCK QUARRY BRANCH 37.0
END DESCRIPTION:
XS GIS Cut Line= 2
      2245894.35     13365725.14      2244734.61     13364364.01
#Sta/Elev= 30
  4030.5  212.75  4105.3  210.05  4111.9  207.86  4119.6  209.23  4126.2  206.34
  4140.4  208.42  4154.7   207.7  4161.3  204.61    4169  206.09  4189.8  203.01
  4246.9  202.17  4253.5  200.62  4415.9  194.31  4497.3  191.89  4562.3  190.89
  4708.6  188.28  4763.5  188.07    4855  186.86  4896.5  186.05    4997  185.13
  4999.8  184.63    5003  185.13  5034.3  187.74  5175.9  190.54  5403.2  198.81
  5409.8  197.26  5417.5  198.81  5487.7  200.47  5675.9   209.9  5818.7  215.09
#Mann= 11 ,-1 , 0
  4030.5      .1       0  4415.9     .08       0  4497.3      .1       0
  4562.3     .08       0  4708.6      .1       0  4763.5     .08       0
    4855     .16       0  4896.5     .08       0    4997     .07       0
    5003     .08       0  5675.9      .1       0
Bank Sta=4997,5003
XS Rating Curve= 0 ,0
Exp/Cntr=0.3,0.1

Type RM Length L Ch R = 1 ,22416   ,215,215,215
BEGIN DESCRIPTION:
ROCK QUARRY BRANCH 37.0
END DESCRIPTION:
XS GIS Cut Line= 2
      2245894.35     13365725.14      2244734.61     13364364.01
#Sta/Elev= 30
  4030.5  212.75  4105.3  210.05  4111.9  207.86  4119.6  209.23  4126.2  206.34
  4140.4  208.42  4154.7   207.7  4161.3  204.61    4169  206.09  4189.8  203.01
  4246.9  202.17  4253.5  200.62  4415.9  194.31  4497.3  191.89  4562.3  190.89
  4708.6  188.28  4763.5  188.07    4855  186.86  4896.5  186.05  4921.2  186.14
  4981.9  185.13  4984.6  184.63  4987.9  185.13  5005.7  186.39  5368.1  196.42
  5403.2  198.81  5409.8  197.26  5417.5  198.81  5675.9   209.9  5818.7  215.09
#Mann= 11 ,-1 , 0
  4030.5      .1       0  4415.9     .08       0  4497.3      .1       0
  4562.3     .08       0  4708.6      .1       0  4763.5     .08       0
    4855     .16       0  4896.5     .08       0  4981.9     .07       0
  4987.9     .08       0  5675.9      .1       0
Bank Sta=4921.2,5005.7
XS Rating Curve= 0 ,0
Exp/Cntr=0.3,0.1

Type RM Length L Ch R = 1 ,22217   ,205,205,205
BEGIN DESCRIPTION:
ROCK QUARRY BRANCH 36.0
END DESCRIPTION:
XS GIS Cut Line= 2
      2245904.03     13365498.87      2244961.61     13364215.67
#Sta/Elev= 30
  4198.5   205.4  4404.6  197.49  4469.4  196.86  4511.2   194.2  4623.3  191.36
  4782.8  187.92  4883.4  186.74  4897.7  187.19  4906.1  188.29  4920.6  186.63
  4970.3   184.4  4977.1  183.07    4997  181.56  4999.8  181.06    5003  181.56
  5033.5  185.12  5101.7  186.05  5163.1  188.16  5169.3  189.31  5221.1  191.18
  5355.3  196.87  5528.6     202  5564.4  204.97  5591.4   210.9  5620.7   213.6
  5741.9  214.63  5771.2   216.2  5777.4   215.6  5785.8  216.08  5790.6  215.32
#Mann= 7 ,-1 , 0
  4198.5      .1       0  4623.3     .08       0  4782.8      .1       0
    4997     .07       0    5003      .1       0  5101.7     .08       0
  5221.1      .1       0
Bank Sta=4997,5003
XS Rating Curve= 0 ,0
Exp/Cntr=0.3,0.1

Type RM Length L Ch R = 1 ,22201   ,205,205,205
BEGIN DESCRIPTION:
ROCK QUARRY BRANCH 36.0
END DESCRIPTION:
XS GIS Cut Line= 2
      2245904.03     13365498.87      2244961.61     13364215.67
#Sta/Elev= 30
  4198.5   205.4  4404.6  197.49  4469.4  196.86  4511.2   194.2  4623.3  191.36
  4782.8  187.92  4883.4  186.74  4897.7  187.19  4906.1  188.29  4920.6  186.63
  4962.5  184.95  4988.8  181.56  4991.5  181.06  4994.8  181.56  5033.5  185.12
  5101.7  186.05  5163.1  188.16  5169.3  189.31  5221.1  191.18  5355.3  196.87
  5449.4  199.13  5528.6     202  5564.4  204.97  5591.4   210.9  5620.7   213.6
  5741.9  214.63  5771.2   216.2  5777.4   215.6  5785.8  216.08  5790.6  215.32
#Mann= 7 ,-1 , 0
  4198.5      .1       0  4623.3     .08       0  4782.8      .1       0
  4988.8     .07       0  4994.8      .1       0  5101.7     .08       0
  5221.1      .1       0
Bank Sta=4962.5,5033.5
XS Rating Curve= 0 ,0
Exp/Cntr=0.3,0.1

Type RM Length L Ch R = 1 ,22012   ,271,271,271
BEGIN DESCRIPTION:
Mapping XS 3beb9038
END DESCRIPTION:
XS GIS Cut Line= 2
       2246244.9     13365449.76      2245051.99     13364135.39
#Sta/Elev= 30
  3980.1  217.33  4029.8  215.53  4170.3  211.35  4199.9  210.06  4206.7  208.61
  4355.2  203.05  4433.1  198.26  4704.5   189.6    4749  188.11    4997  181.58
  4999.8  181.08    5003  181.58    5021  183.14  5077.8  182.92  5105.5  184.38
  5141.3  188.69  5169.7  189.08  5190.6  191.59  5198.1  190.61  5204.8  191.64
  5275.8   192.2  5481.2  197.99  5516.4  200.44  5544.7  200.98  5558.9  202.43
  5571.1  205.19  5601.5  207.76  5679.2  209.77  5695.2  211.52  5755.1  214.73
#Mann= 10 ,-1 , 0
  3980.1     .05       0  4029.8      .1       0  4170.3     .08       0
  4355.2      .1       0  4704.5     .08       0    4749      .1       0
    4997     .07       0    5003      .1       0  5571.1     .05       0
  5695.2      .1       0
Bank Sta=4997,5003
XS Rating Curve= 0 ,0
Exp/Cntr=0.3,0.1

Type RM Length L Ch R = 1 ,21996   ,271,271,271
BEGIN DESCRIPTION:
Mapping XS 3beb9038
END DESCRIPTION:
XS GIS Cut Line= 2
       2246244.9     13365449.76      2245051.99     13364135.39
#Sta/Elev= 30
  3980.1  217.33  4029.8  215.53  4170.3  211.35  4199.9  210.06  4206.7  208.61
  4355.2  203.05  4433.1  198.26  4704.5   189.6    4749  188.11  4829.8  185.45
  4956.8   183.4  4996.4  181.58  4999.1  181.08  5002.4  181.58  5027.8  183.21
  5077.8  182.92  5105.5  184.38  5141.3  188.69  5183.9  190.03  5190.6  191.59
  5198.1  190.61  5204.8  191.64  5275.8   192.2  5481.2  197.99  5544.7  200.98
  5571.1  205.19  5601.5  207.76  5679.2  209.77  5695.2  211.52  5755.1  214.73
#Mann= 10 ,-1 , 0
  3980.1     .05       0  4029.8      .1       0  4170.3     .08       0
  4355.2      .1       0  4704.5     .08       0    4749      .1       0
  4996.4     .07       0  5002.4      .1       0  5571.1     .05       0
  5695.2      .1       0
Bank Sta=4956.8,5027.8
XS Rating Curve= 0 ,0
Exp/Cntr=0.3,0.1

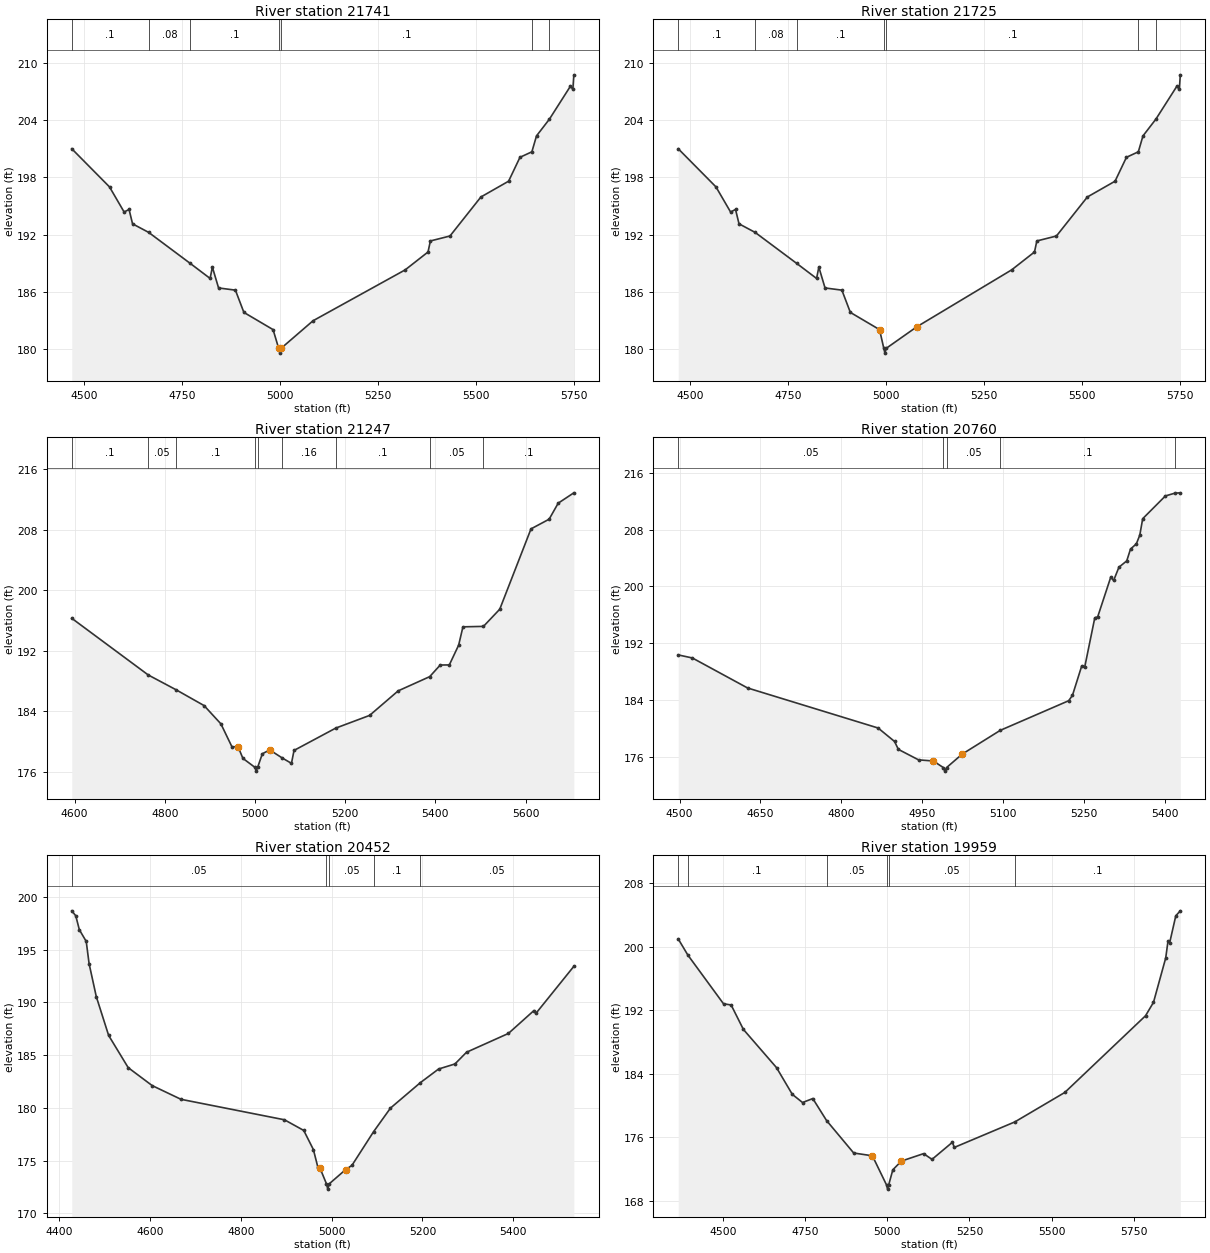
Type RM Length L Ch R = 1 ,21741   ,494,494,494
BEGIN DESCRIPTION:
ROCK QUARRY BRANCH 35.0
END DESCRIPTION:
XS GIS Cut Line= 3
      2246224.18     13364791.23      2245432.28      13364332.1
      2245142.16     13364109.25
#Sta/Elev= 30
    4469  201.02  4565.3  197.01  4602.6  194.37  4615.2  194.64  4624.1  193.13
  4665.2  192.23  4771.3  188.97    4822  187.39  4827.8  188.58  4843.6  186.39
  4886.6  186.16  4908.2  183.82  4982.7  182.01    4997  180.04  4999.8  179.54
    5003  180.04  5084.6  182.94  5319.8  188.29  5378.1  190.17  5384.1  191.33
  5434.1  191.85    5513  195.95  5583.7  197.61  5612.7  200.12  5643.1   200.7
  5654.9  202.37    5688  204.14  5741.4  207.59  5747.7  207.28  5750.2  208.79
#Mann= 7 ,-1 , 0
    4469      .1       0  4665.2     .08       0  4771.3      .1       0
    4997     .07       0    5003      .1       0  5643.1     .05       0
    5688      .1       0
Bank Sta=4997,5003
XS Rating Curve= 0 ,0
Exp/Cntr=0.3,0.1

Type RM Length L Ch R = 1 ,21725   ,478,478,478
BEGIN DESCRIPTION:
ROCK QUARRY BRANCH 35.0
END DESCRIPTION:
XS GIS Cut Line= 3
      2246224.18     13364791.23      2245432.28      13364332.1
      2245142.16     13364109.25
#Sta/Elev= 30
    4469  201.02  4565.3  197.01  4602.6  194.37  4615.2  194.64  4624.1  193.13
  4665.2  192.23  4771.3  188.97    4822  187.39  4827.8  188.58  4843.6  186.39
  4886.6  186.16  4908.2  183.82  4982.7  182.01  4993.6  180.04  4996.4  179.54
  4999.6  180.04  5077.5   182.3  5319.8  188.29  5378.1  190.17  5384.1  191.33
  5434.1  191.85    5513  195.95  5583.7  197.61  5612.7  200.12  5643.1   200.7
  5654.9  202.37    5688  204.14  5741.4  207.59  5747.7  207.28  5750.2  208.79
#Mann= 7 ,-1 , 0
    4469      .1       0  4665.2     .08       0  4771.3      .1       0
  4993.6     .07       0  4999.6      .1       0  5643.1     .05       0
    5688      .1       0
Bank Sta=4982.7,5077.5
XS Rating Curve= 0 ,0
Exp/Cntr=0.3,0.1

Type RM Length L Ch R = 1 ,21247   ,487,487,487
BEGIN DESCRIPTION:
ROCK QUARRY BRANCH 34.0
END DESCRIPTION:
XS GIS Cut Line= 3
      2246270.49     13364243.62      2245558.65     13363961.41
      2245213.27      13363923.5
#Sta/Elev= 30
  4593.7   196.3  4763.3   188.8  4825.1  186.84  4887.1  184.75  4924.4  182.33
  4948.8   179.3  4962.4  179.31  4973.1  177.77  4999.8  176.58  5002.5  176.08
  5005.8  176.58  5016.2  178.37  5032.5  178.89  5060.6  177.81  5080.8  177.11
  5086.5  178.82  5178.9  181.77    5254  183.45  5317.4   186.7  5387.3  188.58
  5410.7  190.12  5430.8  190.13  5451.5  192.75    5461  195.17  5506.5  195.23
  5542.6   197.5  5611.9  208.13  5652.1  209.41  5672.2  211.53  5706.9   212.9
#Mann= 9 ,-1 , 0
  4593.7      .1       0  4763.3     .05       0  4825.1      .1       0
  4999.8     .07       0  5005.8      .1       0  5060.6     .16       0
  5178.9      .1       0  5387.3     .05       0  5506.5      .1       0
Bank Sta=4962.4,5032.5
XS Rating Curve= 0 ,0
Exp/Cntr=0.3,0.1

Type RM Length L Ch R = 1 ,20760   ,308,308,308
BEGIN DESCRIPTION:
ROCK QUARRY BRANCH 33.0
END DESCRIPTION:
XS GIS Cut Line= 3
      2246316.84     13363893.99      2245722.93     13363557.03
      2245491.97     13363649.41
#Sta/Elev= 30
  4497.4  190.35  4523.6  189.92    4626  185.69  4868.3  180.04  4898.8  178.14
  4905.8  177.03  4943.3  175.55  4970.7  175.39  4989.3  174.46  4992.1  173.96
  4995.3  174.46  5024.1  176.35  5094.9  179.71  5221.9  183.89  5228.9  184.65
  5246.1   188.8  5251.5  188.59  5270.3  195.58  5275.7  195.72  5299.9  201.31
  5305.3  200.85  5315.1  202.72  5329.6  203.61  5336.6  205.28  5347.4  206.01
  5353.8  207.24  5359.2  209.56  5401.3  212.77  5419.2  213.17    5429  213.21
#Mann= 5 ,-1 , 0
  4497.4     .05       0  4989.3    .035       0  4995.3     .05       0
  5094.9      .1       0  5419.2     .05       0
Bank Sta=4970.7,5024.1
XS Rating Curve= 0 ,0
Exp/Cntr=0.3,0.1

Type RM Length L Ch R = 1 ,20452   ,493,493,493
BEGIN DESCRIPTION:
ROCK QUARRY BRANCH 32.0
END DESCRIPTION:
XS GIS Cut Line= 3
      2246422.17     13363704.44      2246300.02     13363493.84
      2245487.08      13363203.2
#Sta/Elev= 30
  4427.1  198.67  4435.9   198.2  4443.8  196.88    4459  195.77  4465.3  193.66
  4481.1  190.55  4508.4  186.86  4551.5  183.81  4604.4  182.11  4667.9  180.81
    4896  178.87  4938.5  177.86  4959.7  176.05  4969.3  174.43  4974.6  174.26
  4988.6   172.8  4991.4   172.3  4994.6   172.8  5030.8  174.15  5044.7  174.55
  5092.4  177.74  5129.7  179.98  5195.6  182.39  5235.7  183.68  5271.8  184.16
  5297.3  185.27  5389.6  187.05  5445.9  189.22  5451.2     189  5533.9  193.41
#Mann= 5 ,-1 , 0
  4427.1     .05       0  4988.6    .035       0  4994.6     .05       0
  5092.4      .1       0  5195.6     .05       0
Bank Sta=4974.6,5030.8
XS Rating Curve= 0 ,0
Exp/Cntr=0.3,0.1

Type RM Length L Ch R = 1 ,19959   ,524,524,524
BEGIN DESCRIPTION:
ROCK QUARRY BRANCH 31.0
END DESCRIPTION:
XS GIS Cut Line= 4
      2246784.43     13363081.03      2246472.73     13363043.12
      2245685.02     13362769.32       2245314.3     13362849.36
#Sta/Elev= 30
  4364.1  200.96  4393.3  198.93  4501.8  192.79    4525  192.64  4562.3  189.56
    4663  184.75  4711.1  181.38  4742.2  180.35  4773.4  180.85  4815.3  178.08
  4897.8  173.99  4954.7  173.64    4998  169.94  5000.8  169.44    5004  169.94
  5016.9  171.88  5042.8  172.97  5110.3  173.91  5136.1  173.19  5198.3  175.35
  5203.6  174.69  5388.1  177.91    5540  181.62  5785.5  191.28  5809.7  192.97
  5846.9  198.56  5853.9  200.69    5859  200.49  5877.6  203.88  5891.3   204.5
#Mann= 6 ,-1 , 0
  4364.1     .05       0  4393.3      .1       0  4815.3     .05       0
    4998    .035       0    5004     .05       0  5388.1      .1       0
Bank Sta=4954.7,5042.8
XS Rating Curve= 0 ,0
Exp/Cntr=0.3,0.1

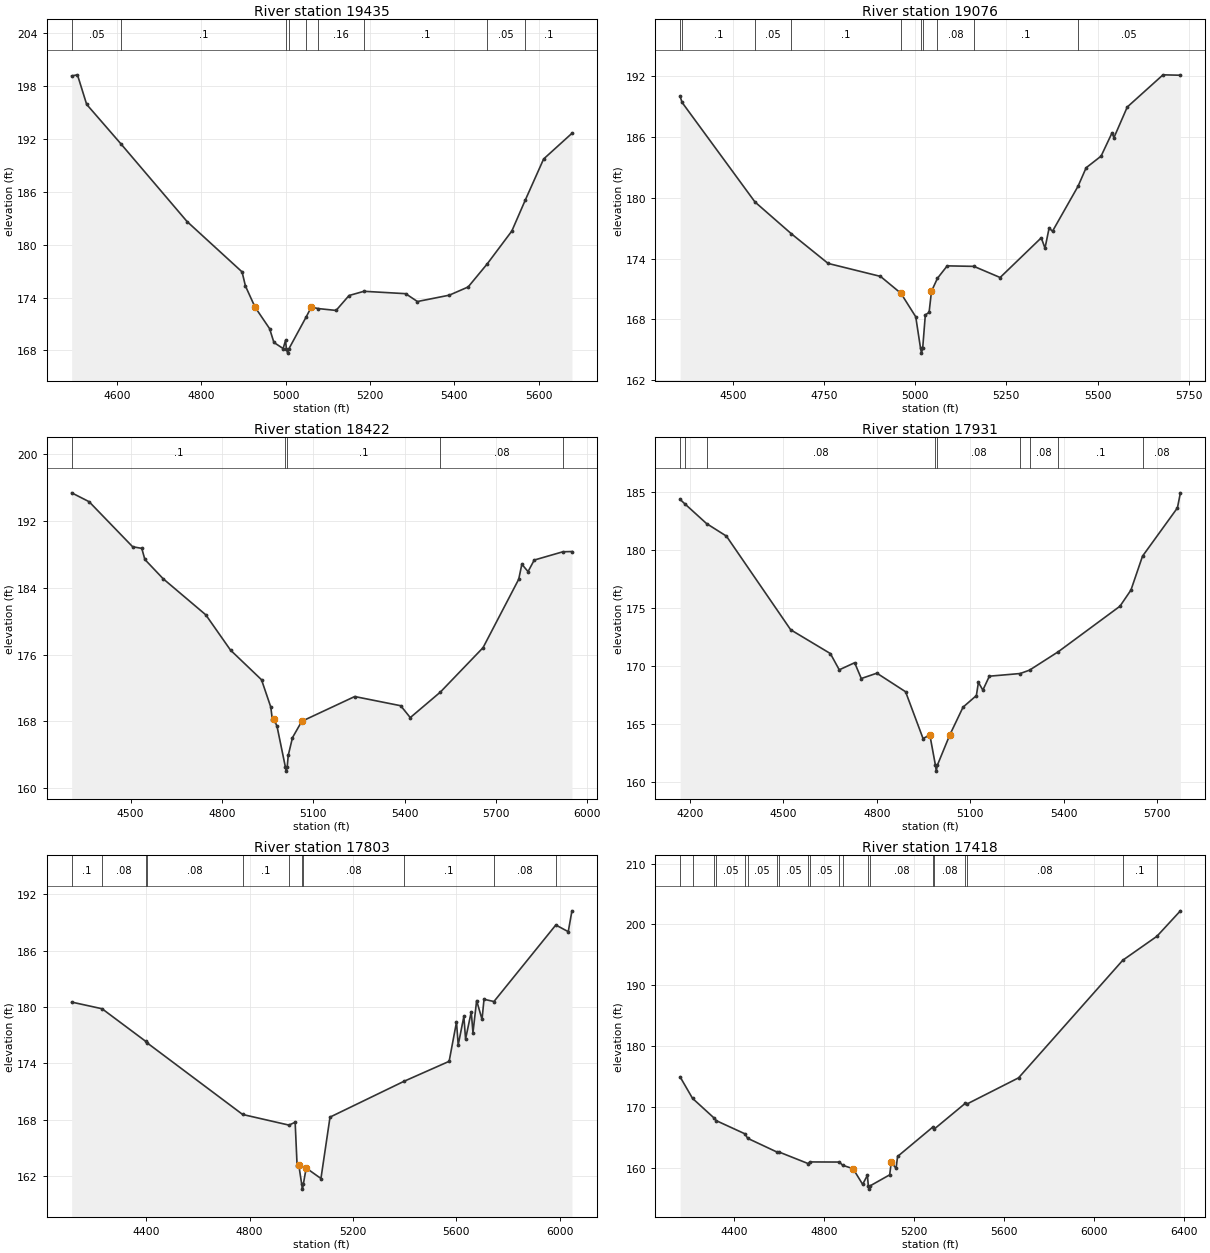
Type RM Length L Ch R = 1 ,19435   ,359,359,359
BEGIN DESCRIPTION:
ROCK QUARRY BRANCH 30.0
END DESCRIPTION:
XS GIS Cut Line= 3
      2246737.72     13362696.85      2246287.72     13362446.85
      2245687.72     13362146.86
#Sta/Elev= 30
  4492.9  199.13  4506.6  199.25  4528.4   195.9  4610.2  191.39  4766.3  182.62
  4896.7  176.91  4904.7  175.31  4927.6   172.9  4961.9  170.48  4972.2  168.91
    4994  168.22  4999.7  169.14  5001.8   168.2  5004.6   167.7  5007.8   168.2
  5048.3  171.77  5060.8  172.92  5077.4  172.75  5119.5  172.54  5150.2  174.23
  5185.6  174.71  5284.4  174.44  5312.3  173.55  5387.8  174.27  5432.5   175.2
  5477.6  177.81    5536  181.54    5568  185.06  5611.4  189.71  5678.5  192.62
#Mann= 9 ,-1 , 0
  4492.9     .05       0  4610.2      .1       0  5001.8     .07       0
  5007.8      .1       0  5048.3     .08       0  5077.4     .16       0
  5185.6      .1       0  5477.6     .05       0    5568      .1       0
Bank Sta=4927.6,5060.8
XS Rating Curve= 0 ,0
Exp/Cntr=0.3,0.1

Type RM Length L Ch R = 1 ,19076   ,654,654,654
BEGIN DESCRIPTION:
ROCK QUARRY BRANCH 29.0
END DESCRIPTION:
XS GIS Cut Line= 2
      2246923.47     13362234.36      2245585.63     13361931.45
#Sta/Elev= 30
  4355.5  190.02  4360.7  189.43  4560.7  179.59  4660.8  176.44  4761.3  173.52
  4904.8  172.24  4960.9  170.57  5001.5  168.25  5014.6  165.16  5017.3  164.66
  5020.6  165.16  5027.8  168.44  5038.1  168.68  5044.7  170.77    5061  172.05
  5087.8  173.28    5161  173.23  5232.9  172.13  5345.7  176.05  5355.9  175.03
  5367.2  177.01  5376.5   176.7  5446.6  181.15  5468.7  182.97  5509.7  184.12
  5539.8  186.42  5544.9  185.94  5581.5  188.97  5679.5  192.15  5727.2  192.11
#Mann= 10 ,-1 , 0
  4355.5     .05       0  4360.7      .1       0  4560.7     .05       0
  4660.8      .1       0  4960.9     .16       0  5014.6     .07       0
  5020.6     .16       0    5061     .08       0    5161      .1       0
  5446.6     .05       0
Bank Sta=4960.9,5044.7
XS Rating Curve= 0 ,0
Exp/Cntr=0.3,0.1

Type RM Length L Ch R = 1 ,18422   ,491,491,491
BEGIN DESCRIPTION:
ROCK QUARRY BRANCH 28.0
END DESCRIPTION:
XS GIS Cut Line= 3
      2247247.82     13361564.59      2246792.87     13361543.53
      2245626.07     13361766.78
#Sta/Elev= 30
  4306.6  195.34  4363.8  194.28  4506.9  188.89  4536.9   188.7    4547  187.37
    4607  185.07  4747.2  180.75  4828.4  176.53  4930.2  172.99  4960.7  169.72
  4965.9  168.19    4971  168.26  4981.1  167.43  5008.6  162.56  5011.4  162.06
  5014.6  162.56    5018  163.94    5032  166.07  5062.5  168.02  5236.4  170.98
  5387.5  169.88  5418.9  168.46  5517.7  171.51  5657.9  176.82  5775.2  185.01
  5785.4   186.8  5805.8  185.92  5826.1   187.3  5920.1  188.29    5950  188.32
#Mann= 5 ,-1 , 0
  4306.6      .1       0  5008.6     .07       0  5014.6      .1       0
  5517.7     .08       0  5920.1      .1       0
Bank Sta=4971,5062.5
XS Rating Curve= 0 ,0
Exp/Cntr=0.3,0.1

Type RM Length L Ch R = 1 ,17931   ,128,128,128
BEGIN DESCRIPTION:
ROCK QUARRY BRANCH 27.0
END DESCRIPTION:
XS GIS Cut Line= 2
      2246977.72     13360607.06      2245762.55     13361655.58
#Sta/Elev= 30
  4169.1  184.36  4183.8  183.99  4253.9  182.28  4317.6   181.2  4523.8  173.13
  4651.1  171.08  4679.6  169.68    4729  170.29  4750.3  168.93  4800.3  169.39
  4892.4  167.79  4948.4  163.76  4970.3  164.06  4988.2  161.45  4990.9  160.95
  4994.2  161.45  5033.9  164.05  5076.7  166.46  5119.5  167.46  5126.1   168.6
  5140.3  167.93  5161.2  169.13  5259.9  169.36    5290  169.65  5382.4  171.24
  5580.2  175.16  5615.4  176.55  5652.5  179.47  5764.5  183.63  5774.1  184.93
#Mann= 9 ,-1 , 0
  4169.1     .08       0  4183.8      .1       0  4253.9     .08       0
  4988.2     .07       0  4994.2     .08       0  5259.9      .1       0
    5290     .08       0  5382.4      .1       0  5652.5     .08       0
Bank Sta=4970.3,5033.9
XS Rating Curve= 0 ,0
Exp/Cntr=0.3,0.1

Type RM Length L Ch R = 1 ,17803   ,385,385,385
BEGIN DESCRIPTION:
Mapping XS fd7e902b
END DESCRIPTION:
XS GIS Cut Line= 4
      2246956.68     13360423.69      2246470.57      13360888.1
      2246092.96     13361213.62      2245512.54     13361711.74
#Sta/Elev= 30
  4111.6  180.52  4229.2  179.81  4398.1  176.34  4404.8  176.15  4773.2  168.55
  4952.2  167.42  4976.3  167.72  4983.9  163.08  4990.5  163.14  5001.8   161.1
  5004.5   160.6  5007.8   161.1    5019  162.85  5076.1  161.73  5111.2  168.27
  5397.2  172.08  5572.1  174.21  5600.6  178.39  5607.2  175.95  5629.1  178.99
  5635.7  176.59  5657.7  179.48  5664.3  177.26  5678.5  180.68  5699.4  178.68
  5707.1  180.82  5745.5  180.58  5984.9  188.73    6033  188.02  6047.3  190.24
#Mann= 11 ,-1 , 0
  4111.6      .1       0  4229.2     .08       0  4398.1      .1       0
  4404.8     .08       0  4773.2      .1       0  4952.2     .08       0
  5001.8     .07       0  5007.8     .08       0  5397.2      .1       0
  5745.5     .08       0  5984.9     .05       0
Bank Sta=4990.5,5019
XS Rating Curve= 0 ,0
Exp/Cntr=0.3,0.1

Type RM Length L Ch R = 1 ,17418   ,403,403,403
BEGIN DESCRIPTION:
ROCK QUARRY BRANCH 26.0
END DESCRIPTION:
XS GIS Cut Line= 4
      2246936.05     13360140.83      2246797.08     13360170.31
      2245465.98     13361417.16      2245238.53     13361539.31
#Sta/Elev= 30
  4161.4  174.94  4216.5  171.42  4310.1  168.26  4322.8  167.74    4450  165.58
  4461.2  164.86  4589.9  162.63  4599.7  162.62  4729.8  160.71  4738.2  160.97
  4869.7  160.95  4883.6  160.43  4930.4  159.85  4972.9  157.28  4993.9  158.78
  4998.2     157  5000.9   156.5  5004.2     157    5093  158.85  5099.9   160.9
  5121.4  159.92  5128.2  161.87  5286.6  166.76    5292   166.4  5429.3  170.61
    5435  170.46    5666  174.79  6129.3  194.12  6280.9  198.05  6385.5  202.24
#Mann= 20 ,-1 , 0
  4161.4     .08       0  4216.5     .05       0  4310.1     .08       0
  4322.8     .05       0    4450     .08       0  4461.2     .05       0
  4589.9     .08       0  4599.7     .05       0  4729.8     .08       0
  4738.2     .05       0  4869.7      .1       0  4883.6     .08       0
  4998.2     .07       0  5004.2     .08       0  5286.6      .1       0
    5292     .08       0  5429.3      .1       0    5435     .08       0
  6129.3      .1       0  6280.9     .08       0
Bank Sta=4930.4,5099.9
XS Rating Curve= 0 ,0
Exp/Cntr=0.3,0.1

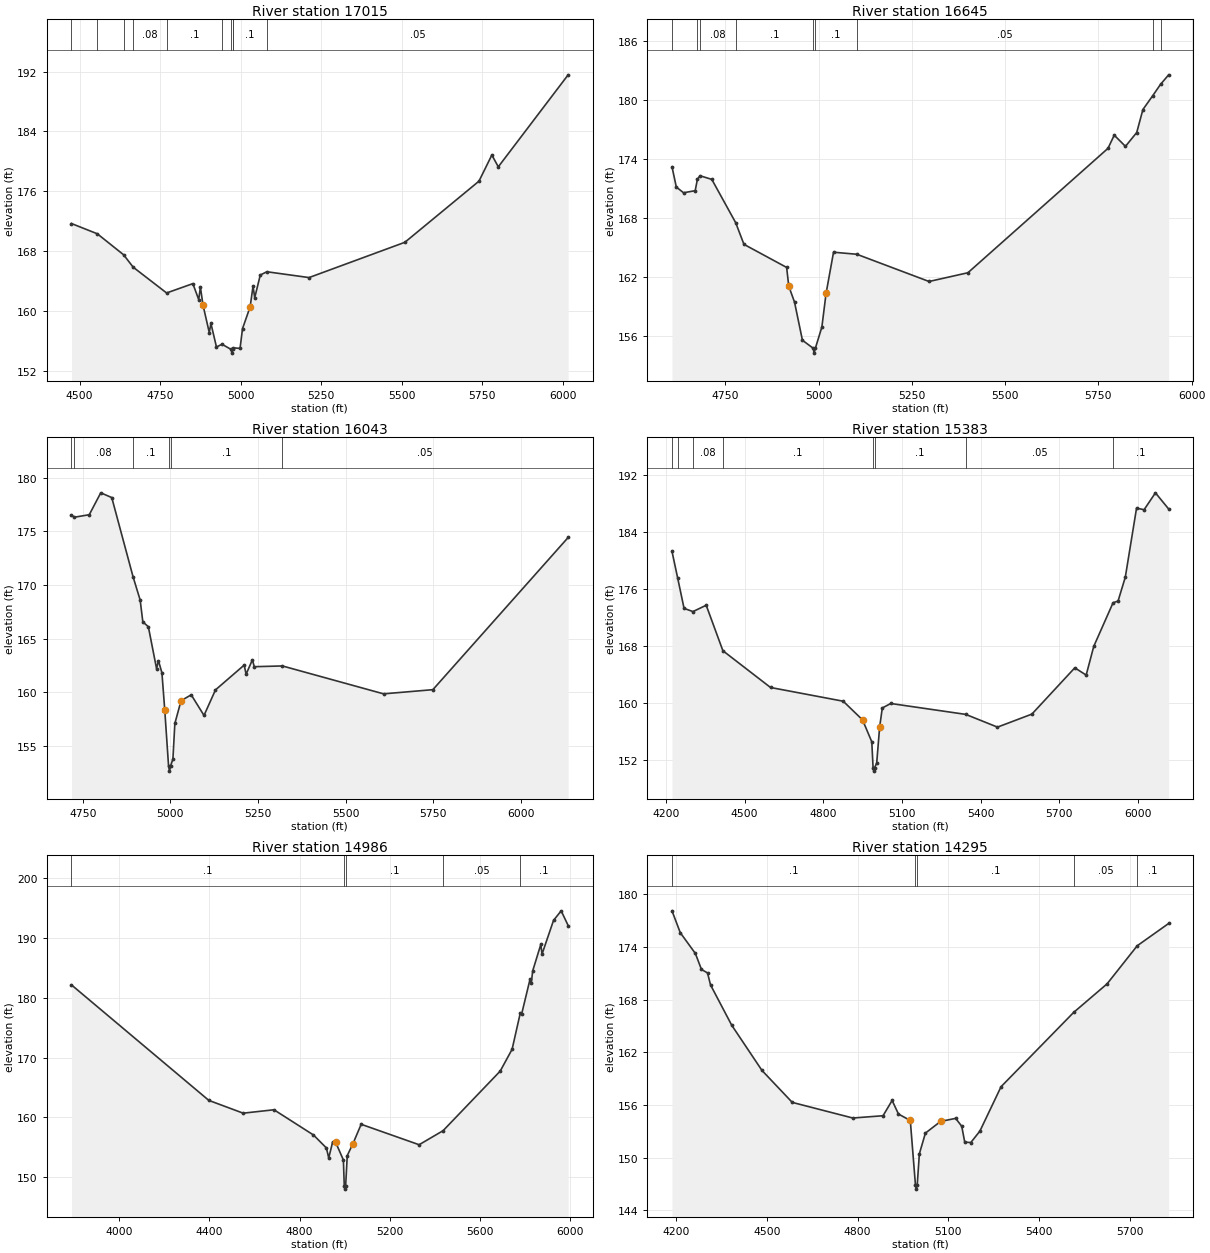
Type RM Length L Ch R = 1 ,17015   ,370,370,370
BEGIN DESCRIPTION:
ROCK QUARRY BRANCH 25.0
END DESCRIPTION:
XS GIS Cut Line= 4
      2246851.81     13360090.29      2246733.89     13360166.09
      2245899.85     13360423.05       2245370.9     13360435.64
#Sta/Elev= 30
  4474.6  171.67  4554.7   170.3  4636.4  167.49  4666.1  165.83  4769.9  162.38
  4851.4  163.63  4869.6  161.49  4874.8  163.18  4882.8  160.78  4902.3  157.09
  4907.5   158.3  4924.7  155.15  4941.9  155.52  4969.9  154.83  4972.6  154.33
  4975.9  154.83  4977.4  155.04  4997.9  154.96  5005.6  157.61  5029.3  160.54
  5038.2  163.28  5043.5  161.75  5060.7  164.78  5081.1  165.22  5212.1  164.44
  5509.6  169.16  5739.7  177.34  5779.7  180.84  5799.7  179.26  6016.6  191.57
#Mann= 10 ,-1 , 0
  4474.6     .05       0  4554.7     .08       0  4636.4     .05       0
  4666.1     .08       0  4769.9      .1       0  4941.9     .08       0
  4969.9     .07       0  4975.9     .08       0  4977.4      .1       0
  5081.1     .05       0
Bank Sta=4882.8,5029.3
XS Rating Curve= 0 ,0
Exp/Cntr=0.3,0.1

Type RM Length L Ch R = 1 ,16645   ,602,602,602
BEGIN DESCRIPTION:
ROCK QUARRY BRANCH 24.0
END DESCRIPTION:
XS GIS Cut Line= 3
      2246948.71      13360102.9      2245996.73     13359778.56
      2245672.59     13359744.88
#Sta/Elev= 30
  4606.7  173.22  4618.3  171.16  4637.6  170.58  4668.9  170.79  4674.8  171.95
  4681.8  172.31  4713.4  171.94  4777.5  167.53  4799.6  165.33  4914.1  162.98
  4919.7  161.08  4935.2  159.45  4956.4  155.57  4985.1  154.76  4987.8  154.26
  4991.1  154.76  5008.5  156.91  5019.8  160.34  5039.8  164.53  5102.2  164.32
  5295.9  161.55  5400.1  162.44  5775.7   175.1  5792.4  176.44  5822.5   175.3
  5852.7  176.71  5869.3  179.05  5895.5  180.45  5916.7  181.62  5938.3  182.58
#Mann= 9 ,-1 , 0
  4606.7     .08       0  4674.8     .05       0  4681.8     .08       0
  4777.5      .1       0  4985.1     .07       0  4991.1      .1       0
  5102.2     .05       0  5895.5      .1       0  5916.7     .05       0
Bank Sta=4919.7,5019.8
XS Rating Curve= 0 ,0
Exp/Cntr=0.3,0.1

Type RM Length L Ch R = 1 ,16043   ,660,660,660
BEGIN DESCRIPTION:
ROCK QUARRY BRANCH 23.0
END DESCRIPTION:
XS GIS Cut Line= 3
      2247294.18     13359799.64      2246717.04     13359546.88
      2245933.58     13359466.85
#Sta/Elev= 30
  4717.7  176.51  4726.2  176.32  4768.4  176.55  4801.2  178.59  4832.6  178.15
  4893.4  170.77  4913.7   168.6  4921.3  166.57  4937.1  166.11  4960.5  162.21
  4965.9  162.95  4975.8  161.82  4983.8   158.4  4994.7  153.16  4997.4  152.66
  5000.7  153.16  5007.2   153.8  5012.7   157.1  5030.4  159.22  5059.4  159.77
  5095.9  157.85  5128.7  160.23  5210.6  162.54  5216.1  161.69    5234  163.03
  5239.5  162.39  5319.6  162.46  5608.4  159.86  5749.2  160.25  6135.3  174.43
#Mann= 6 ,-1 , 0
  4717.7      .1       0  4726.2     .08       0  4893.4      .1       0
  4994.7     .07       0  5000.7      .1       0  5319.6     .05       0
Bank Sta=4983.8,5030.4
XS Rating Curve= 0 ,0
Exp/Cntr=0.3,0.1

Type RM Length L Ch R = 1 ,15383   ,397,397,397
BEGIN DESCRIPTION:
ROCK QUARRY BRANCH 22.0
END DESCRIPTION:
XS GIS Cut Line= 4
      2247605.88     13359551.11      2247125.64     13359226.74
      2246219.99     13358877.12      2246005.18     13358607.55
#Sta/Elev= 30
  4222.7  181.32  4244.2  177.61  4268.7  173.32  4302.7  172.87  4353.2  173.76
  4416.9  167.37  4598.6  162.21  4875.9  160.28  4949.7  157.66    4985  154.58
  4989.9  150.96  4992.7  150.46  4995.9  150.96  5003.7  151.58  5014.9  156.63
  5025.1  159.33  5057.3  159.96  5343.4  158.43  5464.6  156.64  5595.9  158.47
  5759.6  164.97    5803  163.95  5831.9  167.98  5905.6  174.11  5924.7  174.35
  5952.4  177.72  5995.2   187.4    6024  187.18  6067.3  189.55  6117.7  187.28
#Mann= 8 ,-1 , 0
  4222.7     .08       0  4244.2      .1       0  4302.7     .08       0
  4416.9      .1       0  4989.9     .07       0  4995.9      .1       0
  5343.4     .05       0  5905.6      .1       0
Bank Sta=4949.7,5014.9
XS Rating Curve= 0 ,0
Exp/Cntr=0.3,0.1

Type RM Length L Ch R = 1 ,14986   ,691,691,691
BEGIN DESCRIPTION:
ROCK QUARRY BRANCH 21.0
END DESCRIPTION:
XS GIS Cut Line= 3
      2248187.14     13358712.84      2247365.74     13358856.06
      2246034.64     13358544.34
#Sta/Elev= 30
  3788.8  182.16  4397.3  162.84  4549.5   160.7  4686.1  161.27  4861.1  157.05
  4918.4  154.88  4928.7  153.21    4946  155.87  4959.5  155.82  4993.7  152.86
  4997.6  148.49  5000.3  147.99  5003.6  148.49  5010.8   153.6  5036.1  155.61
  5072.5  158.84  5329.2  155.42  5435.5  157.77  5688.6  167.74  5741.3  171.39
  5777.8  177.49  5783.8  177.32  5821.1  183.16  5826.3  182.42  5832.5   184.5
  5868.7  188.95  5873.9  187.31  5924.9  192.96  5958.8  194.56  5989.7   192.1
#Mann= 5 ,-1 , 0
  3788.8      .1       0  4997.6     .07       0  5003.6      .1       0
  5435.5     .05       0  5777.8      .1       0
Bank Sta=4959.5,5036.1
XS Rating Curve= 0 ,0
Exp/Cntr=0.3,0.1

Type RM Length L Ch R = 1 ,14295   ,417,417,417
BEGIN DESCRIPTION:
ROCK QUARRY BRANCH 20.0
END DESCRIPTION:
XS GIS Cut Line= 3
      2247805.03     13358252.09      2246520.35     13358182.65
      2246164.46     13358208.69
#Sta/Elev= 30
  4186.1  178.13  4213.5  175.64  4263.5  173.27  4283.6  171.45  4303.6  171.06
  4313.6  169.69  4383.7   165.1  4483.8  159.95    4584  156.31  4784.3  154.53
  4884.4  154.79  4914.5  156.53  4935.5  154.98  4974.6  154.25  4991.6  146.93
  4994.3  146.43  4997.6  146.93  5004.6  150.45  5024.6  152.81  5074.7  154.14
  5124.8  154.49  5144.8  153.59  5154.8  151.78  5174.9  151.74  5204.9  153.04
    5275   158.1  5515.2  166.56  5625.7  169.81  5725.5  174.15  5829.5  176.69
#Mann= 5 ,-1 , 0
  4186.1      .1       0  4991.6     .07       0  4997.6      .1       0
  5515.2     .05       0  5725.5      .1       0
Bank Sta=4974.6,5074.7
XS Rating Curve= 0 ,0
Exp/Cntr=0.3,0.1