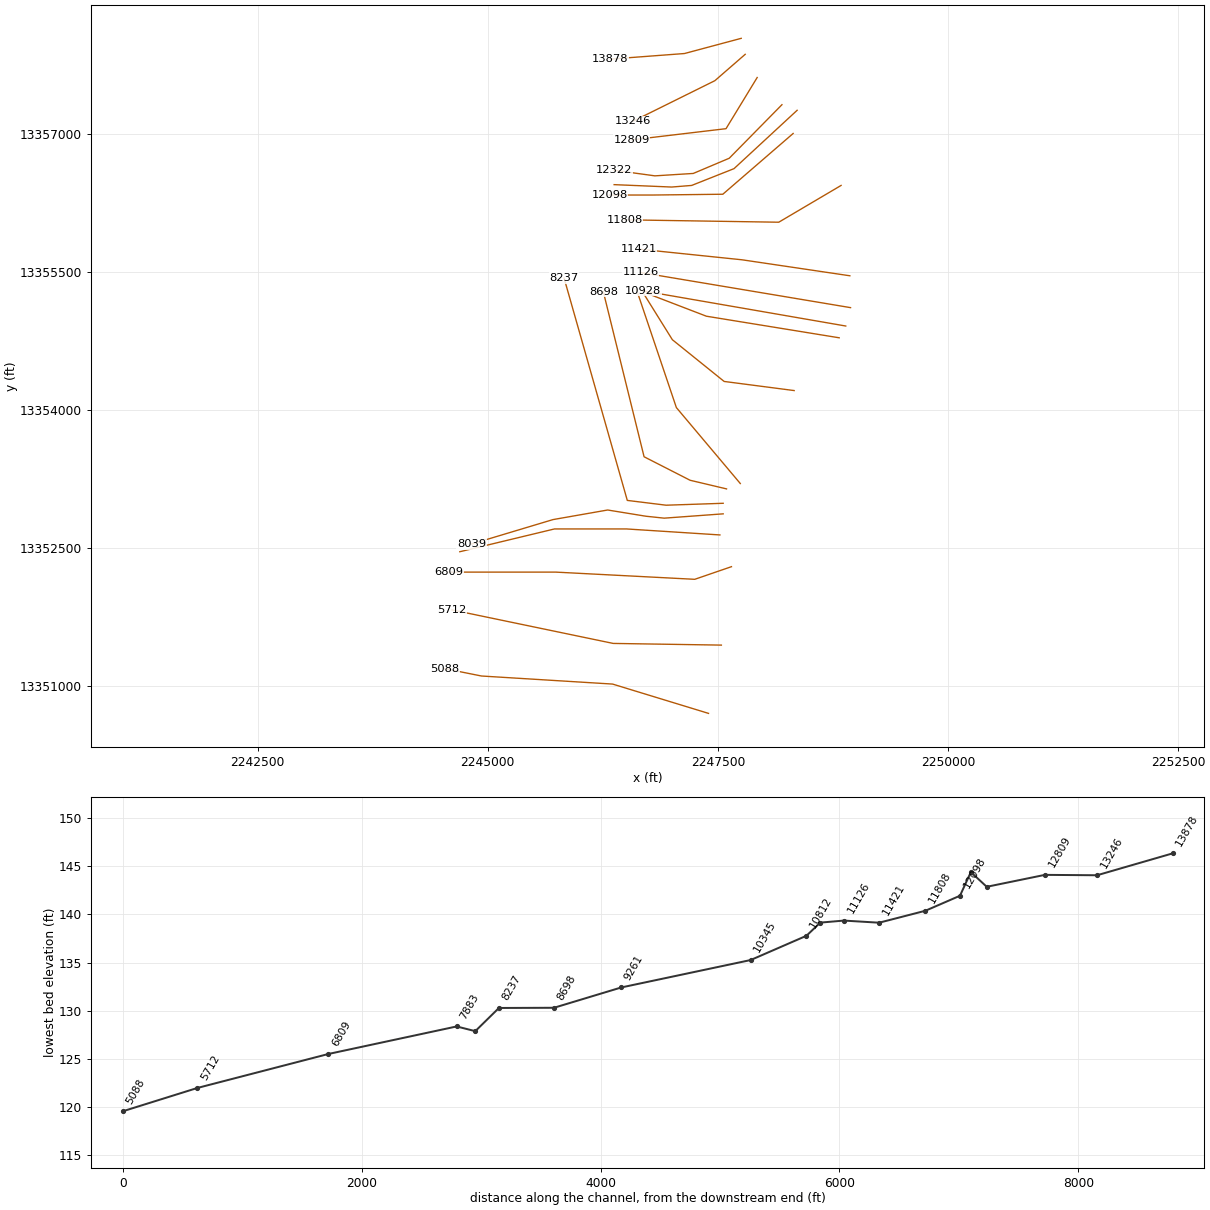
HEC-RAS study ROCK QUARRY BRANCH.prj: ROCK QUARRY BRANCH Base Level Engineering

--- ROCK QUARRY BRANCH.g01 (geometry) --- (continued)

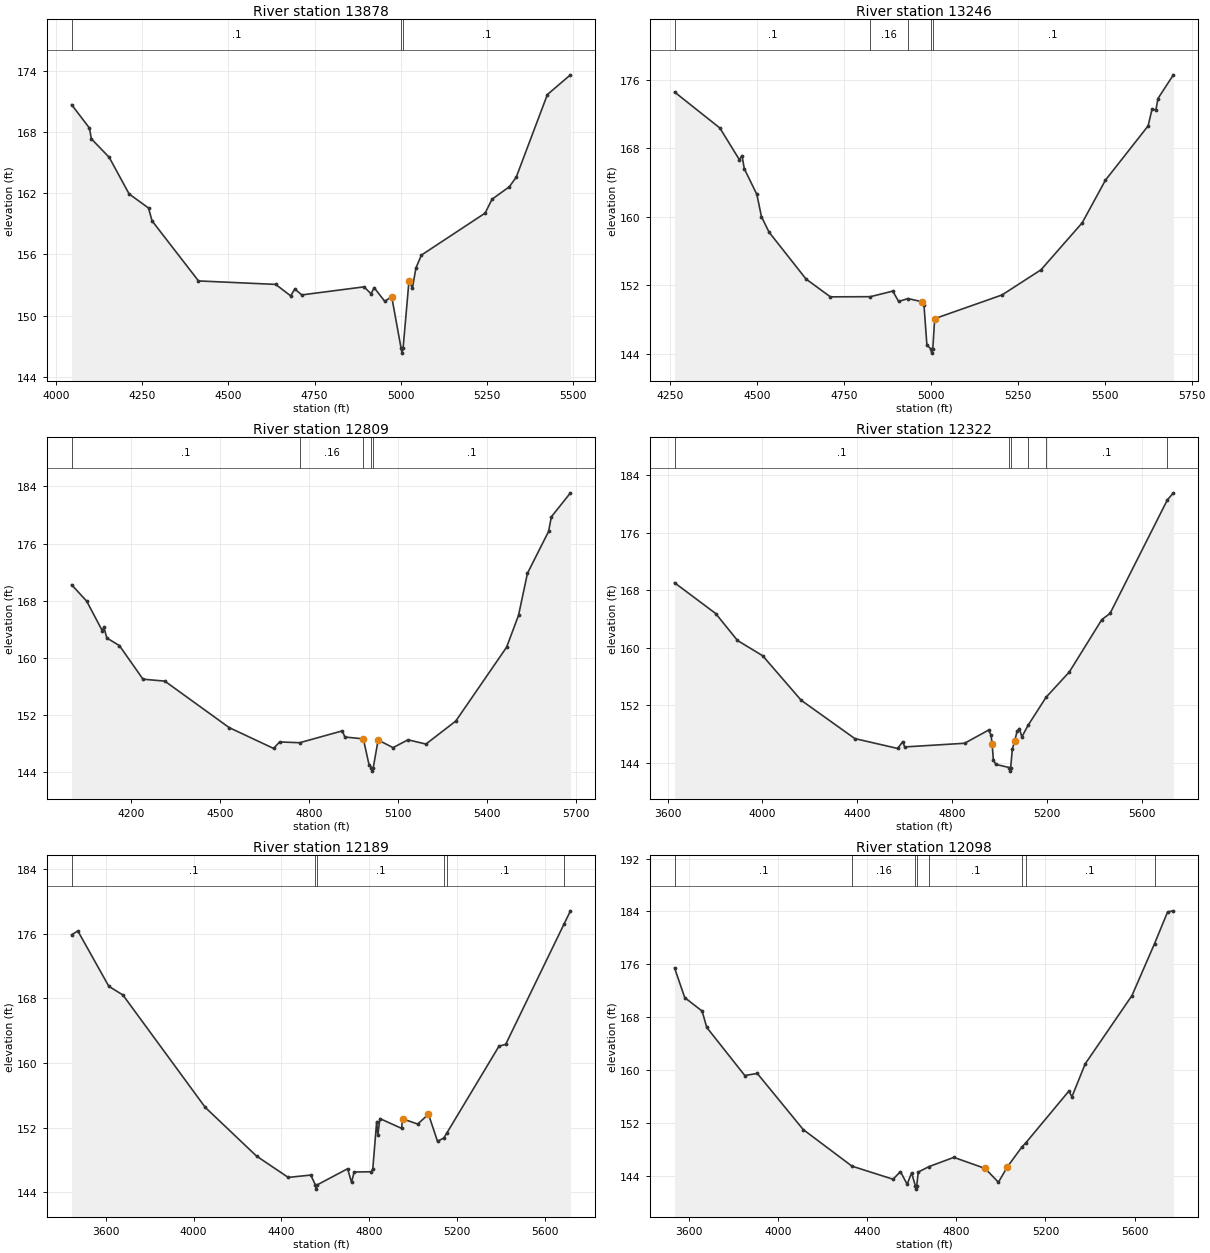
Type RM Length L Ch R = 1 ,13878   ,632,632,632
BEGIN DESCRIPTION:
ROCK QUARRY BRANCH 19.0
END DESCRIPTION:
XS GIS Cut Line= 3
      2247753.04     13358035.09      2247136.67     13357870.15
      2246331.01     13357809.51
#Sta/Elev= 30
  4045.8  170.67  4097.4  168.38  4103.1  167.32  4154.8  165.51  4212.4  161.93
  4268.7  160.55    4279  159.29  4413.6  153.41  4637.4  153.07  4680.7  151.95
  4692.8  152.62  4712.9  152.04  4893.4  152.83  4913.5  152.16    4923  152.74
  4953.6  151.41  4973.6  151.88  5000.7  146.84  5003.5  146.34  5006.7  146.84
  5023.8  153.45  5033.8  152.71  5043.8  154.68  5059.8  155.94  5244.4  160.05
  5264.4  161.41  5314.6  162.63  5334.6  163.57  5424.9  171.66  5491.8  173.59
#Mann= 3 ,-1 , 0
  4045.8      .1       0  5000.7     .07       0  5006.7      .1       0
Bank Sta=4973.6,5023.8
XS Rating Curve= 0 ,0
Exp/Cntr=0.3,0.1

Type RM Length L Ch R = 1 ,13246   ,437,437,437
BEGIN DESCRIPTION:
ROCK QUARRY BRANCH 18.0
END DESCRIPTION:
XS GIS Cut Line= 3
      2247796.42     13357861.49      2247466.54     13357575.01
      2246572.54     13357132.35
#Sta/Elev= 30
    4263   174.6  4393.4  170.39  4449.4  166.69    4457  167.16  4463.6  165.63
  4499.7  162.63    4513  160.02  4534.9  158.21  4641.2  152.73  4711.2  150.65
  4826.1  150.67  4890.6  151.32  4907.4  150.11  4934.1  150.45  4974.7  150.08
  4980.3  149.69  4988.7  145.02  4999.7  144.57  5002.5  144.07  5005.7  144.57
    5011   148.1  5204.6  150.87  5316.7  153.81  5435.1   159.3    5502  164.29
  5624.8  170.64  5636.3  172.64  5647.1  172.48  5653.1  173.84  5697.5  176.61
#Mann= 5 ,-1 , 0
    4263      .1       0  4826.1     .16       0  4934.1      .1       0
  4999.7     .07       0  5005.7      .1       0
Bank Sta=4974.7,5011
XS Rating Curve= 0 ,0
Exp/Cntr=0.3,0.1

Type RM Length L Ch R = 1 ,12809   ,487,487,487
BEGIN DESCRIPTION:
ROCK QUARRY BRANCH 17.0
END DESCRIPTION:
XS GIS Cut Line= 3
      2247926.58     13357609.69      2247588.06     13357054.17
      2246563.78     13356932.65
#Sta/Elev= 30
  3999.9  170.22  4050.8  167.92  4103.1   163.8  4108.9  164.26  4118.5  162.77
  4161.2  161.69  4240.6  156.99  4314.2  156.72  4531.1  150.21    4681  147.29
  4701.1   148.2  4768.9  148.09  4912.6  149.75  4921.2  148.89  4983.5  148.63
  5003.2  144.92    5011  144.61  5013.7  144.11    5017  144.61  5033.4  148.47
  5083.8   147.4  5134.1   148.5  5194.6   147.9  5295.3  151.13  5466.5  161.47
  5506.7  165.93  5536.9  171.83  5608.1  177.69  5617.5  179.74  5681.9   183.1
#Mann= 5 ,-1 , 0
  3999.9      .1       0  4768.9     .16       0  4983.5      .1       0
    5011     .07       0    5017      .1       0
Bank Sta=4983.5,5033.4
XS Rating Curve= 0 ,0
Exp/Cntr=0.3,0.1

Type RM Length L Ch R = 1 ,12322   ,133,133,133
BEGIN DESCRIPTION:
Mapping XS ad337f73
END DESCRIPTION:
XS GIS Cut Line= 5
       2248195.7     13357314.58      2247622.79     13356732.99
      2247232.16     13356568.06      2246815.49     13356542.02
      2246372.82     13356602.78
#Sta/Elev= 30
  3629.6  169.04  3803.4  164.76  3895.2  161.02  4001.4   158.9    4164  152.71
  4390.3  147.39  4570.9  146.02  4592.6  146.97  4600.6  146.23  4853.1  146.74
  4954.6  148.57  4964.6   147.9  4969.6  146.68  4974.6  144.46  4984.7  143.81
  5041.8  143.37  5044.5  142.87  5047.8  143.37  5054.8  145.95  5064.8  147.06
  5074.8  148.41  5084.9  148.78  5094.9  147.62  5120.7  149.21  5197.3  153.14
  5295.3  156.65  5432.5  163.93  5466.9  164.77  5708.4  180.52  5734.3  181.53
#Mann= 6 ,-1 , 0
  3629.6      .1       0  5041.8     .07       0  5047.8      .1       0
  5120.7     .16       0  5197.3      .1       0  5708.4     .08       0
Bank Sta=4969.6,5064.8
XS Rating Curve= 0 ,0
Exp/Cntr=0.3,0.1

Type RM Length L Ch R = 1 ,12189   ,91,91,91
BEGIN DESCRIPTION:
ROCK QUARRY BRANCH 16.0
END DESCRIPTION:
XS GIS Cut Line= 5
      2248360.63     13357253.82      2247674.87     13356620.15
       2247214.8     13356437.86      2246997.79     13356420.49
      2246372.81     13356446.53
#Sta/Elev= 30
  3444.2  175.87  3472.6  176.34  3613.8  169.49  3677.8  168.42  4052.6  154.52
  4286.3  148.49  4430.8  145.85  4533.5  146.14  4554.7   144.9  4557.5   144.4
  4560.7   144.9    4701  146.92    4719  145.23  4730.7  146.52    4809  146.55
  4815.9  146.94  4833.4  152.75  4838.8  151.09  4848.1  153.13  4946.6  151.92
  4951.6   153.1  5020.3  152.45  5069.4  153.67  5110.6  150.31  5139.5  150.74
  5152.1   151.3  5390.8   162.1  5420.8   162.3  5685.7  177.14    5716  178.83
#Mann= 6 ,-1 , 0
  3444.2      .1       0  4554.7     .07       0  4560.7      .1       0
  5139.5     .16       0  5152.1      .1       0  5685.7     .08       0
Bank Sta=4951.6,5069.4
XS Rating Curve= 0 ,0
Exp/Cntr=0.3,0.1

Type RM Length L Ch R = 1 ,12098   ,290,290,290
BEGIN DESCRIPTION:
ROCK QUARRY BRANCH 15.0
END DESCRIPTION:
XS GIS Cut Line= 4
      2248317.21     13357002.07      2247553.34     13356342.37
      2246789.45     13356333.69      2246321.69     13356333.69
#Sta/Elev= 30
  3533.7  175.46  3579.6  170.95  3657.5  168.92  3678.4  166.44  3849.4  159.15
  3905.4  159.47  4111.6  150.97  4330.8  145.42  4515.3  143.44  4548.6   144.6
  4578.6  142.67  4598.6  144.41  4615.6  142.44  4618.4  141.94  4621.6  142.44
  4628.6  144.53  4677.2  145.36  4788.6  146.75  4928.6  145.08  4988.7  142.98
  5028.7  145.31    5094  148.32  5111.4  148.94  5305.3   156.8  5318.7  155.92
  5378.7  160.93  5588.7  171.27    5690  179.13  5748.7  183.94  5774.7   184.1
#Mann= 8 ,-1 , 0
  3533.7      .1       0  4330.8     .16       0  4615.6     .07       0
  4621.6     .16       0  4677.2      .1       0    5094     .16       0
  5111.4      .1       0    5690     .08       0
Bank Sta=4928.6,5028.7
XS Rating Curve= 0 ,0
Exp/Cntr=0.3,0.1

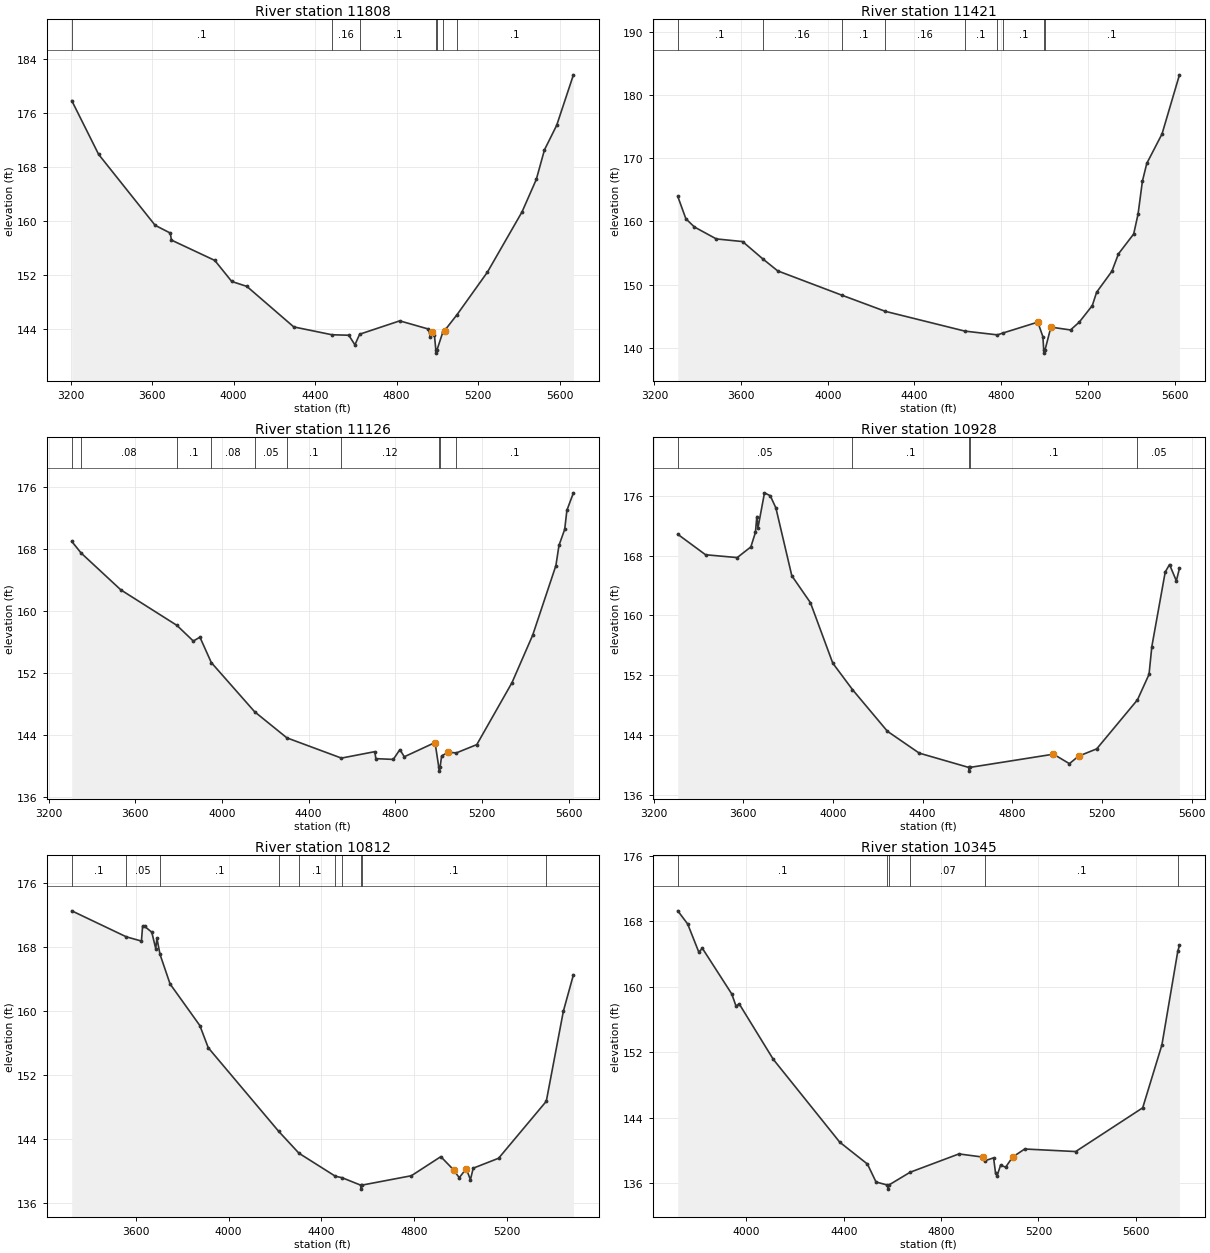
Type RM Length L Ch R = 1 ,11808   ,387,387,387
BEGIN DESCRIPTION:
Mapping XS abcd0ced
END DESCRIPTION:
XS GIS Cut Line= 3
      2248838.09     13356437.87      2248160.98     13356038.55
      2246485.67     13356064.59
#Sta/Elev= 30
  3205.8  177.77  3337.7  169.81  3614.9  159.31  3689.1  158.16  3694.9  157.12
  3907.6  154.11  3990.9  150.99  4065.2  150.26  4295.2  144.26  4482.7   143.1
  4565.2  143.03  4595.2  141.61  4618.5  143.18  4815.2  145.16  4955.3  143.95
  4965.3   142.8  4975.3  143.55  4985.3  143.05  4992.3  140.88    4995  140.38
  4998.3  140.88  5026.7   143.5  5035.3  143.72  5096.2  146.07  5245.3  152.37
  5415.3   161.3  5485.3  166.11  5525.3  170.48  5585.3  174.12  5667.4  181.59
#Mann= 7 ,-1 , 0
  3205.8      .1       0  4482.7     .16       0  4618.5      .1       0
  4992.3     .07       0  4998.3      .1       0  5026.7     .16       0
  5096.2      .1       0
Bank Sta=4975.3,5035.3
XS Rating Curve= 0 ,0
Exp/Cntr=0.3,0.1

Type RM Length L Ch R = 1 ,11421   ,295,295,295
BEGIN DESCRIPTION:
ROCK QUARRY BRANCH 14.0
END DESCRIPTION:
XS GIS Cut Line= 3
       2248933.6     13355456.95      2247761.67     13355630.56
      2246637.69     13355746.86
#Sta/Elev= 30
    3308  163.96  3345.4  160.42  3384.7  159.12  3485.8  157.23  3607.1  156.81
  3699.5  154.09  3768.9  152.17  4065.6  148.31  4265.5  145.76  4632.5  142.63
  4782.6  142.03  4807.7  142.32  4969.2  144.05  4992.7  141.73  4996.4  139.64
  4999.1  139.14  5002.4  139.64  5029.5  143.26    5120  142.81  5160.2  144.04
  5220.5  146.67  5240.6  148.79    5311  152.11  5341.2  154.86  5411.5  158.01
  5431.7  161.16  5451.8  166.38  5471.9  169.19  5542.2  173.85  5622.7  183.22
#Mann= 9 ,-1 , 0
    3308      .1       0  3699.5     .16       0  4065.6      .1       0
  4265.5     .16       0  4632.5      .1       0  4782.6     .16       0
  4807.7      .1       0  4996.4     .07       0  5002.4      .1       0
Bank Sta=4969.2,5029.5
XS Rating Curve= 0 ,0
Exp/Cntr=0.3,0.1

Type RM Length L Ch R = 1 ,11126   ,198,198,198
BEGIN DESCRIPTION:
Mapping XS 40291872
END DESCRIPTION:
XS GIS Cut Line= 2
      2248940.97     13355111.06        2246658.       13355493.
#Sta/Elev= 30
    3307  168.98  3350.2  167.48  3533.4  162.73  3792.3  158.15  3867.9  156.13
  3898.4  156.63  3950.8  153.36    4151  147.01  4299.6  143.65  4551.3  141.04
  4705.1  141.87  4710.1  140.97  4790.6  140.87    4821  142.14  4841.3  141.21
  4983.2  143.05  5000.5  139.86  5003.3  139.36  5006.5  139.86  5013.7  141.33
  5044.1  141.79  5081.5  141.71  5175.9  142.78  5338.1  150.76  5433.7  156.89
  5540.9  165.87  5555.1  168.47  5581.4  170.53  5591.6  172.99  5621.7  175.24
#Mann= 10 ,-1 , 0
    3307      .1       0  3350.2     .08       0  3792.3      .1       0
  3950.8     .08       0    4151     .05       0  4299.6      .1       0
  4551.3     .12       0  5000.5     .07       0  5006.5     .12       0
  5081.5      .1       0
Bank Sta=4983.2,5044.1
XS Rating Curve= 0 ,0
Exp/Cntr=0.3,0.1

Type RM Length L Ch R = 1 ,10928   ,116,116,116
BEGIN DESCRIPTION:
ROCK QUARRY BRANCH 13.0
END DESCRIPTION:
XS GIS Cut Line= 2
      2248888.89     13354911.41      2246684.03     13355293.35
#Sta/Elev= 30
    3308  170.86  3431.9  168.12  3573.1  167.74    3634  169.17  3654.3  171.11
  3660.7  173.24  3665.8  171.74  3694.8  176.41  3720.5  176.02  3745.6  174.39
  3816.6  165.31  3899.7   161.7  3999.3  153.61  4087.1  150.07  4242.9  144.49
    4385  141.56  4605.3  139.65    4608  139.15  4611.3  139.65  4983.8  141.42
  5054.8  140.15  5095.4  141.15  5176.6  142.13  5358.5   148.7    5410  152.11
  5422.5  155.83  5482.2  165.81  5501.4  166.81  5531.8  164.63  5545.7   166.3
#Mann= 5 ,-1 , 0
    3308     .05       0  4087.1      .1       0  4605.3     .07       0
  4611.3      .1       0  5358.5     .05       0
Bank Sta=4983.8,5095.4
XS Rating Curve= 0 ,0
Exp/Cntr=0.3,0.1

Type RM Length L Ch R = 1 ,10812   ,467,467,467
BEGIN DESCRIPTION:
Mapping XS bd511746
END DESCRIPTION:
XS GIS Cut Line= 3
      2248817.65     13354783.59      2247374.95     13355017.96
      2246723.92     13355267.96
#Sta/Elev= 30
  3325.4  172.47  3560.2  169.23  3625.3   168.7  3630.4  170.59  3639.4  170.52
  3669.8  169.81  3686.9  167.75  3691.9  169.06  3705.2  167.05  3748.5  163.36
  3876.7  158.17  3912.9   155.4  4215.8  144.99  4303.4  142.25  4459.7  139.39
  4489.1   139.2  4568.5  138.28  4571.2  137.78  4574.5  138.28    4787  139.45
  4913.7  141.83  4968.4  140.19    4993   139.2  5023.1  140.33  5041.1  138.95
  5053.1  140.39  5162.4  141.63  5367.6  148.73  5441.2  159.97  5484.4   164.5
#Mann= 10 ,-1 , 0
  3325.4      .1       0  3560.2     .05       0  3705.2      .1       0
  4215.8     .16       0  4303.4      .1       0  4459.7     .16       0
  4489.1      .1       0  4568.5     .07       0  4574.5      .1       0
  5367.6     .05       0
Bank Sta=4968.4,5023.1
XS Rating Curve= 0 ,0
Exp/Cntr=0.3,0.1

Type RM Length L Ch R = 1 ,10345   ,1084,1084,1084
BEGIN DESCRIPTION:
Mapping XS fc02bfde
END DESCRIPTION:
XS GIS Cut Line= 4
      2248328.04     13354210.67      2247567.66     13354309.63
      2247005.16     13354762.75      2246702.04     13355248.89
#Sta/Elev= 30
  3717.8  169.25  3758.5  167.64  3804.1  164.22    3819  164.67    3940  159.08
  3957.3   157.6  3970.2  157.89  4110.4  151.11  4383.7  140.99  4497.4  138.32
  4532.7  136.13  4579.3  135.76  4582.1  135.26  4585.3  135.76  4672.7  137.32
  4873.4  139.56  4972.6  139.17  4980.9  138.73  5015.8  139.08  5023.8  137.25
  5030.2  136.89  5044.6  138.19  5065.4  137.94  5094.2  139.18  5143.8  140.16
  5353.2  139.85  5628.7  145.19  5707.7  152.88  5773.1  164.34  5779.8  165.02
#Mann= 6 ,-1 , 0
  3717.8      .1       0  4579.3     .07       0  4585.3      .1       0
  4672.7     .07       0  4980.9      .1       0  5773.1     .05       0
Bank Sta=4972.6,5094.2
XS Rating Curve= 0 ,0
Exp/Cntr=0.3,0.1

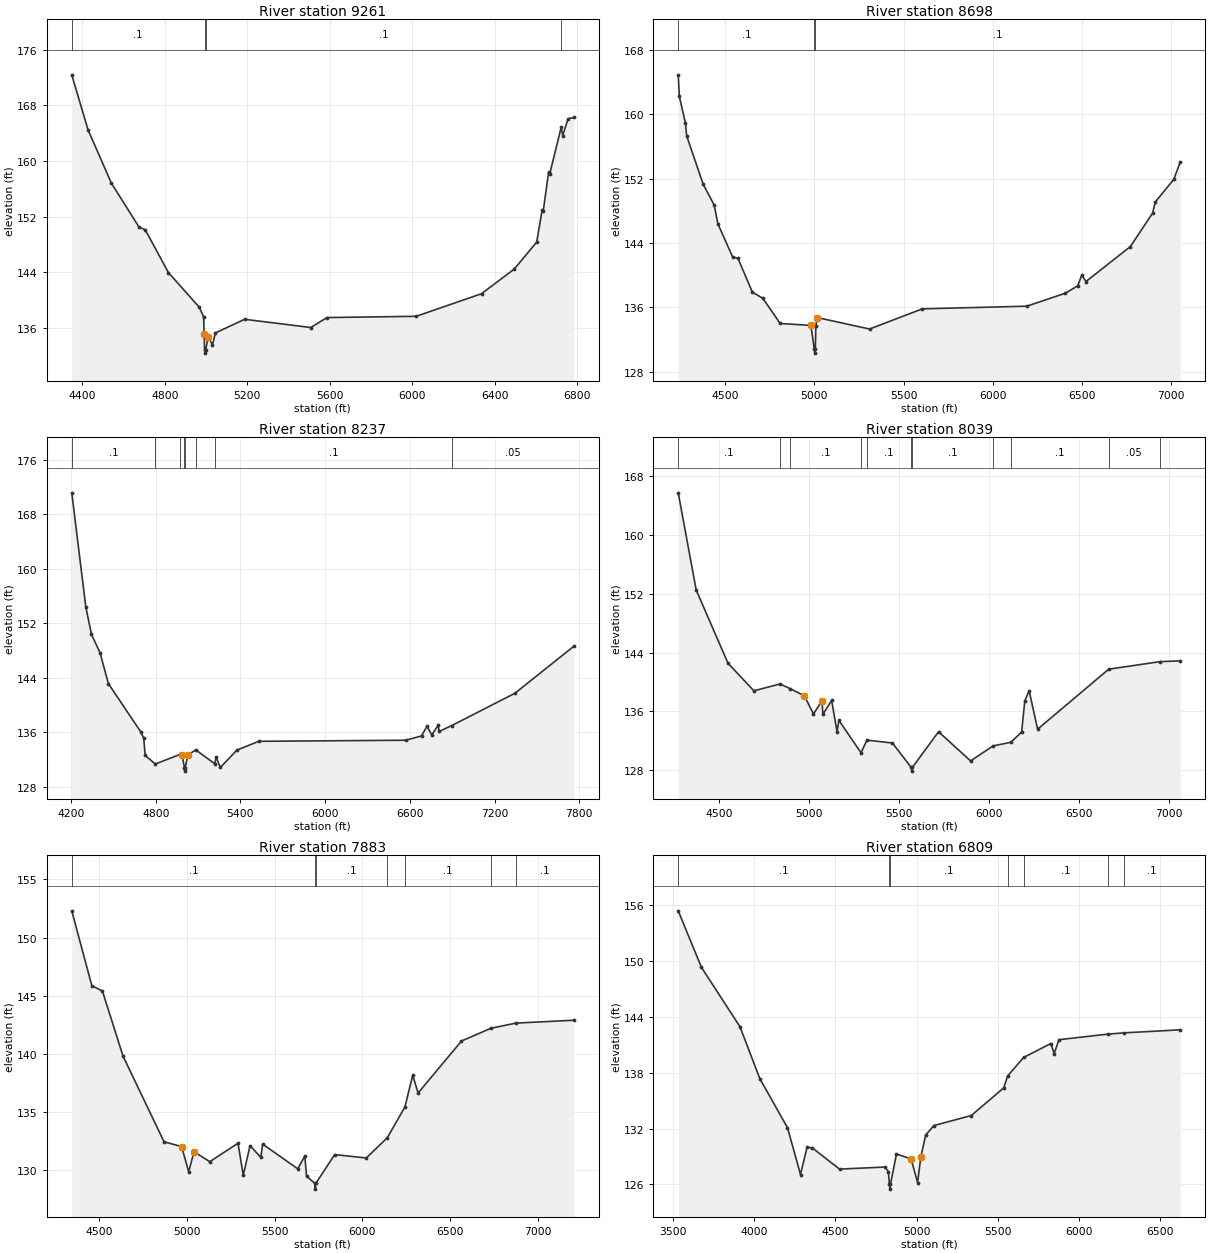
Type RM Length L Ch R = 1 ,9261    ,563,563,563
BEGIN DESCRIPTION:
ROCK QUARRY BRANCH 12.0
END DESCRIPTION:
XS GIS Cut Line= 3
      2247743.07     13353201.31       2247048.6     13354025.99
      2246614.57     13355310.71
#Sta/Elev= 30
    4349  172.39  4427.7   164.5  4540.8  156.84  4676.1  150.47  4704.7  150.15
  4817.8  143.97  4967.3  139.01  4988.2  137.62 4990.74   135.2  4992.9  132.91
  4995.7  132.41  4998.9  132.91  5009.9  134.79  5031.1  133.58  5045.4  135.31
  5187.1  137.27  5507.6  136.09  5586.4  137.52  6019.1   137.7  6335.8  140.95
  6494.1  144.48  6603.2  148.37  6629.4  152.95  6634.7  152.79  6660.9  158.42
  6666.1  158.13  6722.1  164.89  6729.1  163.65  6755.2  166.07  6783.2  166.27
#Mann= 4 ,-1 , 0
    4349      .1       0  4992.9     .07       0  4998.9      .1       0
  6722.1     .05       0
Bank Sta=4990.74,5009.9
XS Rating Curve= 0 ,0
Exp/Cntr=0.3,0.1

Type RM Length L Ch R = 1 ,8698    ,461,461,461
BEGIN DESCRIPTION:
Mapping XS 26072365
END DESCRIPTION:
XS GIS Cut Line= 4
      2247593.73     13353142.96      2247197.87     13353236.71
      2246697.87     13353491.92      2246255.38     13355282.69
#Sta/Elev= 30
  4237.3  164.93  4243.5  162.24  4277.7  158.91  4284.6  157.32  4377.1  151.31
  4438.7  148.73  4459.3   146.4  4541.5  142.29  4572.3  142.08  4652.7  137.88
  4711.6  137.12  4808.2  133.99  4980.4  133.75  4999.6   130.8  5002.4   130.3
  5005.6   130.8  5008.3  133.63  5014.8  134.73  5309.4   133.3  5604.6  135.81
    6190  136.14  6405.4  137.75    6475  138.67  6498.1     140  6521.6  139.21
  6770.3  143.56  6894.6  147.71  6910.2  149.12  7013.2  151.91  7050.1  154.09
#Mann= 3 ,-1 , 0
  4237.3      .1       0  4999.6     .07       0  5005.6      .1       0
Bank Sta=4980.4,5014.8
XS Rating Curve= 0 ,0
Exp/Cntr=0.3,0.1

Type RM Length L Ch R = 1 ,8237    ,198,198,198
BEGIN DESCRIPTION:
Mapping XS eb54742b
END DESCRIPTION:
XS GIS Cut Line= 4
      2247557.21     13352986.71      2246937.45     13352965.88
      2246515.58     13353017.96      2245828.47     13355433.25
#Sta/Elev= 30
  4205.6  171.17  4305.1   154.4  4345.2  150.37  4405.2   147.7  4465.2  143.13
  4695.4  136.02  4715.4  135.12  4725.4  132.58  4797.4  131.33  4973.1  132.74
  4986.6  132.68  5003.8  130.78  5006.6  130.28  5009.8  130.78    5027  132.65
  5084.1   133.4  5218.1  131.37  5228.5  132.32    5258  130.82  5375.2  133.37
  5530.3  134.66    6570  134.82  6682.9  135.45  6721.9  136.88  6755.8   135.6
  6800.1  136.99  6809.1  136.12  6897.4  136.98  7344.5  141.72  7761.9  148.63
#Mann= 8 ,-1 , 0
  4205.6      .1       0  4797.4     .07       0  4973.1      .1       0
  5003.8     .07       0  5009.8      .1       0  5084.1     .16       0
  5218.1      .1       0  6897.4     .05       0
Bank Sta=4986.6,5027
XS Rating Curve= 0 ,0
Exp/Cntr=0.3,0.1

Type RM Length L Ch R = 1 ,8039    ,156,156,156
BEGIN DESCRIPTION:
ROCK QUARRY BRANCH 11.0
END DESCRIPTION:
XS GIS Cut Line= 6
      2247557.25     13352872.13      2246916.62     13352825.25
       2246718.7     13352846.09      2246302.04      13352913.8
      2245708.29     13352809.63      2244822.88     13352544.01
#Sta/Elev= 30
    4274  165.76  4373.8  152.53  4550.5  142.56  4694.7   138.8  4839.9  139.74
  4895.7   139.1    4975  138.12  5025.8  135.65    5073  137.46    5078  135.59
  5126.5   137.5  5156.9  133.24    5167  134.78  5290.1  130.37  5322.8  132.09
  5464.5   131.7  5569.3  128.37  5572.1  127.87  5575.3  128.37  5720.9  133.23
  5899.1  129.26  6023.8   131.3    6123   131.8  6182.7  133.19  6200.2  137.43
  6224.4  138.82  6271.6  133.58  6666.8  141.75  6950.7  142.77  7064.7  142.89
#Mann= 11 ,-1 , 0
    4274      .1       0  4839.9     .07       0  4895.7      .1       0
  5290.1     .16       0  5322.8      .1       0  5569.3     .07       0
  5575.3      .1       0  6023.8     .05       0    6123      .1       0
  6666.8     .05       0  6950.7      .1       0
Bank Sta=4975,5073
XS Rating Curve= 0 ,0
Exp/Cntr=0.3,0.1

Type RM Length L Ch R = 1 ,7883    ,1074,1074,1074
BEGIN DESCRIPTION:
Mapping XS a045838a
END DESCRIPTION:
XS GIS Cut Line= 4
      2247521.67     13352643.04      2246506.07     13352708.15
      2245724.82     13352708.15      2244696.18     13352460.75
#Sta/Elev= 30
  4345.8   152.3    4460  145.86  4520.1   145.4  4637.6   139.8  4870.8  132.43
    4971  132.02  5011.1  129.85  5041.2  131.58  5131.4  130.72  5291.7  132.31
  5321.7  129.55  5360.1   132.1  5421.8  131.09  5431.8  132.23  5631.8  130.11
  5671.8   131.2  5681.8  129.47  5728.8  128.86  5731.6  128.36  5734.8  128.86
  5841.8  131.33  6021.8  131.04  6141.1  132.78  6241.3  135.42  6285.7  138.16
  6316.6  136.63  6563.4   141.1  6729.5  142.19  6872.2  142.64  7202.7  142.89
#Mann= 7 ,-1 , 0
  4345.8      .1       0  5728.8     .07       0  5734.8      .1       0
  6141.1     .05       0  6241.3      .1       0  6729.5     .05       0
  6872.2      .1       0
Bank Sta=4971,5041.2
XS Rating Curve= 0 ,0
Exp/Cntr=0.3,0.1

Type RM Length L Ch R = 1 ,6809    ,1097,1097,1097
BEGIN DESCRIPTION:
ROCK QUARRY BRANCH 10.0
END DESCRIPTION:
XS GIS Cut Line= 4
       2247647.2     13352298.44      2247248.26     13352161.27
      2245737.85      13352239.4      2244580.85      13352239.4
#Sta/Elev= 30
  3531.8  155.37  3674.5  149.31  3911.9  142.93  4034.3  137.35  4204.5   132.1
  4284.6  127.07  4324.7  129.97    4356  129.94    4525  127.65  4805.3  127.87
  4825.4  127.39  4832.4     126  4835.1   125.5  4838.4     126  4875.4  129.27
  4965.6  128.75  5005.6   126.2  5025.6  128.99  5055.7  131.32  5105.7  132.32
  5336.1   133.4  5536.2  136.37  5559.7  137.64    5658  139.63  5826.2  141.13
  5846.2  140.05  5876.2  141.54  6178.6  142.14    6275  142.27  6623.1   142.6
#Mann= 7 ,-1 , 0
  3531.8      .1       0  4832.4     .07       0  4838.4      .1       0
  5559.7     .05       0    5658      .1       0  6178.6     .16       0
    6275      .1       0
Bank Sta=4965.6,5025.6
XS Rating Curve= 0 ,0
Exp/Cntr=0.3,0.1

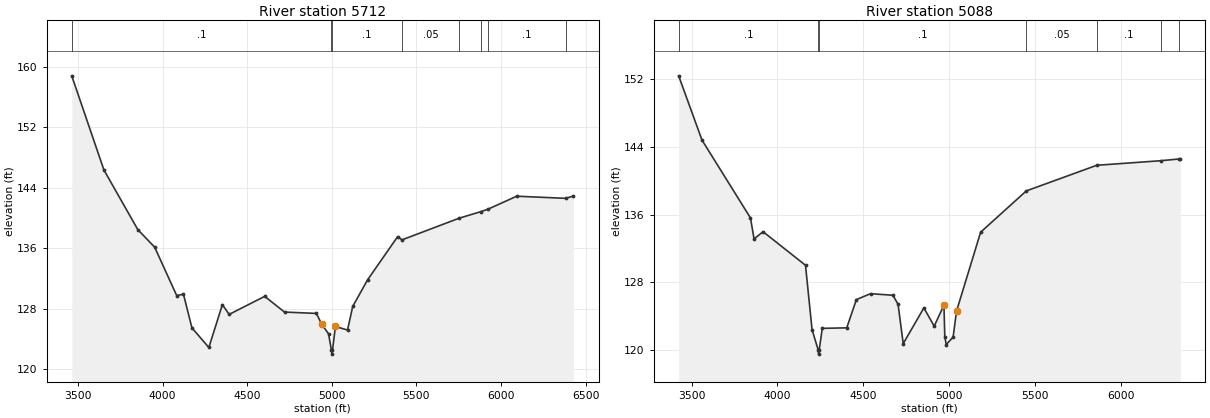
Type RM Length L Ch R = 1 ,5712    ,624,624,624
BEGIN DESCRIPTION:
ROCK QUARRY BRANCH 9.0
END DESCRIPTION:
XS GIS Cut Line= 3
       2247537.7     13351446.86      2246362.52     13351465.12
      2244610.91     13351829.32
#Sta/Elev= 30
  3463.6  158.82  3653.6  146.36  3853.6  138.47  3953.6  136.13  4083.7  129.73
  4123.7   129.9  4173.7  125.45  4273.7  122.85  4353.7  128.52  4393.7  127.23
  4603.7  129.62  4720.8  127.54  4909.4  127.36    4940  125.95  4980.9  124.66
  4998.3  122.47  5001.1  121.97  5004.3  122.47  5021.7  125.63  5093.2  125.16
  5123.9  128.29  5211.5   131.8  5389.4  137.53    5415   137.1  5753.1  139.97
  5881.5  140.84  5923.1  141.16  6092.8  142.88  6381.3   142.6    6428   142.9
#Mann= 8 ,-1 , 0
  3463.6      .1       0  4998.3     .07       0  5004.3      .1       0
    5415     .05       0  5753.1      .1       0  5881.5     .05       0
  5923.1      .1       0  6381.3     .05       0
Bank Sta=4940,5021.7
XS Rating Curve= 0 ,0
Exp/Cntr=0.3,0.1

Type RM Length L Ch R = 1 ,5088    ,558,558,558
BEGIN DESCRIPTION:
ROCK QUARRY BRANCH 8.0
END DESCRIPTION:
XS GIS Cut Line= 4
      2247397.74     13350705.61      2246355.66      13351023.8
       2244931.7     13351111.31       2244533.9     13351190.87
#Sta/Elev= 30
  3425.2  152.37  3561.1  144.79  3843.5  135.61  3864.4  133.13  3916.6  133.99
    4164  130.03  4202.1  122.44  4237.8  120.05  4240.5  119.55  4243.8  120.05
  4261.7  122.59  4404.1  122.65  4460.3  125.98  4542.8  126.68    4673  126.49
  4703.1  125.43  4733.1  120.79  4853.4     125  4913.5  122.85  4970.3  125.32
  4975.3  121.61  4983.6  120.68  5023.7  121.56  5043.7  124.63    5184  133.93
  5450.2   138.8  5860.4  141.82  6233.4  142.36  6338.2  142.56  6347.1  142.55
#Mann= 7 ,-1 , 0
  3425.2      .1       0  4237.8     .07       0  4243.8      .1       0
  5450.2     .05       0  5860.4      .1       0  6233.4     .16       0
  6338.2      .1       0
Bank Sta=4970.3,5043.7
XS Rating Curve= 0 ,0
Exp/Cntr=0.3,0.1