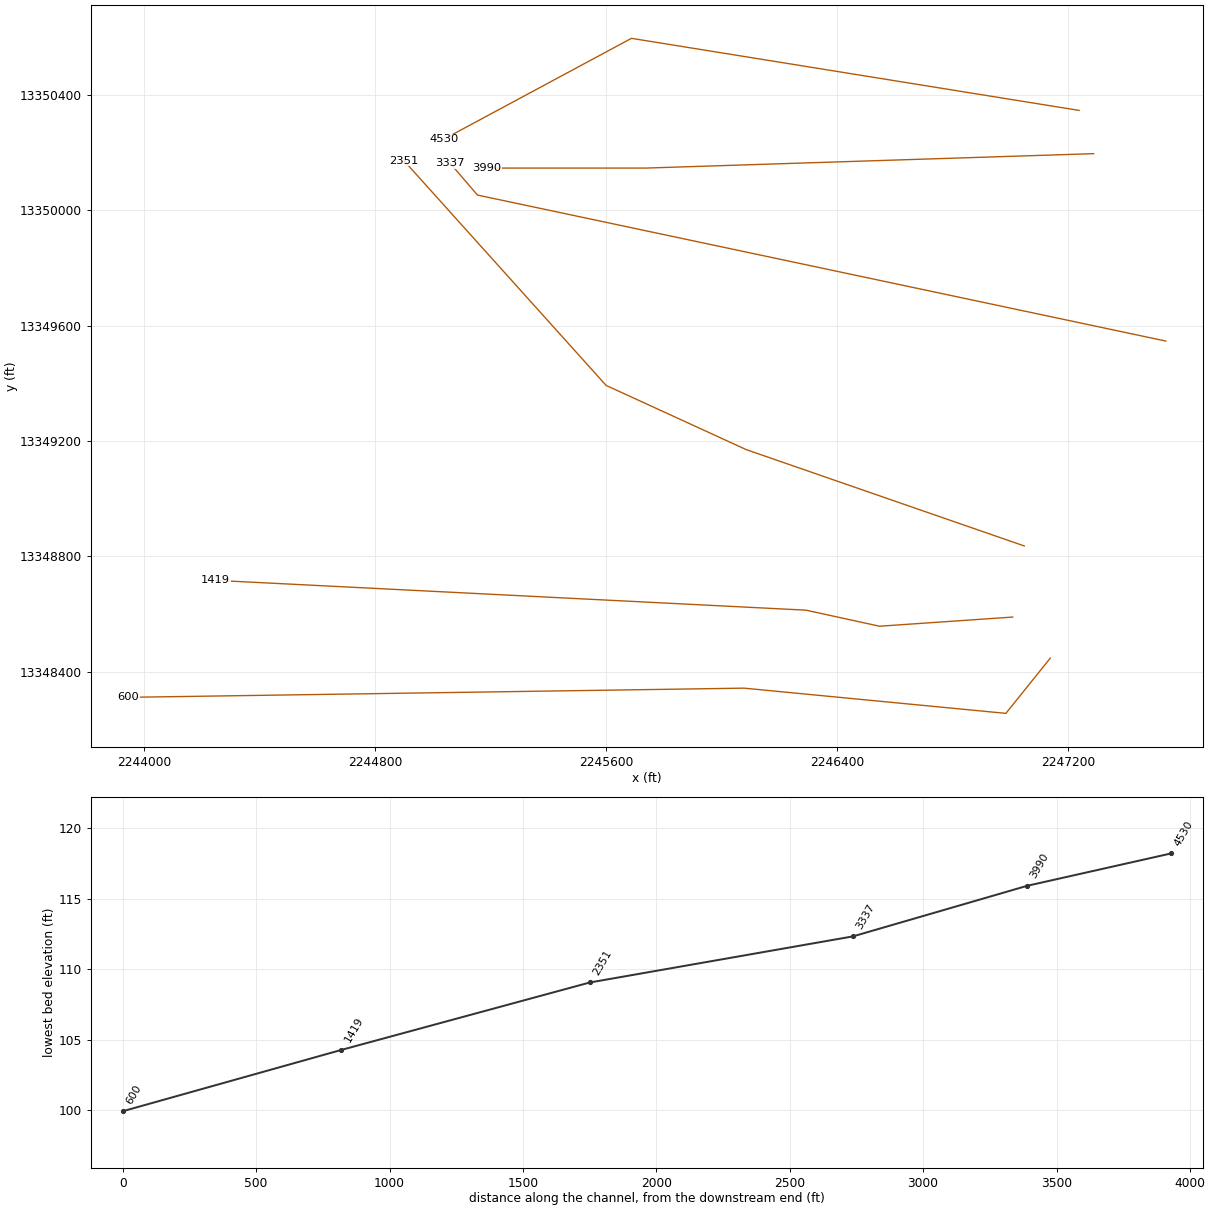
HEC-RAS study ROCK QUARRY BRANCH.prj: ROCK QUARRY BRANCH Base Level Engineering

--- ROCK QUARRY BRANCH.g01 (geometry) --- (continued)

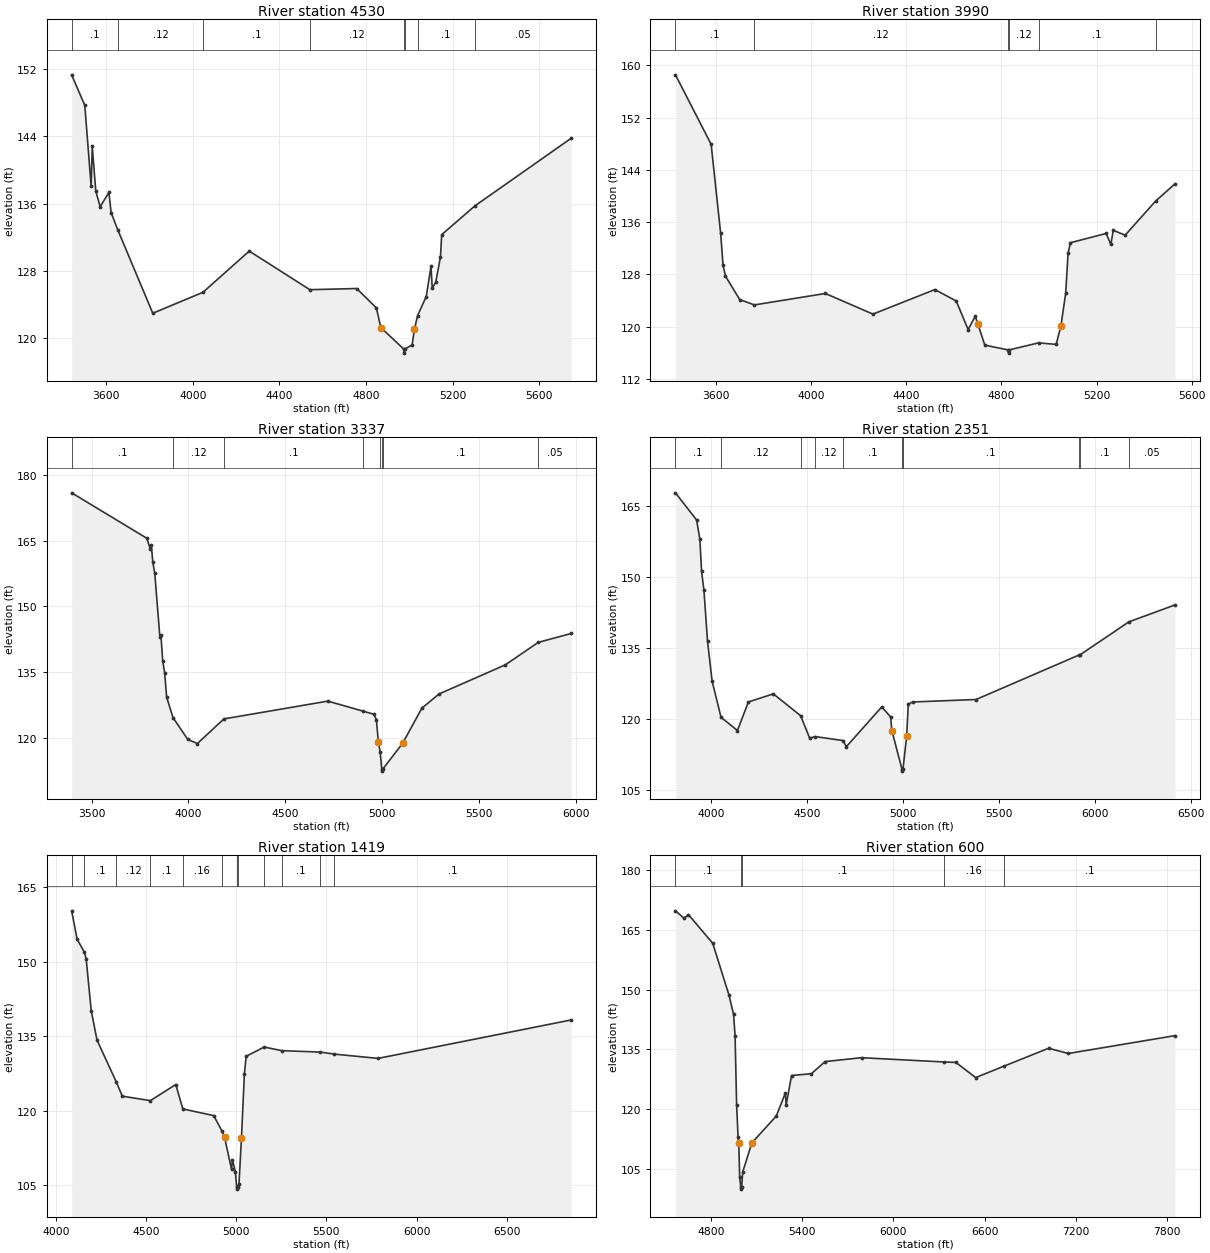
Type RM Length L Ch R = 1 ,4530    ,540,540,540
BEGIN DESCRIPTION:
ROCK QUARRY BRANCH 7.0
END DESCRIPTION:
XS GIS Cut Line= 3
      2247237.69     13350346.86      2245687.72     13350596.85
      2245037.76     13350246.88
#Sta/Elev= 30
  3439.9   151.3  3500.6  147.67    3530  138.06  3535.1  142.79  3551.3  137.49
  3571.6  135.62  3612.1  137.32  3622.2  134.93  3653.2  132.86  3814.7  122.96
  4046.6  125.45  4260.3  130.35  4540.2  125.76  4756.7   125.9  4847.8  123.59
  4868.1  121.26  4973.5  118.72  4976.2  118.22  4979.5  118.72  5012.7  119.19
  5023.7   121.1  5038.2  122.69  5078.1  124.95    5100  128.54  5105.6  125.96
  5121.9  126.65  5143.8  129.67  5149.4   132.3  5302.1  135.71  5748.1  143.77
#Mann= 8 ,-1 , 0
  3439.9      .1       0  3653.2     .12       0  4046.6      .1       0
  4540.2     .12       0  4973.5     .07       0  4979.5     .12       0
  5038.2      .1       0  5302.1     .05       0
Bank Sta=4868.1,5023.7
XS Rating Curve= 0 ,0
Exp/Cntr=0.3,0.1

Type RM Length L Ch R = 1 ,3990    ,653,653,653
BEGIN DESCRIPTION:
ROCK QUARRY BRANCH 6.0
END DESCRIPTION:
XS GIS Cut Line= 3
      2247287.72     13350196.85      2245737.72     13350146.85
      2245187.73     13350146.85
#Sta/Elev= 30
  3429.6  158.57  3579.7  147.92  3619.7  134.26  3629.7  129.42  3639.7  127.74
  3699.7  124.13  3761.4  123.31  4059.9  125.06    4260   121.9  4520.2  125.66
  4610.2  123.91  4660.2  119.53  4690.3  121.58  4700.3  120.45  4730.3  117.15
  4827.3  116.42  4830.1  115.92  4833.3  116.42  4956.1  117.49  5030.4  117.26
  5050.4  120.11  5070.4   125.1  5080.4  131.24  5090.4  132.84  5240.4  134.26
  5260.4  132.59  5270.4  134.74  5320.4     134  5448.7  139.23  5530.4  141.88
#Mann= 6 ,-1 , 0
  3429.6      .1       0  3761.4     .12       0  4827.3     .07       0
  4833.3     .12       0  4956.1      .1       0  5448.7     .05       0
Bank Sta=4700.3,5050.4
XS Rating Curve= 0 ,0
Exp/Cntr=0.3,0.1

Type RM Length L Ch R = 1 ,3337    ,986,986,986
BEGIN DESCRIPTION:
ROCK QUARRY BRANCH 5.0
END DESCRIPTION:
XS GIS Cut Line= 3
      2247537.73     13349546.85      2245154.44     13350053.28
      2245060.21     13350163.22
#Sta/Elev= 30
  3396.9  176.01  3785.4  165.61  3803.3  163.12  3808.4  164.12  3816.1  160.14
  3826.3   157.6  3852.9  142.91    3858  143.54  3867.2  137.61  3877.4  134.83
  3887.6  129.28  3920.4   124.6  3996.6  119.59  4046.3  118.64  4183.6  124.28
  4720.4  128.35  4902.9  126.05  4958.2  125.35  4971.3  124.09  4981.5  118.92
  4990.6  116.72    4999  112.83  5001.7  112.33    5005  112.83  5107.1  118.72
  5206.4  126.75  5295.3  129.99  5637.5  136.65  5807.3  141.79  5978.2  143.83
#Mann= 8 ,-1 , 0
  3396.9      .1       0  3920.4     .12       0  4183.6      .1       0
  4902.9     .12       0  4990.6      .1       0    4999     .07       0
    5005      .1       0  5807.3     .05       0
Bank Sta=4981.5,5107.1
XS Rating Curve= 0 ,0
Exp/Cntr=0.3,0.1

Type RM Length L Ch R = 1 ,2351    ,932,932,932
BEGIN DESCRIPTION:
ROCK QUARRY BRANCH 4.0
END DESCRIPTION:
XS GIS Cut Line= 4
      2247047.78     13348836.14      2246085.18     13349170.27
      2245599.92     13349393.01      2244900.25      13350172.2
#Sta/Elev= 30
  3816.2  167.77  3926.3  162.04  3943.3  157.97  3952.1  151.22  3964.5   147.2
  3983.2  136.43  4006.8  128.09  4053.4  120.42  4138.8  117.63  4195.8  123.65
  4325.6  125.36  4467.5  120.75  4514.9     116  4543.4  116.35  4688.4  115.51
  4705.4  114.21  4889.9  122.62  4935.8  120.49  4942.4  117.62  4994.4  109.56
  4997.1  109.06  5000.4  109.56  5019.4  116.43  5027.8  123.19  5050.8  123.65
  5380.4  124.17  5918.4  133.59  5923.1  133.63  6175.7  140.55  6416.3  144.13
#Mann= 10 ,-1 , 0
  3816.2      .1       0  4053.4     .12       0  4467.5      .1       0
  4543.4     .12       0  4688.4      .1       0  4994.4     .07       0
  5000.4      .1       0  5918.4     .05       0  5923.1      .1       0
  6175.7     .05       0
Bank Sta=4942.4,5019.4
XS Rating Curve= 0 ,0
Exp/Cntr=0.3,0.1

Type RM Length L Ch R = 1 ,1419    ,819,819,819
BEGIN DESCRIPTION:
ROCK QUARRY BRANCH 3.0
END DESCRIPTION:
XS GIS Cut Line= 4
      2247007.96     13348589.55      2246546.58     13348557.73
      2246292.02     13348613.41      2244247.59     13348716.83
#Sta/Elev= 30
  4088.1  160.19  4118.4  154.49  4158.7  151.88  4168.5  150.56  4196.7  140.11
  4228.7  134.21  4336.2  125.76    4369  122.95  4524.6  122.05  4665.3  125.29
  4704.6  120.38  4875.5  119.05  4920.7  116.01  4935.6  114.72  4974.5  108.25
  4979.5  110.16  4995.7   107.8  5002.7  104.77  5005.4  104.27  5008.7  104.77
  5015.7  105.22 5029.55  114.54  5045.8  127.45  5055.8  130.96  5155.5  132.82
    5254  132.09  5466.3  131.81  5544.1   131.4  5786.7  130.54  6858.2  138.27
#Mann= 12 ,-1 , 0
  4088.1     .16       0  4158.7      .1       0  4336.2     .12       0
  4524.6      .1       0  4704.6     .16       0  4920.7      .1       0
  5002.7     .07       0  5008.7      .1       0  5155.5     .16       0
    5254      .1       0  5466.3     .16       0  5544.1      .1       0
Bank Sta=4935.6,5029.55
XS Rating Curve= 0 ,0
Exp/Cntr=0.3,0.1

Type RM Length L Ch R = 1 ,600     ,0,0,0
BEGIN DESCRIPTION:
ROCK QUARRY BRANCH 1.0
END DESCRIPTION:
XS GIS Cut Line= 4
      2247137.73     13348446.87      2246984.11     13348255.43
      2246077.23     13348342.94      2243945.22     13348311.12
#Sta/Elev= 30
  4565.6  169.84  4622.4  167.98  4651.2  168.89  4811.1  161.68  4917.9  148.68
  4948.1  143.82  4958.1  138.49  4968.2  121.17  4977.6  113.11  4982.6  111.55
  4988.3  103.06  4995.3  100.42  4998.1   99.92  5001.3  100.42  5008.4  104.25
  5068.6  111.55  5229.4  118.28  5289.5  124.13  5294.5  121.07  5329.8  128.46
  5460.4  128.92  5550.9  131.97  5790.7  132.94  6333.7  131.87  6411.7  131.75
  6541.7  127.94  6726.5  130.79  7021.8  135.31  7151.8     134  7854.4  138.49
#Mann= 5 ,-1 , 0
  4565.6      .1       0  4995.3     .07       0  5001.3      .1       0
  6333.7     .16       0  6726.5      .1       0
Bank Sta=4982.6,5068.6
XS Rating Curve= 0 ,0
Exp/Cntr=0.3,0.1

Chan Stop Cuts=-1
Use User Specified Reach Order=0
Composite Channel Slope=5