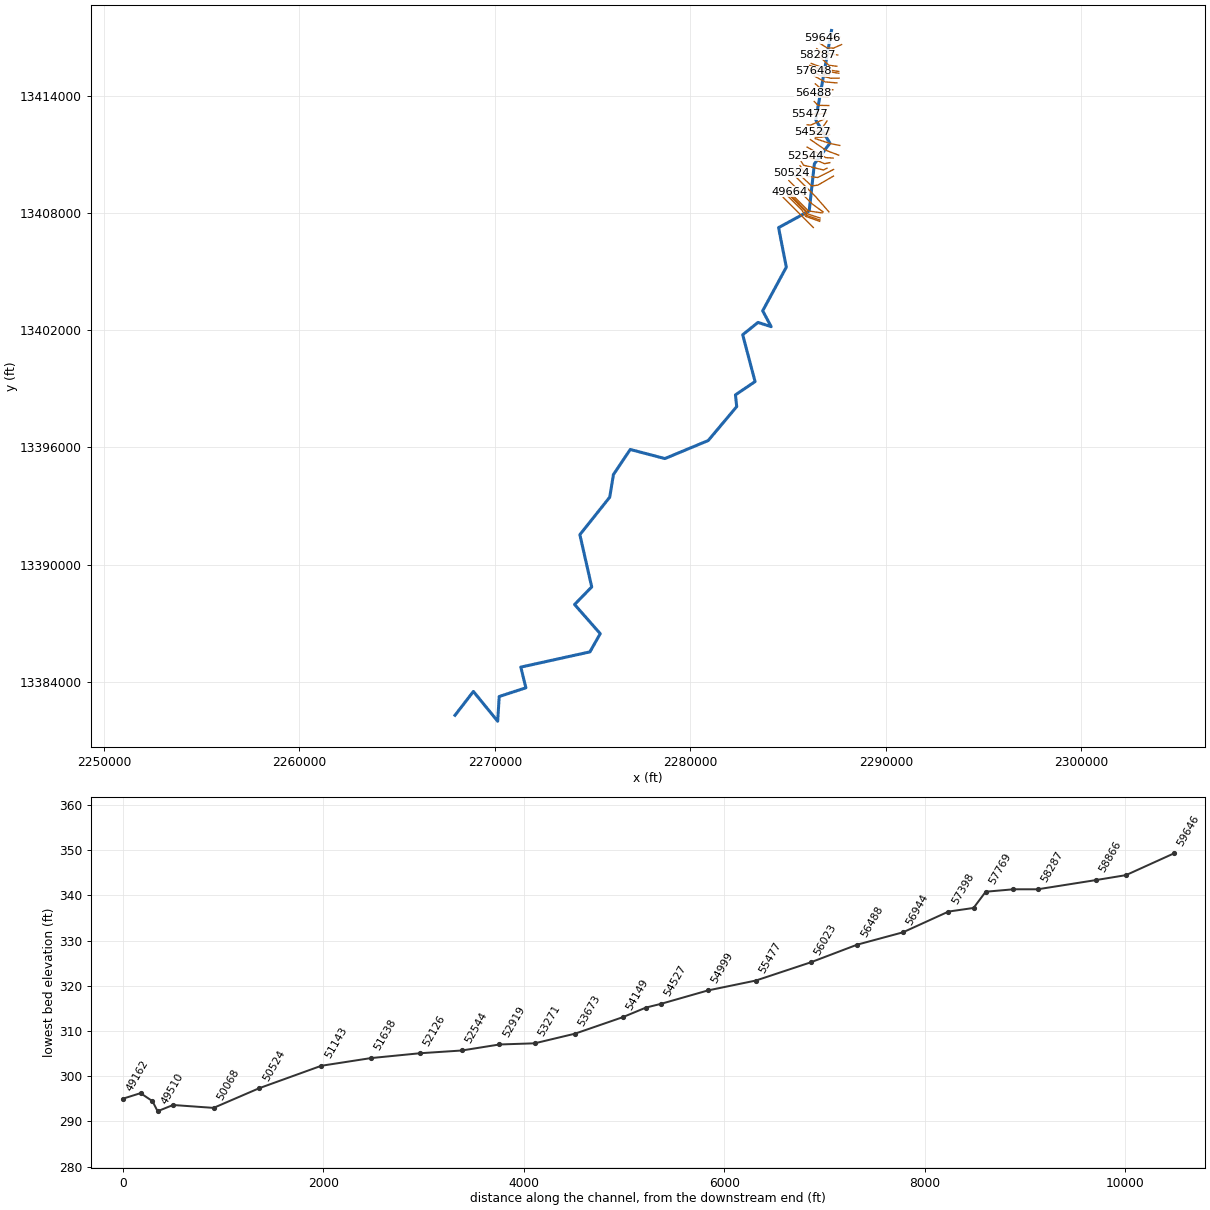
--- SALT CREEK.prj (project) ---

Proj Title=SALT CREEK Base Level Engineering
Current Plan=p01
Default Exp/Contr=0.3,0.1
English Units
Geom File=g01
Flow File=f01
Plan File=p01
Y Axis Title=Elevation
X Axis Title(PF)=Main Channel Distance
X Axis Title(XS)=Station
BEGIN DESCRIPTION:
SALT CREEK
END DESCRIPTION:
DSS Export Rating Curves= 0
DSS Export Rating Curve Sorted= 0
DSS Export Volume Flow Curves= 0
DXF OffsetX= 0
DXF OffsetY= 0
DXF ScaleX= 1
DXF ScaleY= 10

--- SALT CREEK.p01 (plan) ---

Plan Title=Multiple Run
Short Identifier=Multiple
Geom File=g01
Flow File=f01
Subcritical Flow
K Sum by GR= 0
Std Step Tol= 0.01
Critical Tol= 0.01
Num of Std Step Trials= 20
Max Error Tol= 0.3
Flow Tol Ratio= 0.001
Split Flow NTrial= 30
Split Flow Tol= 0.02
Split Flow Ratio= 0.02
Log Output Level= 0
Friction Slope Method= 1
Unsteady Friction Slope Method= 2
Unsteady Bridges Friction Slope Method= 1
Parabolic Critical Depth
Global Vel Dist=  1 , 1 , 1
Global Log Level= 0
CheckData=True
Encroach Param= -1, 0, 0, 0
BEGIN DESCRIPTION:
Multiple Run
END DESCRIPTION:

--- SALT CREEK.f01 (steady flow) ---

Flow Title=Multiple
Program Version=4.10
Number of Profiles= 7
Profile Names=10-year,25-year,50-year,1pct_min,100-year,1pct_plu,500-year
River Rch & RM=SALT CREEK,Reach-1         ,59646
     224     306     373     334     452     612     673
River Rch & RM=SALT CREEK,Reach-1         ,54149
     227     310     378     339     459     620     684
River Rch & RM=SALT CREEK,Reach-1         ,53673
     973    1428    1826    1706    2308    3121    3721
River Rch & RM=SALT CREEK,Reach-1         ,50524
    1893    2838    3678    3474    4699    6354    7727
River Rch & RM=SALT CREEK,Reach-1         ,47551
    1897    2849    3697    3498    4731    6398    7818
River Rch & RM=SALT CREEK,Reach-1         ,46983
    1859    2786    3609    3410    4611    6236    7598
River Rch & RM=SALT CREEK,Reach-1         ,43696
    1920    2879    3732    3528    4771    6452    7873
River Rch & RM=SALT CREEK,Reach-1         ,39327
    1903    2849    3689    3484    4712    6372    7767
River Rch & RM=SALT CREEK,Reach-1         ,32546
    1877    2803    3624    3418    4622    6251    7601
River Rch & RM=SALT CREEK,Reach-1         ,28505
    1870    2789    3604    3397    4594    6213    7548
River Rch & RM=SALT CREEK,Reach-1         ,27952
    3351    5095    6668    6354    8593   11621   14401
River Rch & RM=SALT CREEK,Reach-1         ,19927
    3234    4898    6394    6077    8218   11114   13700
River Rch & RM=SALT CREEK,Reach-1         ,16775
    3265    4945    6456    6138    8301   11227   13860
River Rch & RM=SALT CREEK,Reach-1         ,10931
    3222    4871    6352    6033    8159   11034   13596
Boundary for River Rch & Prof#=SALT CREEK,Reach-1         , 1
Up Type= 0
Dn Type= 3
Dn Slope=0.0049
Boundary for River Rch & Prof#=SALT CREEK,Reach-1         , 2
Up Type= 0
Dn Type= 3
Dn Slope=0.0049
Boundary for River Rch & Prof#=SALT CREEK,Reach-1         , 3
Up Type= 0
Dn Type= 3
Dn Slope=0.0049
Boundary for River Rch & Prof#=SALT CREEK,Reach-1         , 4
Up Type= 0
Dn Type= 3
Dn Slope=0.0049
Boundary for River Rch & Prof#=SALT CREEK,Reach-1         , 5
Up Type= 0
Dn Type= 3
Dn Slope=0.0049
Boundary for River Rch & Prof#=SALT CREEK,Reach-1         , 6
Up Type= 0
Dn Type= 3
Dn Slope=0.0049
Boundary for River Rch & Prof#=SALT CREEK,Reach-1         , 7
Up Type= 0
Dn Type= 3
Dn Slope=0.0049
DSS Import GetInterval= 0
DSS Import GetPeak= 0
DSS Import FillOption= 0

--- SALT CREEK.g01 (geometry) ---

Geom Title=Existing Conditions
Program Version=4.10

River Reach=SALT CREEK      ,Reach-1
Reach XY= 30
      2287217.72     13417328.29      2286409.02     13412753.91
      2287137.72     13411564.28      2286340.83     13410505.57
      2286075.61     13408094.41      2284508.94     13407242.96
       2284906.1     13405220.78      2283696.72     13402987.17
        2284131.     13402177.35      2283459.13     13402393.21
      2282673.87     13401763.14      2283307.23     13399366.73
      2282303.77     13398688.14      2282367.72     13398086.85
      2280910.54     13396351.41      2278694.89     13395429.16
      2276921.46     13395893.99      2276060.69     13394609.94
      2275872.96       13393454.      2274344.14     13391536.61
      2274950.95     13388863.62      2274074.65     13387963.88
      2275386.39     13386471.05      2274859.63     13385540.31
      2271323.35     13384760.53      2271583.54     13383703.66
       2270218.2     13383256.72      2270140.48     13381992.12
      2268897.76     13383515.82      2267957.72     13382296.86

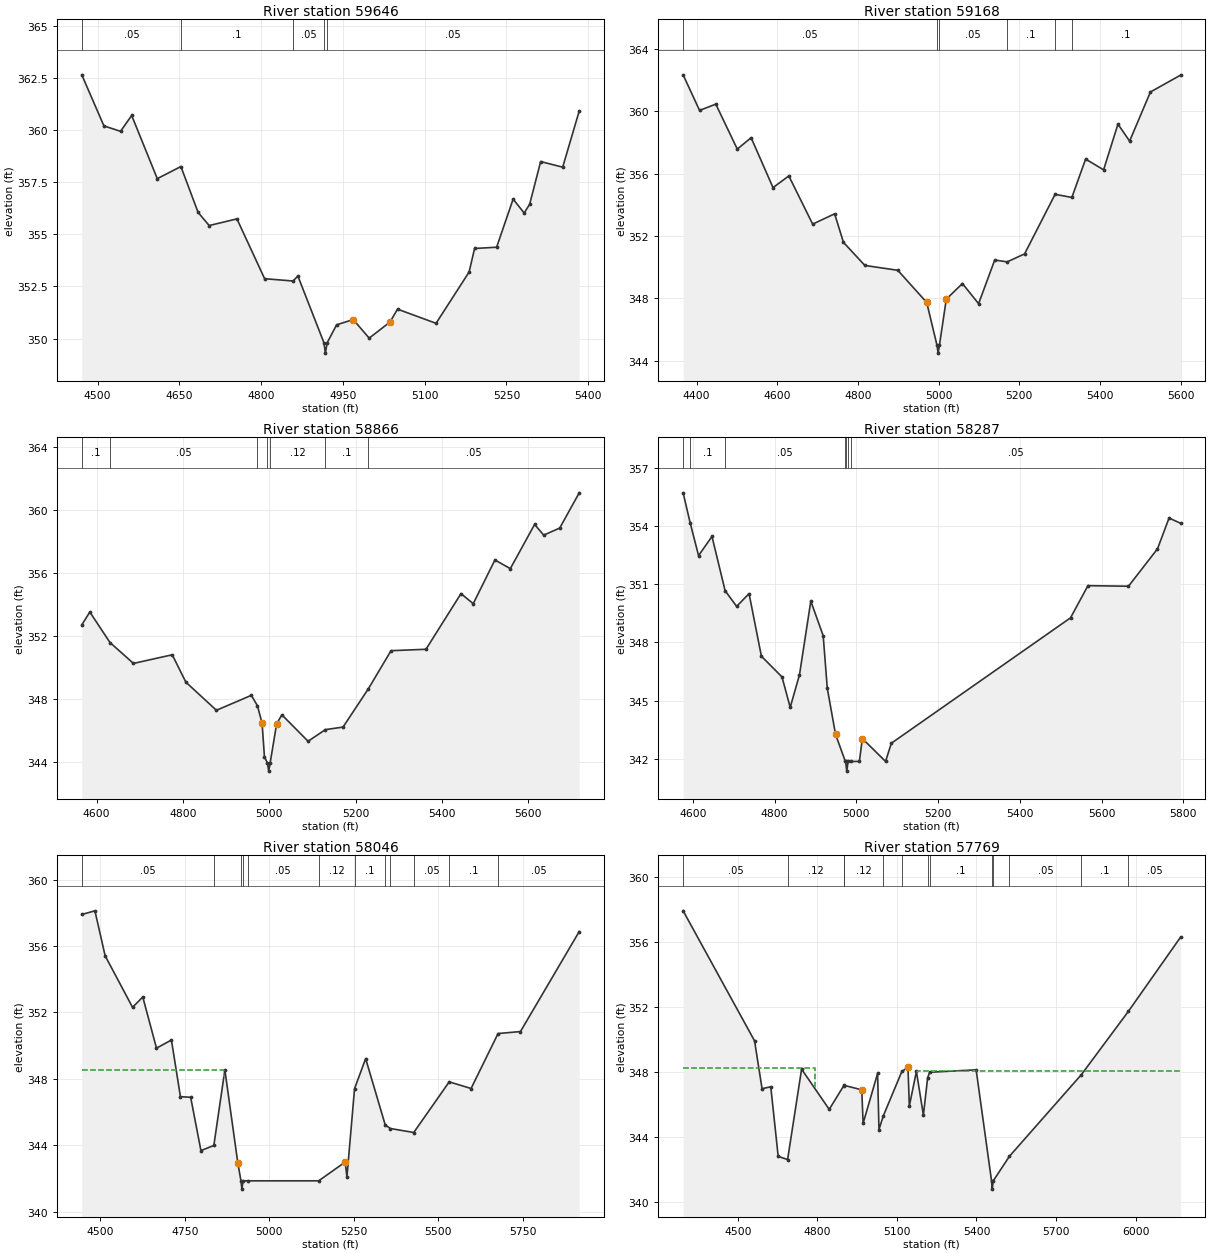
Type RM Length L Ch R = 1 ,59646   ,478,478,478
BEGIN DESCRIPTION:
SALT CREEK 91.0
END DESCRIPTION:
XS GIS Cut Line= 3
       2287637.7     13416996.85      2287087.72     13416896.85
      2286737.77     13416946.85
#Sta/Elev= 30
  4470.9  362.65  4511.5   360.2    4542  359.94  4562.4   360.7  4609.4  357.67
  4652.7  358.25  4684.3  356.05  4704.6  355.42  4755.5  355.74  4806.3  352.87
  4858.4  352.76  4867.3     353  4915.1   349.8  4917.8   349.3  4921.1   349.8
  4938.4  350.66  4968.9  350.91  4998.1  350.02  5036.3  350.79  5050.1  351.41
  5120.8  350.73  5181.4  353.19  5191.5  354.32  5231.9  354.38  5262.2  356.69
  5282.4  356.02  5292.5  356.44  5312.7  358.49  5353.1  358.22  5383.4  360.91
#Mann= 5 ,-1 , 0
  4470.9     .05       0  4652.7      .1       0  4858.4     .05       0
  4915.1     .03       0  4921.1     .05       0
Bank Sta=4968.9,5036.3
XS Rating Curve= 0 ,0
Exp/Cntr=0.3,0.1

Type RM Length L Ch R = 1 ,59168   ,302,302,302
BEGIN DESCRIPTION:
SALT CREEK 90.0
END DESCRIPTION:
XS GIS Cut Line= 4
      2287731.95     13416607.33      2287315.28     13416425.04
      2286981.94     13416440.66      2286606.94     13416680.25
#Sta/Elev= 30
  4366.4  362.33  4407.1  360.05  4447.4  360.45  4500.7  357.57    4535   358.3
  4589.3   355.1  4628.5  355.85  4687.6  352.76  4742.1  353.42    4764  351.59
  4817.1  350.11  4898.8   349.8  4970.4  347.74    4996  344.99  4998.7  344.49
    5002  344.99    5019  347.95    5059  348.95  5099.1  347.66  5139.1  350.46
  5169.9  350.34  5213.1  350.85  5288.8  354.67  5330.4  354.47  5364.5  356.93
  5409.1  356.24  5444.7  359.17  5473.6  358.08  5525.2  361.23  5599.9  362.31
#Mann= 6 ,-1 , 0
  4366.4     .05       0    4996     .03       0    5002     .05       0
  5169.9      .1       0  5288.8     .05       0  5330.4      .1       0
Bank Sta=4970.4,5019
XS Rating Curve= 0 ,0
Exp/Cntr=0.3,0.1

Type RM Length L Ch R = 1 ,58866   ,579,579,579
BEGIN DESCRIPTION:
SALT CREEK 89.0
END DESCRIPTION:
XS GIS Cut Line= 3
      2287536.14      13416070.5      2286733.17     13416189.86
      2286462.31     13416395.71
#Sta/Elev= 30
  4565.9  352.69  4584.5  353.51  4631.2  351.57  4685.6  350.24  4775.4  350.79
  4806.9  349.05  4877.7  347.26  4958.6  348.21  4972.7  347.55  4983.5  346.43
  4988.9  344.31    4996  343.89  4998.8  343.39    5002  343.89 5017.26  346.41
  5029.4  346.97    5090  345.29  5130.1  346.03  5170.9  346.19  5229.9  348.64
  5282.1  351.05    5363  351.14  5444.1  354.68  5472.5  354.04  5522.7  356.82
  5558.4  356.27  5614.6  359.08  5635.7   358.4  5672.8  358.85  5717.9  361.09
#Mann= 7 ,-1 , 0
  4565.9      .1       0  4631.2     .05       0  4972.7     .12       0
    4996     .07       0    5002     .12       0  5130.1      .1       0
  5229.9     .05       0
Bank Sta=4983.5,5017.26
XS Rating Curve= 0 ,0
Exp/Cntr=0.3,0.1

Type RM Length L Ch R = 1 ,58287   ,241,241,241
BEGIN DESCRIPTION:
SALT CREEK 88.0
END DESCRIPTION:
XS GIS Cut Line= 3
      2287487.74     13415496.85      2287087.72     13415546.85
       2286487.7     13416096.87
#Sta/Elev= 30
    4576  355.72  4593.2  354.17  4613.8  352.48  4646.6  353.47  4678.7  350.67
    4707  349.86  4737.3  350.52  4767.5  347.29  4817.9  346.22    4838  344.65
  4860.7  346.33  4888.4  350.13  4918.7  348.35  4928.7  345.64  4948.9  343.26
  4972.6  341.88  4973.6  341.86  4976.4  341.36  4979.6  341.86  4986.3  341.86
  5007.2  341.86  5014.6  343.04  5071.3  341.86  5085.5   342.8  5523.9  349.27
  5566.5  350.93  5665.7   350.9  5736.7  352.83    5765  354.42  5793.1  354.15
#Mann= 7 ,-1 , 0
    4576     .05       0  4593.2      .1       0  4678.7     .05       0
  4972.6     .12       0  4973.6    .035       0  4979.6     .12       0
  4986.3     .05       0
Bank Sta=4948.9,5014.6
XS Rating Curve= 0 ,0
Exp/Cntr=0.3,0.1

Type RM Length L Ch R = 1 ,58046   ,277,277,277
BEGIN DESCRIPTION:
Mapping XS 5cbad8b4
END DESCRIPTION:
XS GIS Cut Line= 3
      2287586.08     13415232.33      2287070.48     13415310.45
       2286181.3     13415643.25
#Sta/Elev= 30
  4445.4   357.9  4484.2  358.12  4514.5  355.41  4595.5  352.31  4625.8  352.93
  4666.3  349.85  4710.5  350.34  4737.1  346.93  4767.4  346.89  4797.7  343.68
  4835.9  343.99  4868.5  348.54  4906.7  342.95  4916.1  341.86  4918.9  341.36
  4922.1  341.86  4935.7  341.86  5145.9  341.86  5224.2  342.99  5229.5   342.1
    5252  347.41  5284.8  349.22  5342.8  345.22  5358.1  345.01    5427  344.77
  5531.9  347.82  5596.5  347.42  5676.4  350.73  5742.6  350.85  5916.3  356.87
#Mann= 12 ,-1 , 0
  4445.4     .05       0  4835.9     .12       0  4916.1    .033       0
  4922.1     .12       0  4935.7     .05       0  5145.9     .12       0
    5252      .1       0  5342.8     .05       0  5358.1      .1       0
    5427     .05       0  5531.9      .1       0  5676.4     .05       0
#XS Ineff= 2 , 0
         4865.45  348.54
Permanent Ineff=
       F       F
Bank Sta=4906.7,5224.2
XS Rating Curve= 0 ,0
Exp/Cntr=0.3,0.1

Type RM Length L Ch R = 1 ,57769   ,121,121,121
BEGIN DESCRIPTION:
SALT CREEK 87.0
END DESCRIPTION:
XS GIS Cut Line= 6
      2287591.32     13415138.58      2287148.61      13415211.5
      2287101.73     13415034.41       2286830.9     13415081.29
      2286825.69      13415279.2      2286102.25     13415544.64
#Sta/Elev= 30
  4294.1  357.92  4563.4  349.93  4591.7  346.99  4624.5  347.11  4652.5  342.83
    4688  342.64  4740.7  348.19  4844.9  345.72  4899.2  347.16  4900.3   347.2
  4967.6  346.92  4972.6  344.86  5027.3  347.93  5032.4  344.48    5049  345.33
  5118.7  348.05  5141.8   348.3  5146.9  345.93  5173.6  348.05  5199.9  345.37
    5216  347.67  5223.6     348  5398.8  348.15  5456.9  341.32  5459.6  340.82
  5462.9  341.32  5524.4  342.84  5795.8  347.86  5972.6  351.74  6169.4   356.3
#Mann= 13 ,-1 , 0
  4294.1     .05       0    4688     .12       0  4899.2     .05       0
  4900.3     .12       0    5049     .05       0  5118.7      .1       0
    5216     .05       0  5223.6      .1       0  5456.9     .07       0
  5462.9      .1       0  5524.4     .05       0  5795.8      .1       0
  5972.6     .05       0
#XS Ineff= 2 , 0
       0 4792.61  348.26 5174.72       0  348.09
Permanent Ineff=
       T       T
Bank Sta=4967.6,5141.8
XS Rating Curve= 0 ,0
Exp/Cntr=0.3,0.1

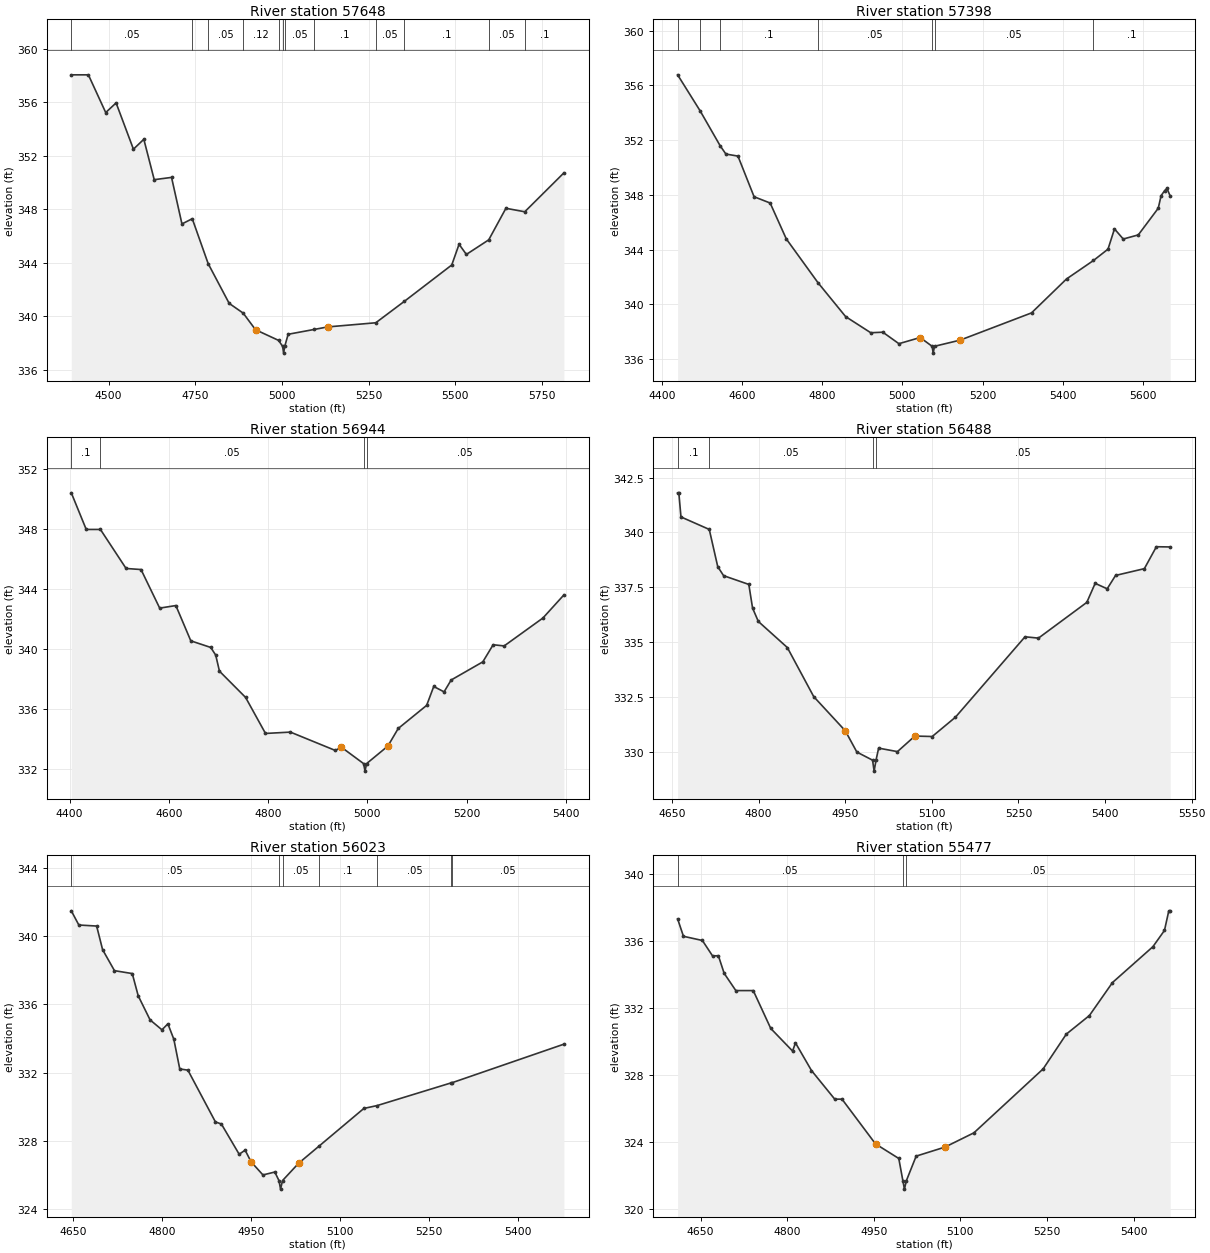
Type RM Length L Ch R = 1 ,57648   ,250,250,250
BEGIN DESCRIPTION:
Mapping XS 22848319
END DESCRIPTION:
XS GIS Cut Line= 4
      2287606.98     13414888.58      2287185.07     13414883.37
       2286580.9     13415039.62      2286268.37     13415247.97
#Sta/Elev= 30
  4392.3  358.04  4441.6  358.04  4491.6  355.22  4521.6  355.94  4571.6  352.48
  4601.6  353.22  4631.6   350.2  4681.6  350.37  4711.6  346.89  4741.4  347.28
  4787.3  343.92  4847.9  340.95  4888.4  340.22    4924  338.98  4990.7  338.18
  5002.2  337.73    5005  337.23  5008.2  337.73  5018.1  338.64    5093     339
  5132.3  339.19    5271   339.5  5353.8  341.11  5490.2  343.82  5511.3  345.37
  5532.4  344.61  5596.9   345.7  5646.5  348.06  5700.9   347.8  5813.9  350.71
#Mann= 12 ,-1 , 0
  4392.3     .05       0  4741.4      .1       0  4787.3     .05       0
  4888.4     .12       0  4990.7     .05       0  5002.2    .035       0
  5008.2     .05       0    5093      .1       0    5271     .05       0
  5353.8      .1       0  5596.9     .05       0  5700.9      .1       0
Bank Sta=4924,5132.3
XS Rating Curve= 0 ,0
Exp/Cntr=0.3,0.1

Type RM Length L Ch R = 1 ,57398   ,454,454,454
BEGIN DESCRIPTION:
SALT CREEK 86.0
END DESCRIPTION:
XS GIS Cut Line= 3
      2287487.74     13414646.85      2286887.72     13414696.85
      2286337.72     13414996.86
#Sta/Elev= 30
  4439.4  356.77  4495.7  354.13  4545.6  351.58  4559.8  350.98  4589.9  350.83
  4630.1  347.86  4670.2   347.4  4710.4  344.78  4789.4  341.58  4858.4   339.1
  4921.1  337.92  4951.2  337.96  4991.3  337.12  5044.3  337.57  5074.1  336.93
  5076.8  336.43  5080.1  336.93    5144  337.38    5322  339.37  5409.3  341.85
  5476.5   343.2  5512.8  344.03  5528.9  345.51  5550.8  344.77  5588.3  345.07
  5638.1  347.02  5645.2  347.94  5654.2  348.31  5659.9  348.47    5668   347.9
#Mann= 7 ,-1 , 0
  4439.4      .1       0  4495.7     .05       0  4545.6      .1       0
  4789.4     .05       0  5074.1    .035       0  5080.1     .05       0
  5476.5      .1       0
Bank Sta=5044.3,5144
XS Rating Curve= 0 ,0
Exp/Cntr=0.3,0.1

Type RM Length L Ch R = 1 ,56944   ,456,456,456
BEGIN DESCRIPTION:
SALT CREEK 85.0
END DESCRIPTION:
XS GIS Cut Line= 3
       2287287.7     13414296.86      2286687.72     13414346.85
       2286387.7     13414596.87
#Sta/Elev= 30
  4403.5  350.38  4433.6  347.94  4462.2  347.94  4513.9  345.34    4544  345.27
  4581.6   342.7  4614.2  342.87  4644.3  340.52  4684.4  340.08  4694.5  339.57
    4702   338.5  4754.7  336.75  4794.8  334.35    4845  334.44  4935.3  333.22
  4947.9  333.43  4992.5  332.34  4995.3  331.84  4998.5  332.34  5041.4  333.51
  5062.2  334.68  5119.5  336.22  5133.8  337.48  5154.6  337.12  5168.9  337.91
  5232.7  339.12  5253.5  340.26  5275.7  340.18  5353.8  342.04  5396.1  343.58
#Mann= 4 ,-1 , 0
  4403.5      .1       0  4462.2     .05       0  4992.5    .035       0
  4998.5     .05       0
Bank Sta=4947.9,5041.4
XS Rating Curve= 0 ,0
Exp/Cntr=0.3,0.1

Type RM Length L Ch R = 1 ,56488   ,465,465,465
BEGIN DESCRIPTION:
SALT CREEK 84.0
END DESCRIPTION:
XS GIS Cut Line= 3
      2287036.98     13413911.21       2286418.5     13413965.46
      2286277.42     13414149.94
#Sta/Elev= 30
  4659.8  341.81  4661.9  341.81  4665.6  340.71  4714.6  340.14  4729.3  338.44
  4739.4  338.03  4783.1  337.63  4789.6  336.55  4799.6  335.94  4849.8  334.75
  4895.5  332.51  4950.2  330.95  4970.2  329.98  4997.4  329.61  5000.1  329.11
  5003.4  329.61  5007.9  330.16  5040.5     330  5070.6  330.71  5100.7  330.69
  5140.9  331.57  5261.4  335.24  5284.7  335.18  5368.4  336.81  5382.9  337.68
  5403.7  337.43  5418.2  338.04  5468.1  338.35  5488.9  339.35  5512.9  339.34
#Mann= 4 ,-1 , 0
  4659.8      .1       0  4714.6     .05       0  4997.4    .035       0
  5003.4     .05       0
Bank Sta=4950.2,5070.6
XS Rating Curve= 0 ,0
Exp/Cntr=0.3,0.1

Type RM Length L Ch R = 1 ,56023   ,546,546,546
BEGIN DESCRIPTION:
SALT CREEK 83.0
END DESCRIPTION:
XS GIS Cut Line= 3
      2287080.43     13413488.03        2286527.     13413498.88
      2286331.66     13413694.23
#Sta/Elev= 30
  4647.1  341.47  4659.8  340.64  4689.8  340.58  4699.8   339.2  4719.8  337.97
  4749.8   337.8  4759.8   336.5  4779.8  335.09  4799.8  334.51  4809.8  334.86
  4819.8  333.96  4829.8  332.22  4843.5  332.15  4889.9  329.12  4899.9     329
  4929.9  327.23  4939.9  327.47  4949.9  326.79  4969.9  326.02  4989.9  326.19
  4996.9  325.69  4999.6  325.19  5002.9  325.69  5029.9   326.7  5064.2   327.7
  5139.9  329.91  5162.5  330.08  5287.4  331.41  5288.1  331.41  5476.9  333.67
#Mann= 7 ,-1 , 0
  4647.1     .05       0  4996.9     .03       0  5002.9     .05       0
  5064.2      .1       0  5162.5     .05       0  5287.4      .1       0
  5288.1     .05       0
Bank Sta=4949.9,5029.9
XS Rating Curve= 0 ,0
Exp/Cntr=0.3,0.1

Type RM Length L Ch R = 1 ,55477   ,478,478,478
BEGIN DESCRIPTION:
SALT CREEK 82.0
END DESCRIPTION:
XS GIS Cut Line= 3
      2286937.75     13413096.86      2286537.72     13413046.85
      2286087.76     13413046.85
#Sta/Elev= 30
  4610.3   337.3  4620.4  336.26  4653.2  336.01  4670.8  335.09  4680.9   335.1
  4690.9  334.05  4711.1  333.02  4741.3  333.02  4771.6  330.76  4809.4  329.41
  4814.4   329.9  4842.1  328.25  4882.4  326.54    4895  326.54    4953  323.87
  4993.3     323  5000.4  321.67  5003.1  321.17  5006.4  321.67  5023.4  323.14
  5073.4  323.68  5123.4  324.53  5243.4  328.35  5283.4  330.42  5323.4  331.53
  5363.4   333.5  5433.4  335.64  5453.4  336.61  5460.9  337.78  5463.4  337.78
#Mann= 3 ,-1 , 0
  4610.3     .05       0  5000.4     .03       0  5006.4     .05       0
Bank Sta=4953,5073.4
XS Rating Curve= 0 ,0
Exp/Cntr=0.3,0.1

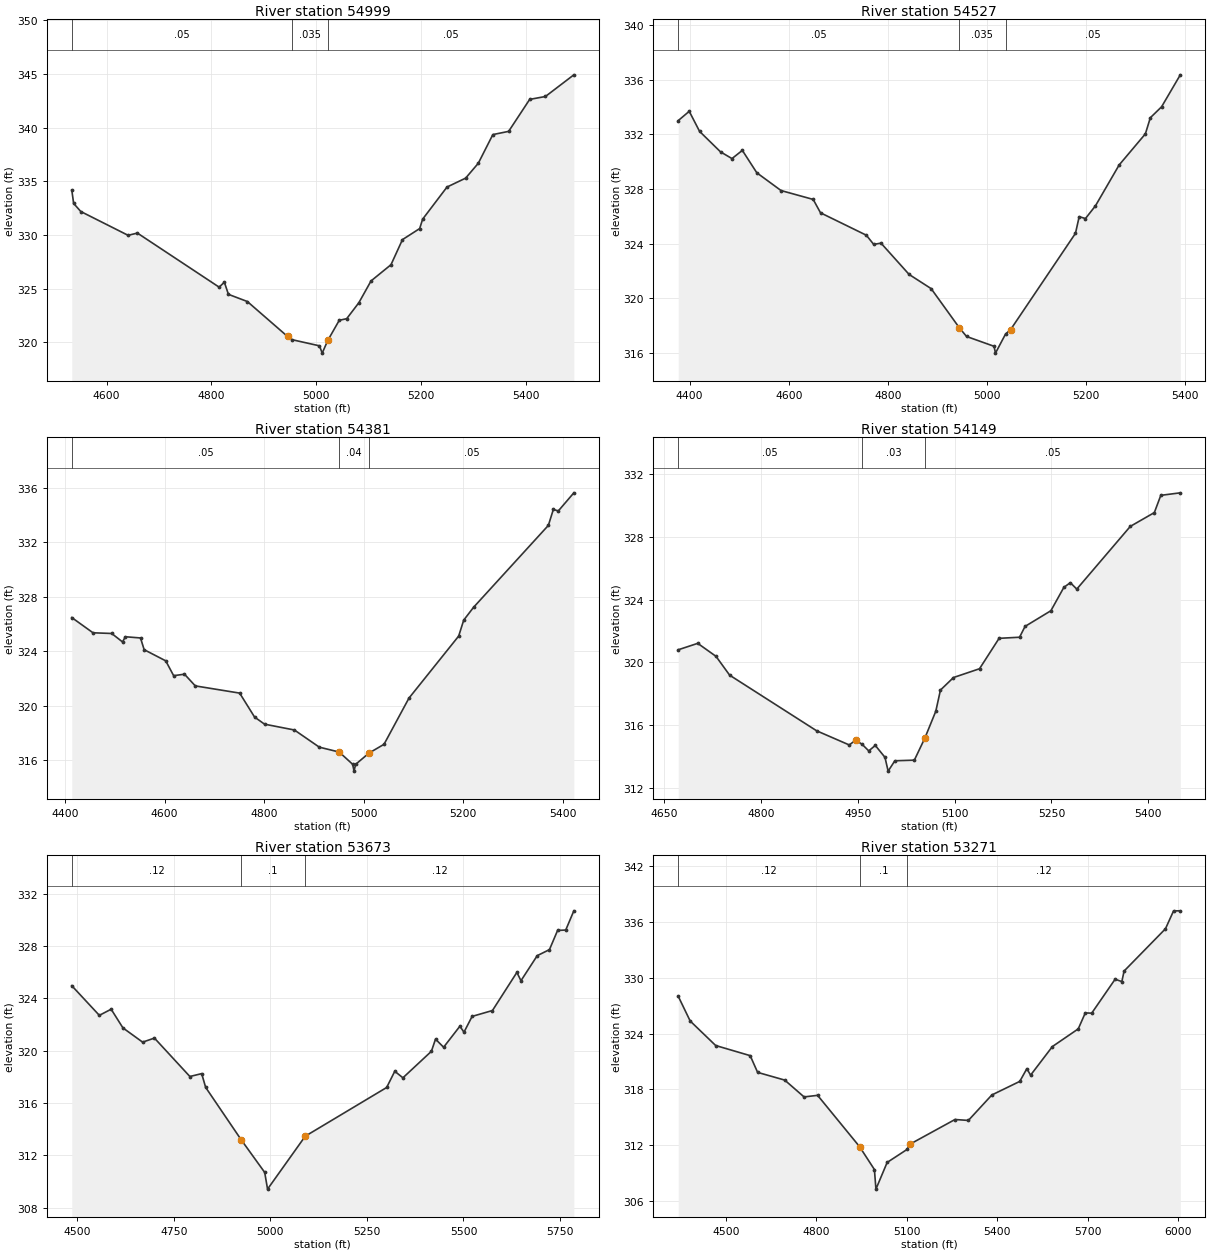
Type RM Length L Ch R = 1 ,54999   ,472,472,472
BEGIN DESCRIPTION:
SALT CREEK 81.0
END DESCRIPTION:
XS GIS Cut Line= 3
       2286863.4     13412804.45      2286158.08     13412489.77
      2285973.64     13412500.62
#Sta/Elev= 30
  4533.7  334.18  4537.3  332.93  4550.9  332.18  4641.1  329.96  4658.8  330.17
  4814.6  325.13  4824.6  325.59  4832.3  324.46  4868.4  323.79  4945.1  320.53
  4953.9  320.23  5005.9  319.66  5011.1  318.98  5021.7  320.16  5043.6  322.04
  5057.8  322.19    5081  323.68  5104.2  325.71  5142.2  327.22  5164.1  329.56
  5196.9  330.59  5202.6  331.47    5249  334.46  5284.5  335.29  5308.7  336.68
  5336.4  339.35  5366.5  339.65  5406.6  342.63  5436.6   342.9  5490.8  344.92
#Mann= 3 ,-1 , 0
  4533.7     .05       0  4953.9    .035       0  5021.7     .05       0
Bank Sta=4945.1,5021.7
XS Rating Curve= 0 ,0
Exp/Cntr=0.3,0.1

Type RM Length L Ch R = 1 ,54527   ,146,146,146
BEGIN DESCRIPTION:
SALT CREEK 80.0
END DESCRIPTION:
XS GIS Cut Line= 3
       2286987.7     13412696.82      2286637.72     13412196.85
      2286237.72     13412146.85
#Sta/Elev= 30
  4376.9  333.01  4399.1  333.69    4420  332.22  4462.3  330.72  4485.4  330.23
  4506.3  330.83  4535.5  329.19  4584.4  327.89  4649.3  327.24  4664.1  326.26
  4756.6  324.62  4771.4  323.95  4786.2  324.04  4842.9  321.75  4887.4  320.71
    4944  317.86  4958.8  317.21  5014.4  316.49  5017.2  315.99  5037.6  317.39
  5047.7  317.71  5178.7  324.76  5186.2  325.98  5198.8  325.84    5219  326.77
  5266.8  329.76  5319.8  332.04  5329.8  333.22  5352.5  334.02  5390.3  336.36
#Mann= 3 ,-1 , 0
  4376.9     .05       0    4944    .035       0  5037.6     .05       0
Bank Sta=4944,5047.7
XS Rating Curve= 0 ,0
Exp/Cntr=0.3,0.1

Type RM Length L Ch R = 1 ,54381   ,232,232,232
BEGIN DESCRIPTION:
Mapping XS 4ca30653
END DESCRIPTION:
XS GIS Cut Line= 3
      2287134.42     13412297.51      2287009.95     13412074.77
      2286256.52     13412042.01
#Sta/Elev= 30
  4413.3  326.47    4456  325.35  4493.6   325.3  4515.3  324.68  4521.1  325.06
  4551.5  324.97  4558.8  324.11  4602.2  323.29  4618.1   322.2  4639.9  322.31
  4661.6  321.45  4750.8  320.92  4780.8  319.16  4800.8  318.64  4860.9  318.21
  4910.9  316.95    4951  316.59    4978  315.69  4980.7  315.19    4984  315.69
    5011  316.52    5041  317.16  5091.1  320.55  5191.1  325.11  5201.2  326.28
  5221.2  327.23  5371.4  333.24  5381.4  334.41  5391.4   334.3  5422.6  335.63
#Mann= 3 , 0 , 0
  4413.3     .05       0    4951     .04       0    5011     .05       0
Bank Sta=4951,5011
XS Rating Curve= 0 ,0
Exp/Cntr=0.3,0.1

Type RM Length L Ch R = 1 ,54149   ,476,476,476
BEGIN DESCRIPTION:
SALT CREEK 79.0
END DESCRIPTION:
XS GIS Cut Line= 4
       2287121.3     13412015.78      2287013.22     13411914.26
      2286639.79     13411865.12      2286387.52     13411874.95
#Sta/Elev= 30
  4672.2   320.8  4702.4  321.21  4730.7  320.38  4751.8  319.18  4886.6  315.63
    4937  314.73  4947.1  315.04  4957.2  314.76  4967.2  314.35  4977.3   314.7
  4992.3  313.94  4997.2  313.06  5007.6  313.72  5037.8  313.76 5053.98  315.16
    5071  316.88  5078.2  318.23  5098.4  319.03  5138.7  319.59    5169  321.53
  5200.7   321.6  5209.2  322.29  5249.2  323.29  5269.3  324.78  5279.3  325.08
  5289.3  324.67  5372.2  328.67  5409.4  329.55  5419.4  330.65  5449.6  330.81
#Mann= 3 ,-1 , 0
  4672.2     .05       0  4957.2     .03       0 5053.98     .05       0
Bank Sta=4947.1,5053.98
XS Rating Curve= 0 ,0
Exp/Cntr=0.3,0.1

Type RM Length L Ch R = 1 ,53673   ,402,402,402
BEGIN DESCRIPTION:
SALT CREEK 78.0
END DESCRIPTION:
XS GIS Cut Line= 3
      2287637.69     13411446.86      2287137.72     13411546.85
      2286387.76     13411796.84
#Sta/Elev= 30
  4485.5  324.98  4556.9  322.71  4587.5  323.18    4618  321.75    4669  320.66
  4699.6  320.97  4791.4  318.03    4822  318.25  4832.2   317.2    4924   313.2
  4985.2  310.69  4992.6  309.41  5090.2  313.46  5301.1  317.19  5322.1  318.43
  5343.2  317.93    5417  319.96  5427.6  320.89  5448.6  320.27  5490.8  321.88
  5501.3  321.42  5522.4  322.63  5575.1  323.08  5638.4     326  5648.9  325.36
  5691.1  327.28  5722.7  327.74  5743.8  329.21  5764.9  329.24  5785.9  330.71
#Mann= 3 , 0 , 0
  4485.5     .12       0    4924      .1       0  5090.2     .12       0
Bank Sta=4924,5090.2
XS Rating Curve= 0 ,0
Exp/Cntr=0.3,0.1

Type RM Length L Ch R = 1 ,53271   ,352,352,352
BEGIN DESCRIPTION:
SALT CREEK 77.0
END DESCRIPTION:
XS GIS Cut Line= 3
      2287587.71     13410946.86      2286937.72     13411196.85
      2286137.75     13411746.84
#Sta/Elev= 30
  4340.9  328.03  4380.5  325.37  4465.2  322.73  4579.8  321.64  4604.5  319.84
  4694.5  319.01  4758.7   317.2  4803.7  317.37    4943  311.85  4992.3  309.39
  4997.4  307.28  5034.6  310.15  5101.6  311.57  5110.1  312.11  5259.9  314.77
  5304.3  314.67  5382.3  317.41    5475  318.87  5498.5  320.24  5510.9  319.54
  5583.4  322.62  5669.2  324.52  5692.6  326.24  5713.9  326.21  5791.6  329.86
    5814  329.61  5821.4  330.74  5958.8  335.29  5985.8  337.22  6008.1  337.22
#Mann= 3 ,-1 , 0
  4340.9     .12       0    4943      .1       0  5101.6     .12       0
Bank Sta=4943,5110.1
XS Rating Curve= 0 ,0
Exp/Cntr=0.3,0.1

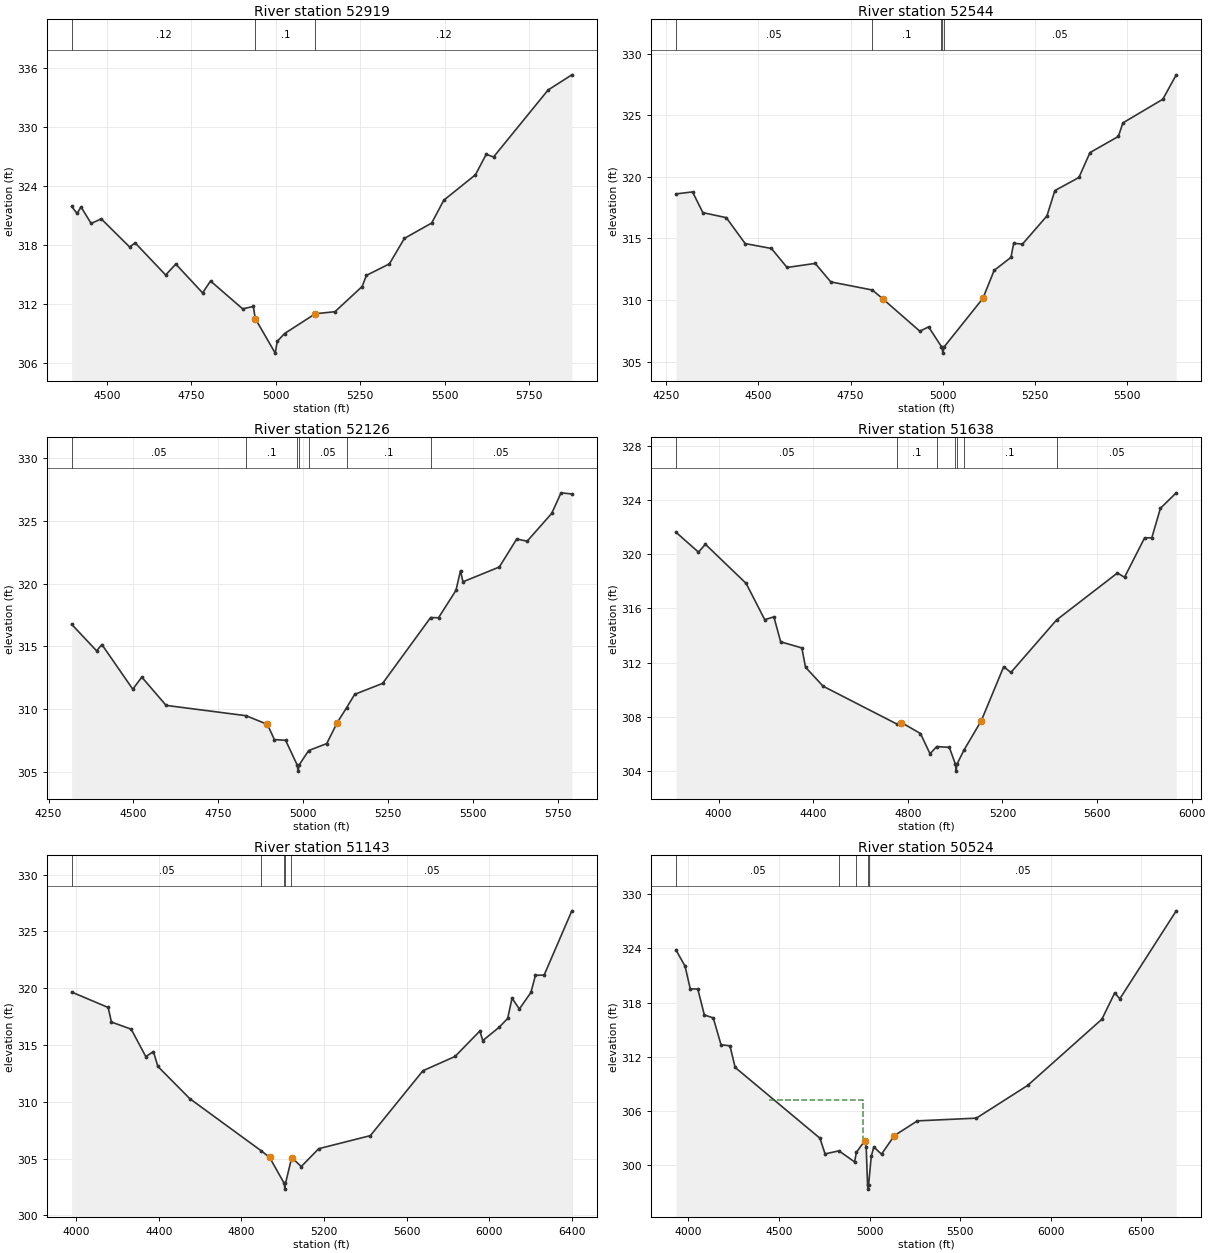
Type RM Length L Ch R = 1 ,52919   ,375,375,375
BEGIN DESCRIPTION:
SALT CREEK 76.0
END DESCRIPTION:
XS GIS Cut Line= 3
      2287305.17     13410800.54      2286914.59     13410826.58
       2285968.4     13411364.78
#Sta/Elev= 30
  4396.3  321.92  4412.4  321.21  4423.8  321.88  4453.9   320.2  4483.9  320.66
  4567.7  317.81  4584.2  318.22  4674.4  314.96  4704.4  316.07  4783.7  313.14
  4807.2  314.35  4902.2  311.52  4933.7  311.76  4939.7  310.52  4998.6  307.02
  5004.6  308.22  5026.2  309.01    5117  311.02  5175.3  311.23  5255.8  313.79
  5268.3  314.92  5336.4  316.09  5380.8  318.68  5461.5  320.24  5497.4  322.56
  5591.2  325.15  5622.9  327.23  5644.6  326.95    5806  333.76  5876.3   335.3
#Mann= 3 , 0 , 0
  4396.3     .12       0  4939.7      .1       0    5117     .12       0
Bank Sta=4939.7,5117
XS Rating Curve= 0 ,0
Exp/Cntr=0.3,0.1

Type RM Length L Ch R = 1 ,52544   ,418,418,418
BEGIN DESCRIPTION:
SALT CREEK 75.0
END DESCRIPTION:
XS GIS Cut Line= 3
      2287131.58     13410566.16      2286862.51     13410514.08
      2285864.24     13410930.75
#Sta/Elev= 30
  4276.7  318.61  4321.4  318.77  4349.4  317.09    4413  316.68    4464  314.58
  4535.3  314.18  4577.6  312.64  4653.9  312.97  4696.1  311.47  4808.9  310.81
  4837.7  310.08  4937.5  307.47  4961.3  307.82    4996  306.22  4997.2  306.19
    5000  305.69  5003.2  306.19  5108.6  310.14  5138.9   312.4  5184.5  313.46
  5191.9   314.6  5215.8  314.54    5282  316.82  5303.6  318.88  5368.7  319.94
  5398.7  321.96  5475.6  323.27  5487.9  324.37  5596.2  326.29  5632.5  328.27
#Mann= 5 ,-1 , 0
  4276.7     .05       0  4808.9      .1       0    4996     .05       0
  4997.2    .035       0  5003.2     .05       0
Bank Sta=4837.7,5108.6
XS Rating Curve= 0 ,0
Exp/Cntr=0.3,0.1

Type RM Length L Ch R = 1 ,52126   ,488,488,488
BEGIN DESCRIPTION:
SALT CREEK 74.0
END DESCRIPTION:
XS GIS Cut Line= 4
      2286984.03      13410279.7      2286801.74      13410192.9
      2285786.12     13410435.96      2285664.57     13410626.96
#Sta/Elev= 30
  4318.2  316.76  4391.6  314.65  4407.2  315.15  4498.1   311.6  4524.7  312.56
  4596.2  310.31  4831.4  309.49  4894.4   308.8    4915  307.59  4948.1  307.53
    4982  305.58  4984.8  305.08    4988  305.58  5016.1  306.72  5069.1  307.27
    5100  308.94  5127.5  310.12  5151.5  311.19  5233.7  312.06    5375   317.3
  5398.2  317.28  5449.6  319.46    5463  321.03  5470.2  320.14  5577.3  321.32
  5628.6  323.55  5659.1  323.37  5731.4  325.58    5759  327.22  5790.8  327.13
#Mann= 7 ,-1 , 0
  4318.2     .05       0  4831.4      .1       0    4982     .07       0
    4988      .1       0  5016.1     .05       0  5127.5      .1       0
    5375     .05       0
Bank Sta=4894.4,5100
XS Rating Curve= 0 ,0
Exp/Cntr=0.3,0.1

Type RM Length L Ch R = 1 ,51638   ,495,495,495
BEGIN DESCRIPTION:
Mapping XS bdbdf4a4
END DESCRIPTION:
XS GIS Cut Line= 4
      2287322.26     13410218.46      2286509.72     13409806.98
      2285957.64     13409864.27      2285608.66     13410411.18
#Sta/Elev= 30
  3820.2  321.61    3915  320.15  3944.2  320.73  4116.7  317.84  4195.2  315.17
  4233.8  315.38  4262.5  313.54  4352.1  313.09  4367.5  311.67  4441.8  310.27
  4752.8  307.49  4773.2  307.59  4853.6  306.78  4893.9  305.29  4922.3  305.82
  4975.6  305.76  5001.5  304.51  5004.2  304.01  5007.5  304.51  5037.1  305.55
  5110.8  307.73  5205.5  311.71  5235.7  311.28  5428.8  315.15    5686  318.61
  5716.2   318.3  5801.1   321.2  5831.6  321.21    5868  323.38  5934.8  324.52
#Mann= 7 ,-1 , 0
  3820.2     .05       0  4752.8      .1       0  4922.3     .05       0
  5001.5     .03       0  5007.5     .05       0  5037.1      .1       0
  5428.8     .05       0
Bank Sta=4773.2,5110.8
XS Rating Curve= 0 ,0
Exp/Cntr=0.3,0.1

Type RM Length L Ch R = 1 ,51143   ,619,619,619
BEGIN DESCRIPTION:
SALT CREEK 73.0
END DESCRIPTION:
XS GIS Cut Line= 4
      2287317.05     13409879.92      2286520.14     13409416.36
      2286197.22     13409374.69      2285343.14      13410181.9
#Sta/Elev= 30
  3978.2  319.66    4155   318.3  4170.8  317.02  4266.6  316.39  4337.1  313.98
  4374.3  314.41  4395.8  313.11  4550.6  310.27  4896.6  305.68  4936.6  305.11
  5007.9  302.81  5010.7  302.31  5013.9  302.81  5042.2  304.95  5043.7  305.09
  5090.3   304.3  5174.8  305.87    5425  307.02  5679.4  312.73  5835.2  313.99
  5955.3  316.23  5969.5  315.39  6047.6  316.54  6090.1  317.34  6111.1  319.12
  6146.7  318.17  6202.9  319.63  6224.4  321.13  6266.8  321.16  6400.9  326.81
#Mann= 5 ,-1 , 0
  3978.2     .05       0  4896.6      .1       0  5007.9     .07       0
  5013.9      .1       0  5042.2     .05       0
Bank Sta=4936.6,5043.7
XS Rating Curve= 0 ,0
Exp/Cntr=0.3,0.1

Type RM Length L Ch R = 1 ,50524   ,456,456,456
BEGIN DESCRIPTION:
SALT CREEK 72.0
END DESCRIPTION:
XS GIS Cut Line= 3
       2287087.7     13408046.88      2286387.72     13408846.85
      2285187.75     13410046.82
#Sta/Elev= 30
  3932.2  323.82    3982  322.04  4010.5  319.53  4052.2  319.51  4088.3  316.64
  4137.7  316.31  4180.4  313.34  4229.7  313.22  4258.2  310.83  4726.1  302.99
  4754.6  301.25  4831.1  301.59  4916.9  300.37  4927.9  301.44  4973.8  302.71
  4981.4  302.07  4988.9  297.85  4991.6  297.35  4994.9  297.85  5009.3  300.97
  5023.5  302.02  5065.9  301.22  5136.6  303.27  5263.9  304.91  5589.2  305.21
    5872  308.83  6282.1  316.17  6352.8  319.08  6381.1  318.43  6692.2  328.17
#Mann= 5 ,-1 , 0
  3932.2     .05       0  4831.1      .1       0  4927.9     .05       0
  4988.9     .03       0  4994.9     .05       0
#XS Ineff= 1 ,-1
 4446.49 4966.28307.2272
Permanent Ineff=
       F
Bank Sta=4973.8,5136.6
XS Rating Curve= 0 ,0
Exp/Cntr=0.3,0.1

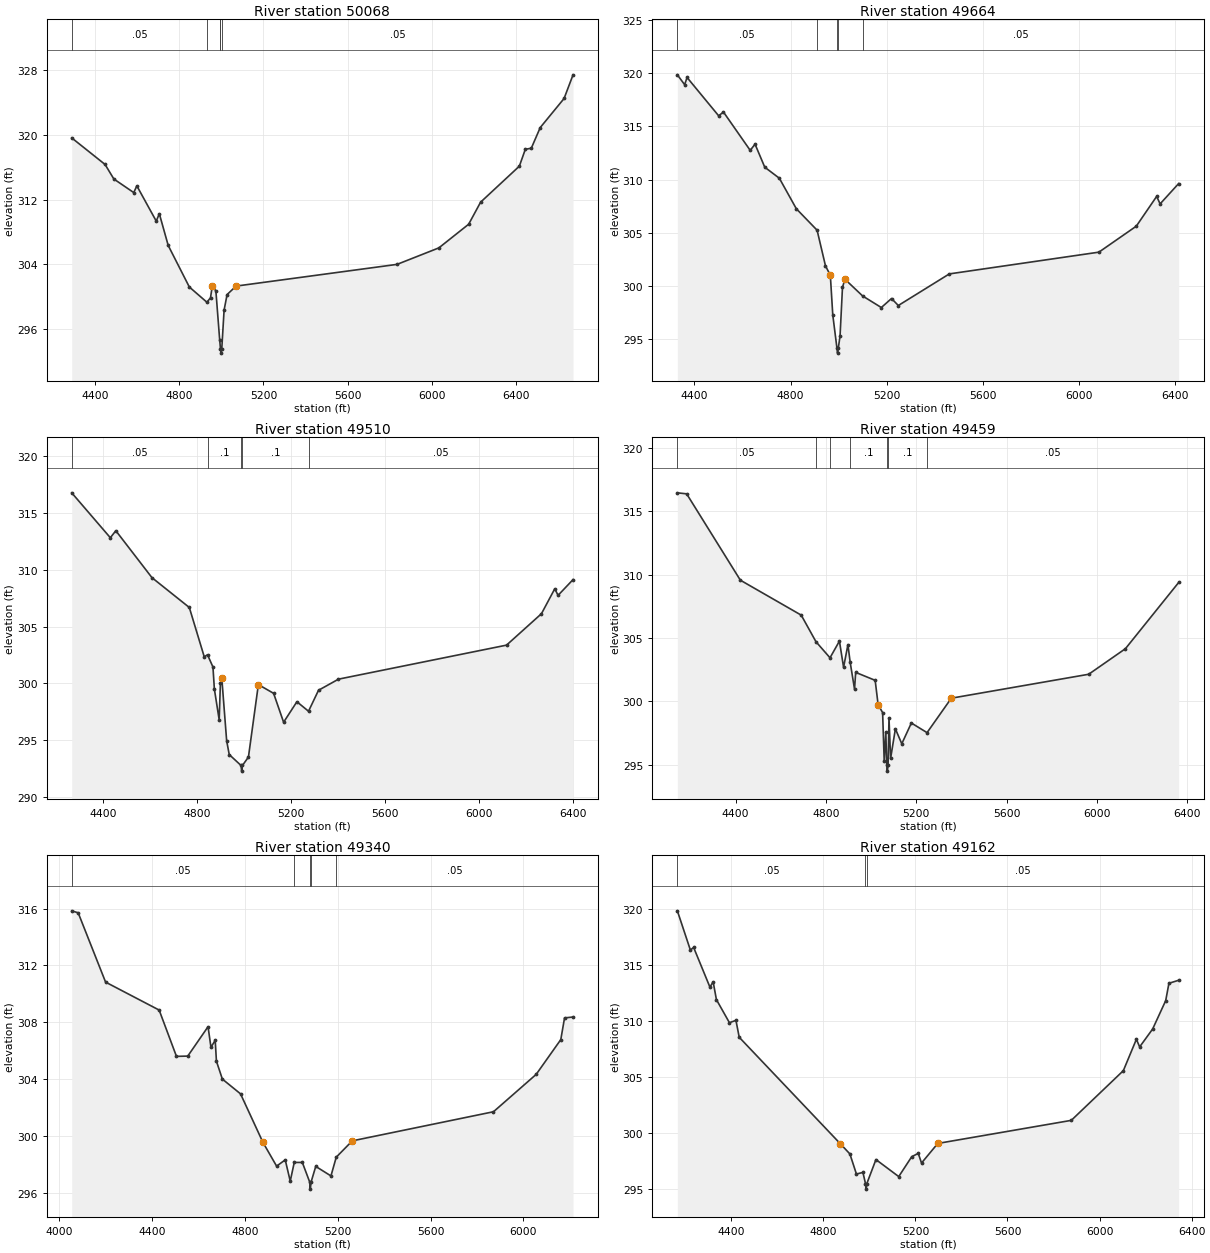
Type RM Length L Ch R = 1 ,50068   ,404,404,404
BEGIN DESCRIPTION:
SALT CREEK 71.0
END DESCRIPTION:
XS GIS Cut Line= 3
      2286787.74     13408046.84      2286237.72     13408446.85
      2285037.69     13409646.88
#Sta/Elev= 30
    4291  319.64  4449.1  316.35  4490.8  314.55  4585.1  312.87  4599.8   313.7
  4691.7  309.34  4706.4  310.25  4748.5  306.32  4848.6  301.18  4932.1  299.29
  4949.1  299.85  4957.6  301.32  4974.6  300.68  4992.5  294.65  4996.4  293.49
  4999.1  292.99  5002.4  293.49  5013.5  298.32  5027.7  300.24  5070.1  301.29
  5833.8  303.98  6031.8  306.02  6173.2  308.95  6229.8  311.68  6413.6  316.14
  6441.9  318.23  6470.2  318.36  6512.6  320.92  6625.7  324.52  6668.2  327.45
#Mann= 5 ,-1 , 0
    4291     .05       0  4932.1      .1       0  4992.5     .05       0
  4996.4     .03       0  5002.4     .05       0
Bank Sta=4957.6,5070.1
XS Rating Curve= 0 ,0
Exp/Cntr=0.3,0.1

Type RM Length L Ch R = 1 ,49664   ,154,154,154
BEGIN DESCRIPTION:
SALT CREEK 70.0
END DESCRIPTION:
XS GIS Cut Line= 3
      2286737.71     13407996.86      2286037.72     13408096.85
      2285063.05     13409071.53
#Sta/Elev= 30
    4329  319.87  4359.3  318.94  4369.4  319.62  4500.7  316.01  4520.9  316.36
    4632  312.75  4652.2  313.33  4692.6  311.16  4753.3  310.12    4824  307.24
  4910.3  305.22  4945.2  301.86  4965.4  300.97  4975.5  297.24  4992.7  294.13
  4995.4  293.63  4998.7  294.13  5005.8  295.24  5015.9  299.82    5026   300.6
  5099.7  299.02  5177.5  297.93  5219.9  298.78  5248.2  298.12  5460.4   301.1
  6082.6  303.15  6238.2   305.6    6323  308.41  6337.2   307.7  6414.5  309.62
#Mann= 5 ,-1 , 0
    4329     .05       0  4910.3      .1       0  4992.7     .07       0
  4998.7      .1       0  5099.7     .05       0
Bank Sta=4965.4,5026
XS Rating Curve= 0 ,0
Exp/Cntr=0.3,0.1

Type RM Length L Ch R = 1 ,49510   ,51,51,51
BEGIN DESCRIPTION:
Mapping XS 9c859605
END DESCRIPTION:
XS GIS Cut Line= 4
      2286633.55     13407734.07      2285970.37     13407952.82
      2285956.48     13408053.51      2285029.37      13409008.4
#Sta/Elev= 30
  4268.3  316.79  4432.4  312.83  4455.7  313.45  4609.3  309.31  4768.1  306.68
  4831.6  302.33  4845.4  302.51  4868.6  301.43  4874.6  299.49  4895.1  296.77
  4900.3  300.03  4906.2  300.44  4926.8  294.93  4937.8  293.71  4987.9  292.75
  4990.6  292.25  4993.9  292.75  5019.4  293.49  5061.6  299.88  5126.4  299.11
  5168.9  296.56  5225.4  298.37  5274.8  297.53  5317.3  299.38  5402.2  300.36
  6116.5  303.36  6264.9  306.13  6321.5  308.33  6335.6  307.75  6399.2  309.14
#Mann= 5 ,-1 , 0
  4268.3     .05       0  4845.4      .1       0  4987.9     .07       0
  4993.9      .1       0  5274.8     .05       0
Bank Sta=4906.2,5061.6
XS Rating Curve= 0 ,0
Exp/Cntr=0.3,0.1

Type RM Length L Ch R = 1 ,49459   ,119,119,119
BEGIN DESCRIPTION:
Mapping XS d3be0748
END DESCRIPTION:
XS GIS Cut Line= 4
      2286626.58     13407631.65      2285927.83     13407870.35
      2285910.47     13408039.62      2284990.31      13408972.8
#Sta/Elev= 30
  4142.5  316.46  4183.6  316.38  4421.4  309.56  4690.8   306.8  4756.1   304.7
  4818.2  303.43  4859.9  304.75  4878.3  302.68  4897.5  304.47  4907.3   303.1
  4926.8  300.95  4931.8  302.28  5018.1  301.65  5031.1  299.74  5051.1   299.1
  5058.1  295.28  5065.2  297.57  5069.3  294.98    5072  294.48  5075.3  294.98
  5079.3  298.68  5086.4  295.48  5107.6  297.82  5135.9  296.64  5178.3  298.28
  5247.8  297.52  5355.2  300.24  5963.2  302.13  6125.9  304.15  6361.6  309.38
#Mann= 7 ,-1 , 0
  4142.5     .05       0  4756.1      .1       0  4818.2     .05       0
  4907.3      .1       0  5069.3     .07       0  5075.3      .1       0
  5247.8     .05       0
Bank Sta=5031.1,5355.2
XS Rating Curve= 0 ,0
Exp/Cntr=0.3,0.1

Type RM Length L Ch R = 1 ,49340   ,178,178,178
BEGIN DESCRIPTION:
Mapping XS 189bbe49
END DESCRIPTION:
XS GIS Cut Line= 5
      2286612.74     13407563.92      2285890.51     13407820.87
       2285716.9     13408119.48      2285001.62     13408834.76
      2284981.73     13408864.59
#Sta/Elev= 30
  4054.2  315.85    4082  315.71    4200  310.83  4430.8  308.86  4505.3   305.6
  4554.1  305.62  4641.4  307.69  4653.9  306.24  4672.2  306.73  4677.5  305.26
    4703     304  4781.3  302.96  4877.9  299.54  4936.7  297.87  4973.9  298.31
  4995.4  296.81  5012.7  298.13  5047.5  298.13  5079.2  296.75  5081.9  296.25
  5085.2  296.75  5105.3  297.85  5170.8  297.18  5193.6   298.5  5262.7  299.65
  5870.9   301.7  6054.7  304.33  6160.8  306.78    6177  308.31  6213.6  308.37
#Mann= 5 ,-1 , 0
  4054.2     .05       0  5012.7      .1       0  5079.2     .03       0
  5085.2      .1       0  5193.6     .05       0
Bank Sta=4877.9,5262.7
XS Rating Curve= 0 ,0
Exp/Cntr=0.3,0.1

Type RM Length L Ch R = 1 ,49162   ,457,457,457
BEGIN DESCRIPTION:
SALT CREEK 69.0
END DESCRIPTION:
XS GIS Cut Line= 3
       2286287.7     13407246.88      2285687.72     13407846.85
      2284747.83     13408786.74
#Sta/Elev= 30
    4166  319.86  4222.5  316.36  4236.7  316.59  4307.4  313.05  4321.5  313.52
  4335.7  311.93  4392.2  309.87  4420.5  310.08  4434.7  308.57  4873.1  299.08
  4915.5  298.15  4943.8  296.36  4972.1   296.5  4983.2  295.51    4986  295.01
  4989.2  295.51  5028.6  297.65  5127.6  296.13  5184.2  297.91  5212.5   298.2
  5226.6  297.34  5297.3  299.09  5877.2  301.15  6103.4  305.59    6160  308.39
  6174.2  307.71  6230.7  309.31  6287.3  311.84  6301.4  313.39  6343.7  313.66
#Mann= 3 ,-1 , 0
    4166     .05       0  4983.2     .03       0  4989.2     .05       0
Bank Sta=4873.1,5297.3
XS Rating Curve= 0 ,0
Exp/Cntr=0.3,0.1