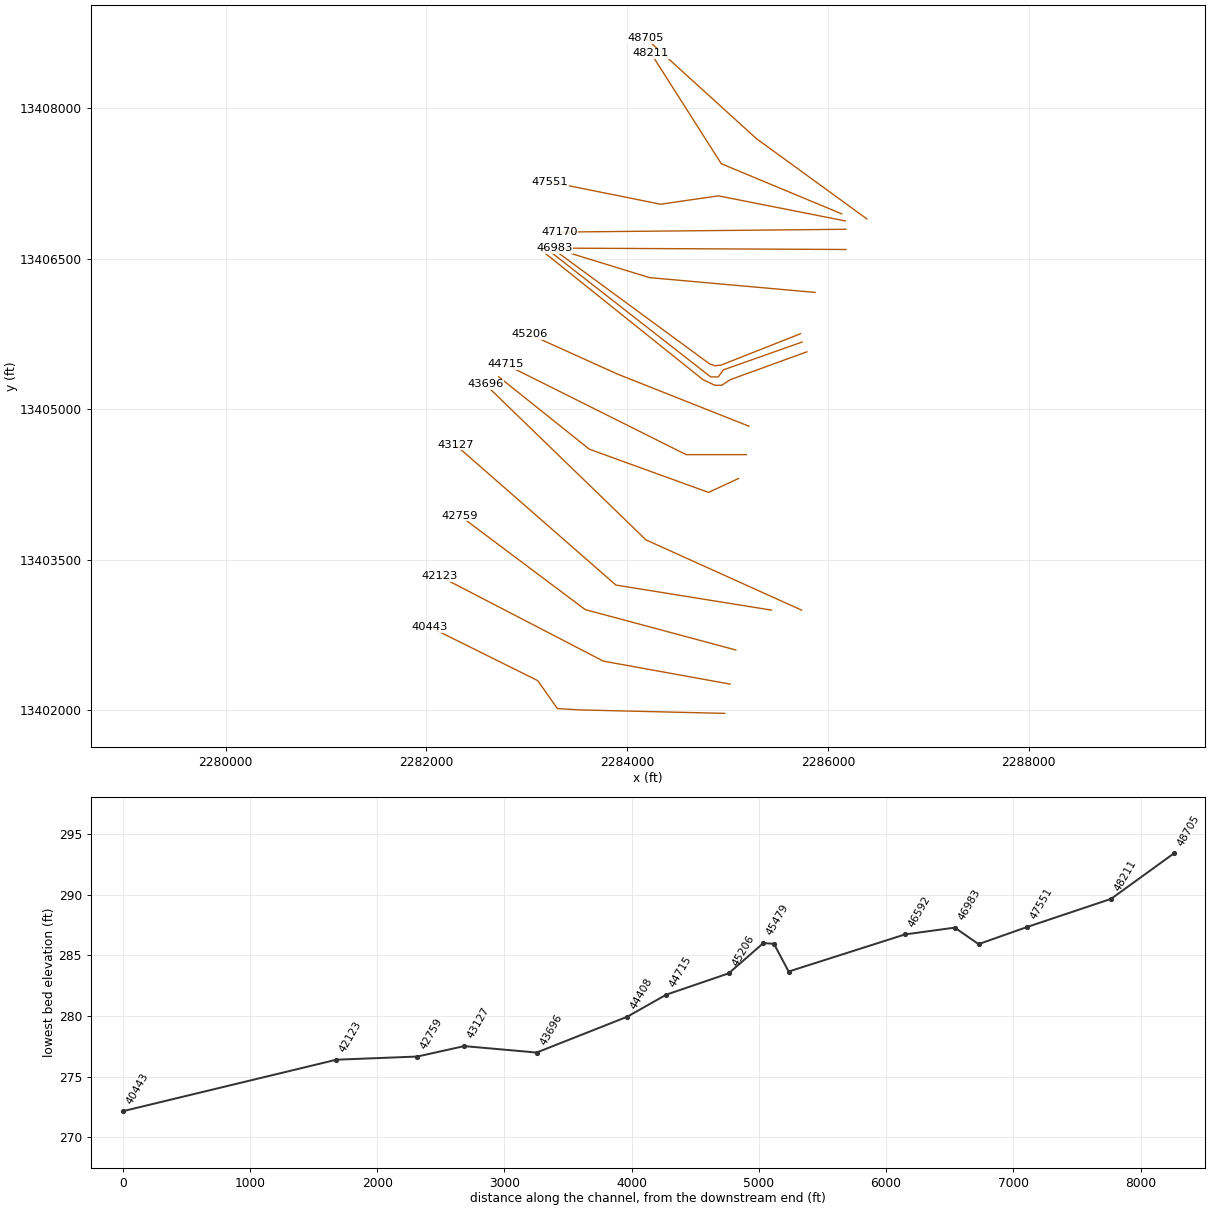
HEC-RAS study SALT CREEK.prj: SALT CREEK Base Level Engineering

--- SALT CREEK.g01 (geometry) --- (continued)

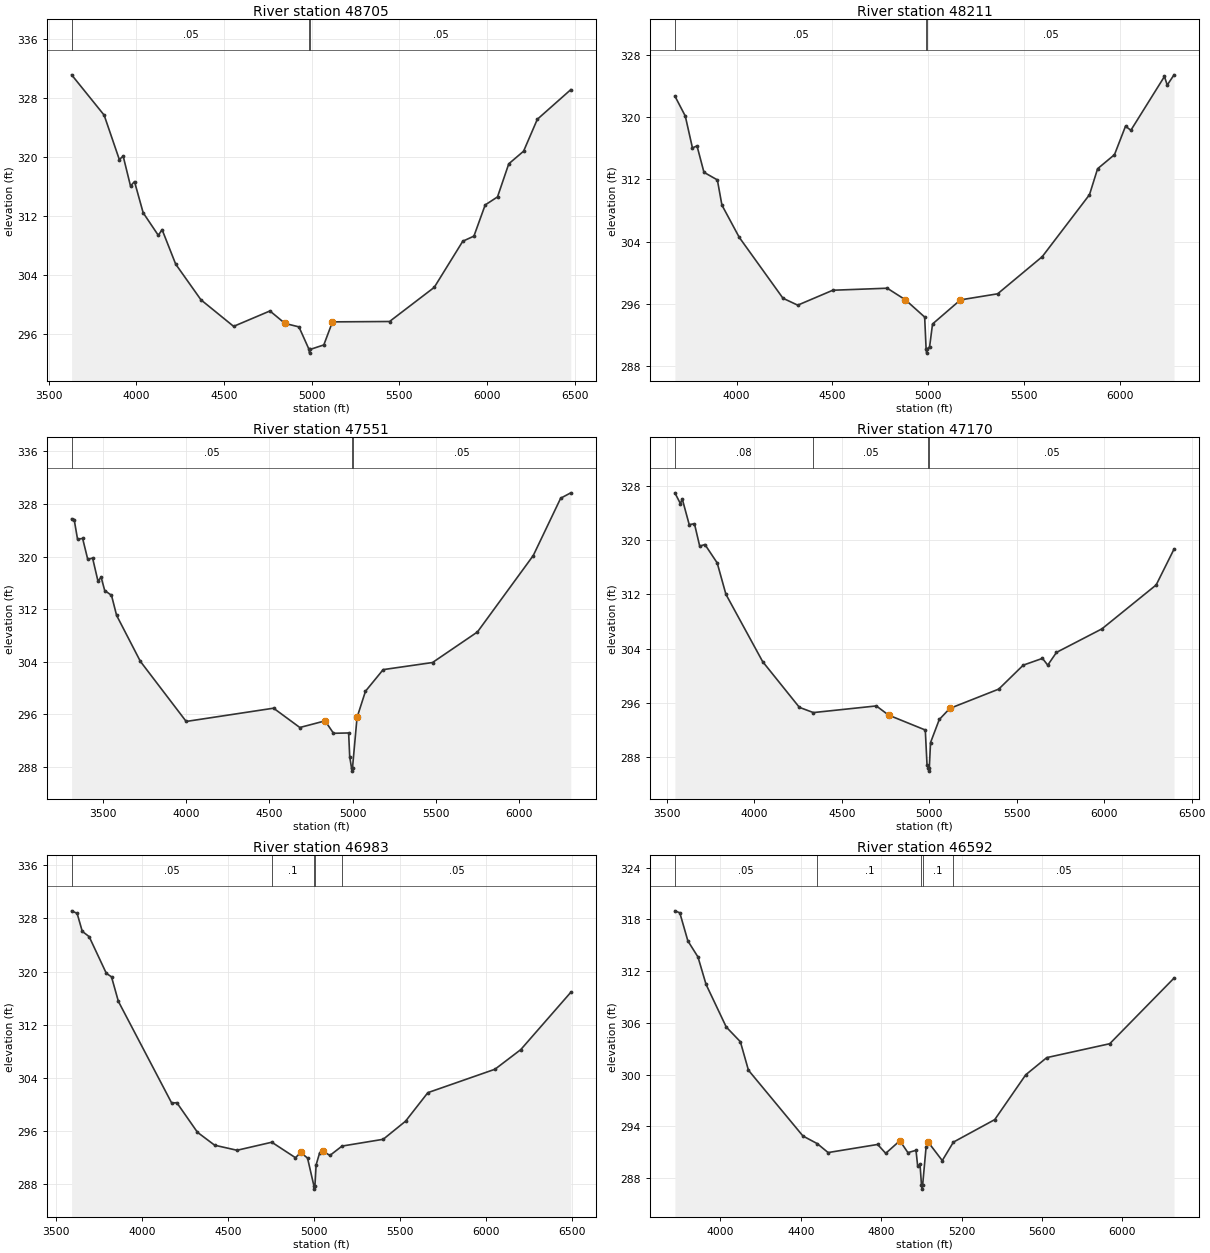
Type RM Length L Ch R = 1 ,48705   ,494,494,494
BEGIN DESCRIPTION:
SALT CREEK 68.0
END DESCRIPTION:
XS GIS Cut Line= 3
      2286387.71     13406896.86      2285287.72     13407696.85
      2284187.75     13408696.82
#Sta/Elev= 30
  3631.6  331.16  3817.1  325.69  3903.6  319.67  3925.6  320.13  3967.4  316.08
  3990.2  316.68  4039.6  312.45  4126.2  309.38  4147.4  310.17  4225.1  305.48
  4369.2  300.64  4555.5  297.04  4762.6  299.13  4848.4  297.44    4928  296.97
  4985.6  293.91  4988.4  293.41  4991.6  293.91  5069.8  294.52  5119.1  297.65
  5444.8   297.7  5699.6  302.33  5862.4  308.59  5925.9  309.28  5990.1  313.51
  6060.4   314.6  6124.6  319.09  6209.1   320.8  6287.5  325.13  6478.3  329.15
#Mann= 3 ,-1 , 0
  3631.6     .05       0  4985.6     .03       0  4991.6     .05       0
Bank Sta=4848.4,5119.1
XS Rating Curve= 0 ,0
Exp/Cntr=0.3,0.1

Type RM Length L Ch R = 1 ,48211   ,660,660,660
BEGIN DESCRIPTION:
SALT CREEK 67.0
END DESCRIPTION:
XS GIS Cut Line= 3
      2286137.75     13406946.84      2284937.72     13407446.85
      2284237.71     13408546.88
#Sta/Elev= 30
  3678.3  322.73  3732.5  320.16  3769.9  316.06  3793.7  316.32    3830  312.92
  3899.9  311.94  3923.7   308.7  4014.2  304.55  4242.2  296.72  4319.1  295.83
  4502.2  297.75    4786  298.01  4880.8  296.52  4981.3   294.3  4988.9  290.16
  4991.6  289.66  4994.9  290.16  5007.1  290.49  5022.4  293.41    5168  296.51
  5361.9  297.29  5594.7  302.07  5841.1  310.04  5883.4  313.38  5971.5  315.19
    6029  318.85    6057  318.33  6232.2  325.25  6246.6  324.14  6282.2  325.46
#Mann= 3 ,-1 , 0
  3678.3     .05       0  4988.9     .03       0  4994.9     .05       0
Bank Sta=4880.8,5168
XS Rating Curve= 0 ,0
Exp/Cntr=0.3,0.1

Type RM Length L Ch R = 1 ,47551   ,381,381,381
BEGIN DESCRIPTION:
SALT CREEK 66.0
END DESCRIPTION:
XS GIS Cut Line= 4
      2286172.59     13406876.65      2284908.74     13407126.64
      2284332.35     13407043.31      2283228.21     13407265.53
#Sta/Elev= 30
  3313.1  325.75  3328.3  325.64  3348.6  322.65  3379.2  322.75  3409.8  319.59
  3439.1  319.76    3471  316.29  3490.4  316.84  3511.7  314.83  3552.5   314.1
  3583.1  311.05  3725.8  304.05    4001   294.9  4525.6  296.92  4683.3  293.98
  4834.9  294.99  4885.4   293.1  4976.3  293.15  4982.8  289.52  4993.5  287.84
  4996.3  287.34  4999.5  287.84  5026.8  295.51  5077.4   299.5  5183.6  302.79
  5479.9  303.87  5749.6  308.52  6084.9  320.16  6249.4  328.88  6310.1   329.7
#Mann= 3 ,-1 , 0
  3313.1     .05       0  4993.5     .03       0  4999.5     .05       0
Bank Sta=4834.9,5026.8
XS Rating Curve= 0 ,0
Exp/Cntr=0.3,0.1

Type RM Length L Ch R = 1 ,47170   ,187,187,187
BEGIN DESCRIPTION:
SALT CREEK 65.0
END DESCRIPTION:
XS GIS Cut Line= 2
      2286179.58     13406793.31      2283325.42     13406765.53
#Sta/Elev= 30
    3545  326.95  3576.9  325.34  3586.9  326.07  3626.9  322.27  3656.9  322.39
  3686.9  319.09  3716.9  319.33  3786.9  316.62  3836.9  311.99  4046.9  302.07
  4256.9  295.33  4336.9  294.56  4696.9  295.54  4766.9  294.19  4976.9  291.99
  4986.9   286.8  4993.9  286.43  4996.7  285.93  4999.9  286.43  5006.9  290.14
  5056.9  293.54  5116.9  295.17  5396.9  298.02    5537  301.55    5647  302.55
    5677  301.55    5727  303.43    5987   306.9    6297  313.37  6399.3  318.66
#Mann= 4 ,-1 , 0
    3545     .08       0  4336.9     .05       0  4993.9     .04       0
  4999.9     .05       0
Bank Sta=4766.9,5116.9
XS Rating Curve= 0 ,0
Exp/Cntr=0.3,0.1

Type RM Length L Ch R = 1 ,46983   ,391,391,391
BEGIN DESCRIPTION:
SALT CREEK 64.0
END DESCRIPTION:
XS GIS Cut Line= 2
       2286179.6     13406591.92      2283276.83     13406605.81
#Sta/Elev= 30
  3590.3  329.12  3622.2  328.74  3652.2  326.04  3692.2  325.24  3792.2  319.72
  3822.2   319.2  3862.2  315.51  4172.2  300.23  4202.2  300.28  4322.2  295.83
  4422.2  293.89  4552.2  293.13  4754.4  294.34  4892.2  292.01  4922.2   292.8
  4962.2  291.96  4999.2  287.79  5001.9  287.29  5005.2  287.79  5012.2  290.95
  5032.2   292.7  5052.2     293  5092.2  292.35  5162.8  293.76  5402.2  294.78
  5532.2   297.5  5661.9  301.79  6052.2  305.31  6202.2  308.26  6493.1  316.87
#Mann= 5 ,-1 , 0
  3590.3     .05       0  4754.4      .1       0  4999.2     .07       0
  5005.2      .1       0  5162.8     .05       0
Bank Sta=4922.2,5052.2
XS Rating Curve= 0 ,0
Exp/Cntr=0.3,0.1

Type RM Length L Ch R = 1 ,46592   ,915,915,915
BEGIN DESCRIPTION:
Mapping XS c4e11bf7
END DESCRIPTION:
XS GIS Cut Line= 3
      2285872.08     13406163.96      2284222.74     13406311.53
      2283432.82     13406554.59
#Sta/Elev= 30
  3774.3     319  3798.8  318.77  3838.9  315.51  3889.1  313.65  3929.3  310.47
  4029.7  305.53    4100  303.82  4140.1  300.52  4411.2  292.89    4482  292.01
  4536.4  290.97  4782.7  291.91  4822.8  290.88  4893.1  292.34  4933.3  290.96
  4973.4  291.23  4981.7  289.41  4993.5  289.59  5000.6  287.23  5003.3  286.73
  5006.6  287.23  5023.6  291.63  5033.7  292.19    5104  290.04  5159.4  292.18
    5365  294.79  5519.2  299.99  5623.8  301.98  5936.9  303.59  6256.7   311.2
#Mann= 5 ,-1 , 0
  3774.3     .05       0    4482      .1       0  5000.6     .07       0
  5006.6      .1       0  5159.4     .05       0
Bank Sta=4893.1,5033.7
XS Rating Curve= 0 ,0
Exp/Cntr=0.3,0.1

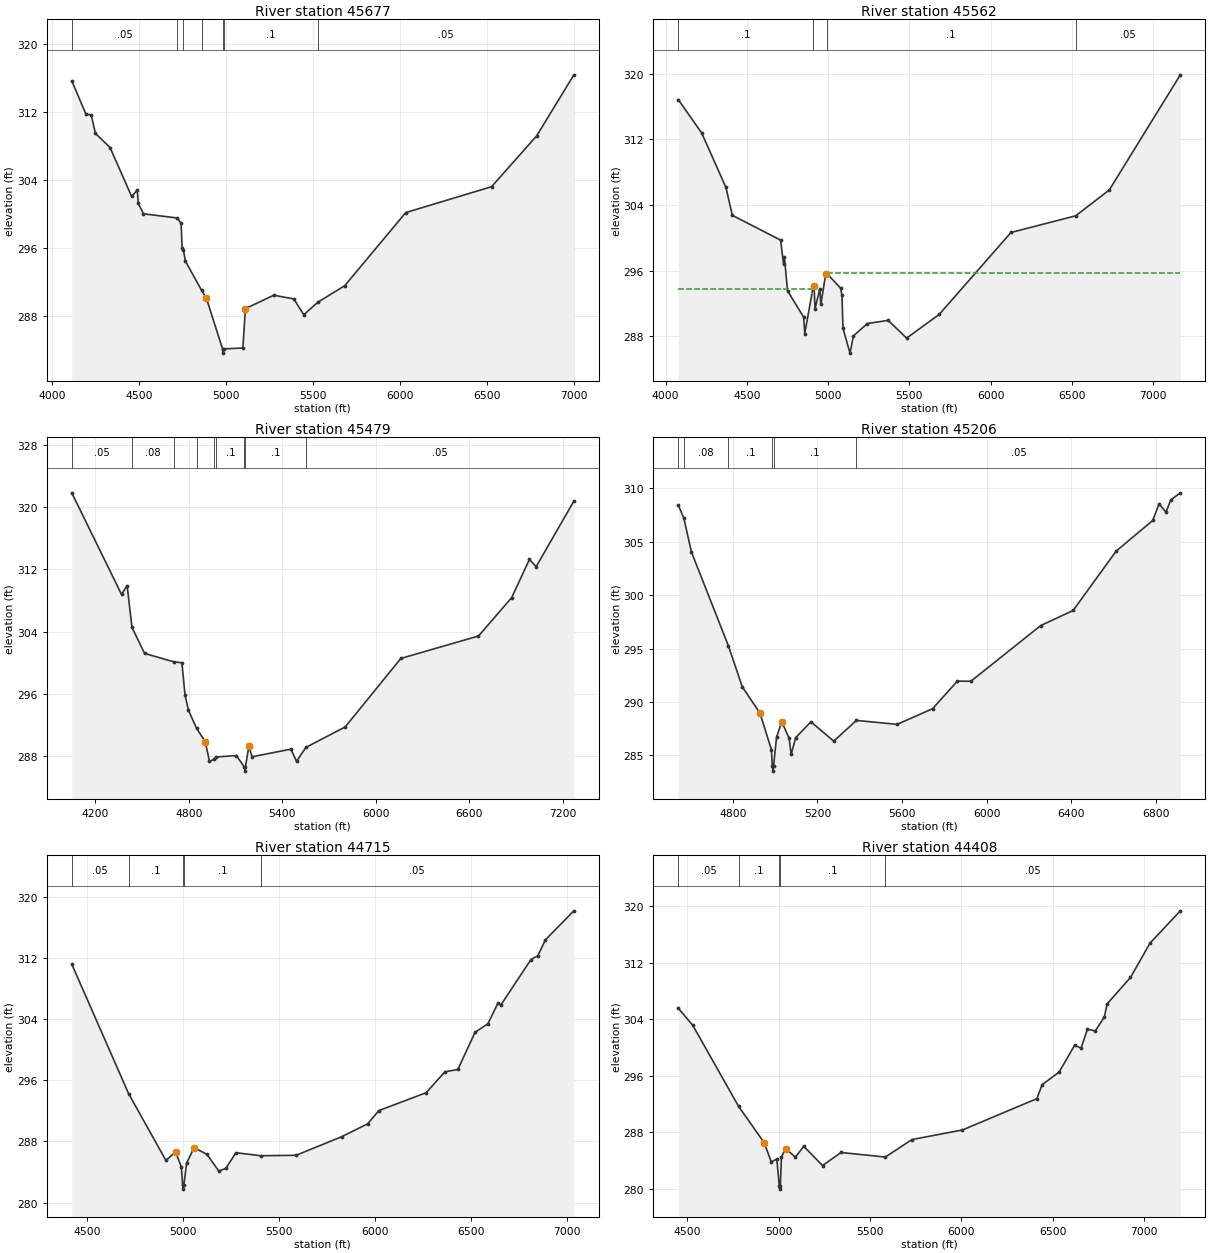
Type RM Length L Ch R = 1 ,45677   ,115,115,115
BEGIN DESCRIPTION:
Mapping XS c53d1f17
END DESCRIPTION:
XS GIS Cut Line= 5
       2285727.8     13405752.36       2284936.1     13405439.85
       2284873.6      13405432.9      2284818.05     13405453.74
      2283276.35      13406585.7
#Sta/Elev= 30
  4114.4  315.71  4196.3  311.76    4226   311.7  4250.4  309.52  4334.3  307.86
  4458.5  302.11  4490.8  302.85  4496.6   301.3  4526.4  300.06  4720.5  299.57
  4742.8  298.94  4748.8  296.05  4756.6  295.79  4767.2  294.51    4861  291.04
  4888.6  290.11    4981  284.17  4983.8  283.67    4987  284.17  5097.9  284.27
  5112.6  288.91  5275.5  290.48  5390.4  290.05  5447.9  288.19  5529.7  289.67
  5683.7  291.61    6034   300.2  6527.3  303.25  6786.4  309.22  7000.4  316.41
#Mann= 7 ,-1 , 0
  4114.4     .05       0  4720.5     .08       0  4756.6     .05       0
    4861      .1       0    4981     .07       0    4987      .1       0
  5529.7     .05       0
Bank Sta=4888.6,5112.6
XS Rating Curve= 0 ,0
Exp/Cntr=0.3,0.1

Type RM Length L Ch R = 1 ,45562   ,83,83,83
BEGIN DESCRIPTION:
SALT CREEK 63.0
END DESCRIPTION:
XS GIS Cut Line= 5
      2285741.68     13405669.02      2284956.94     13405391.24
      2284908.33     13405321.79      2284831.94     13405321.79
      2283180.22     13406612.63
#Sta/Elev= 30
  4078.1  316.85  4222.5  312.77  4371.7  306.14  4411.1  302.74  4708.2  299.72
  4726.5  296.75  4731.8  297.61  4750.6  293.55  4850.1  290.33  4856.7  288.33
  4909.6  294.14  4914.2  294.14    4920  291.33  4949.6  293.82  4955.7  291.88
  4985.4  295.54  4991.5  295.68  5077.6  293.86  5085.7  292.99  5092.1  288.97
  5135.2  285.95  5156.3  288.05  5242.1  289.56  5369.7  289.94  5483.7  287.78
  5684.4  290.67  6125.8  300.65  6523.9  302.68  6730.8  305.83    7168  319.86
#Mann= 4 ,-1 , 0
  4078.1      .1       0  4909.6     .08       0  4991.5      .1       0
  6523.9     .05       0
#XS Ineff= 2 , 0
       0 4900.85  293.76  4998.3       0  295.73
Permanent Ineff=
       T       T
Bank Sta=4914.2,4985.4
XS Rating Curve= 0 ,0
Exp/Cntr=0.3,0.1

Type RM Length L Ch R = 1 ,45479   ,273,273,273
BEGIN DESCRIPTION:
Mapping XS bbff53ac
END DESCRIPTION:
XS GIS Cut Line= 6
      2285790.24     13405571.78      2285026.38     13405294.01
      2284943.05     13405238.46       2284873.6     13405238.46
      2284755.55     13405294.01      2283112.21     13406611.46
#Sta/Elev= 30
  4050.1  321.86  4369.2  308.77  4405.1  309.91  4436.1  304.53  4516.9  301.18
    4703   300.1  4756.3  299.98  4776.2  295.83  4797.6  293.89  4849.9  291.54
 4905.91  289.82  4933.1  287.26    4964  287.57  4977.4  287.84  5105.3  288.03
  5157.4  286.52  5160.2  286.02  5163.4  286.52  5185.5  289.23  5206.3  287.87
    5455  288.85  5491.1  287.29  5551.6  289.08  5803.2  291.71  6159.9  300.53
  6657.8  303.42  6870.7  308.37  6984.3  313.28  7027.5  312.35  7269.2  320.79
#Mann= 9 ,-1 , 0
  4050.1     .05       0  4436.1     .08       0    4703     .05       0
  4849.9      .1       0    4964     .05       0  4977.4      .1       0
  5157.4     .07       0  5163.4      .1       0  5551.6     .05       0
Bank Sta=4905.91,5185.5
XS Rating Curve= 0 ,0
Exp/Cntr=0.3,0.1

Type RM Length L Ch R = 1 ,45206   ,491,491,491
BEGIN DESCRIPTION:
SALT CREEK 62.0
END DESCRIPTION:
XS GIS Cut Line= 3
       2285213.7     13404830.06      2283901.18      13405350.9
      2283026.23     13405746.72
#Sta/Elev= 30
  4542.1  308.46  4568.8   307.2  4604.4  304.05  4779.6  295.23  4844.8  291.41
  4928.5  288.95  4982.5  285.52  4986.6  284.02  4989.4  283.52  4992.6  284.02
  5006.8  286.71  5031.1  288.15  5066.2   286.6  5075.7   285.1  5097.2  286.66
  5168.8  288.14  5276.9  286.33  5384.1  288.27  5576.6   287.9    5744  289.37
  5861.1  291.95  5924.9  291.94  6254.3  297.15    6408  298.57  6611.3  304.13
    6784     307  6814.1  308.55    6847  307.78    6869  308.92  6914.5  309.59
#Mann= 6 ,-1 , 0
  4542.1     .05       0  4568.8     .08       0  4779.6      .1       0
  4986.6     .07       0  4992.6      .1       0  5384.1     .05       0
Bank Sta=4928.5,5031.1
XS Rating Curve= 0 ,0
Exp/Cntr=0.3,0.1

Type RM Length L Ch R = 1 ,44715   ,307,307,307
BEGIN DESCRIPTION:
SALT CREEK 61.0
END DESCRIPTION:
XS GIS Cut Line= 3
      2285187.75     13404546.85      2284587.72     13404546.85
      2282787.71     13405446.86
#Sta/Elev= 30
  4422.3  311.21  4718.2  294.25  4912.3  285.51  4962.3  286.63  4992.3  284.68
  4999.3  282.26  5002.1  281.76  5005.3  282.26  5019.8  285.17  5058.7  287.19
  5125.7  286.31  5187.2  284.13  5223.6  284.47  5276.7  286.53  5405.6  286.13
  5589.7  286.19  5827.3  288.63  5961.5   290.3  6020.2  292.04  6266.1  294.38
    6364  297.12  6431.1  297.42  6520.5  302.28  6587.6  303.41  6640.7  306.15
  6654.7  305.85  6811.2   311.8  6847.5  312.31  6886.6  314.39  7034.8  318.19
#Mann= 5 ,-1 , 0
  4422.3     .05       0  4718.2      .1       0  4999.3     .07       0
  5005.3      .1       0  5405.6     .05       0
Bank Sta=4962.3,5058.7
XS Rating Curve= 0 ,0
Exp/Cntr=0.3,0.1

Type RM Length L Ch R = 1 ,44408   ,712,712,712
BEGIN DESCRIPTION:
SALT CREEK 60.0
END DESCRIPTION:
XS GIS Cut Line= 4
       2285109.5     13404309.22      2284810.91     13404170.35
      2283623.41      13404600.9      2282720.61     13405323.14
#Sta/Elev= 30
  4449.4  305.56  4528.6  303.15  4779.8  291.66  4920.4   286.5  4958.4  283.81
    4989  284.19  5002.5  280.44  5005.2  279.94  5008.5  280.44  5014.3  284.48
  5037.4  285.68  5090.6  284.47  5136.8     286  5239.5  283.28  5340.5  285.13
  5582.9  284.48  5728.8  286.96  6005.4  288.32  6412.8  292.75  6441.6  294.73
  6534.5  296.52  6619.3  300.31  6654.6  299.91  6689.8  302.59    6733  302.35
  6782.6  304.34    6797  306.17  6925.1  309.91  7032.3  314.78    7198  319.35
#Mann= 5 ,-1 , 0
  4449.4     .05       0  4779.8      .1       0  5002.5     .07       0
  5008.5      .1       0  5582.9     .05       0
Bank Sta=4920.4,5037.4
XS Rating Curve= 0 ,0
Exp/Cntr=0.3,0.1

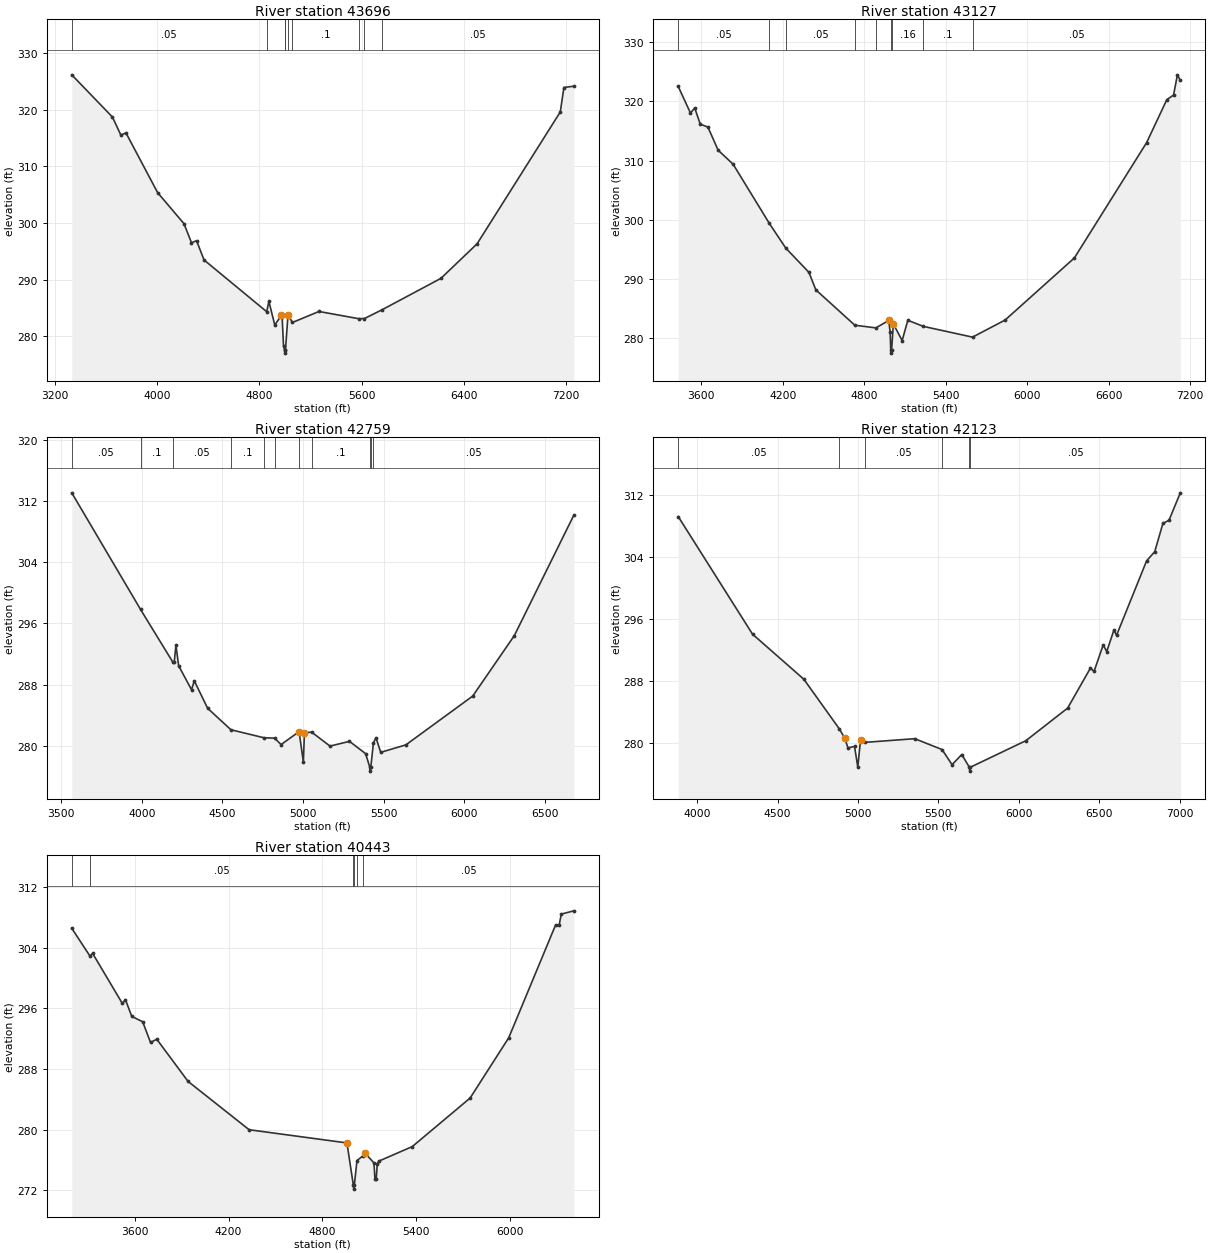
Type RM Length L Ch R = 1 ,43696   ,569,569,569
BEGIN DESCRIPTION:
SALT CREEK 59.0
END DESCRIPTION:
XS GIS Cut Line= 3
       2285737.7     13402996.87      2284187.72     13403696.85
       2282587.7     13405246.87
#Sta/Elev= 30
  3331.2  326.17  3649.4  318.71  3715.2  315.53    3755  315.92  4002.7  305.36
    4209  299.87  4267.9   296.5  4307.7  296.86  4365.9  293.46  4856.4  284.31
  4873.4  286.14  4919.6  281.95  4971.4  283.67    4977  283.44    4988  278.28
    4997  277.49  4999.7  276.99    5003  277.49  5023.1  283.75    5026   283.6
  5058.2  282.41  5265.3  284.35  5575.3  283.08  5621.2   283.1  5758.8  284.65
    6220  290.21  6502.9  296.32  7153.5  319.61  7181.8  323.93  7259.6  324.16
#Mann= 9 ,-1 , 0
  3331.2     .05       0  4856.4      .1       0    4997     .07       0
    5003      .1       0    5026     .16       0  5058.2      .1       0
  5575.3     .16       0  5621.2      .1       0  5758.8     .05       0
Bank Sta=4971.4,5023.1
XS Rating Curve= 0 ,0
Exp/Cntr=0.3,0.1

Type RM Length L Ch R = 1 ,43127   ,368,368,368
BEGIN DESCRIPTION:
SALT CREEK 58.0
END DESCRIPTION:
XS GIS Cut Line= 3
      2285437.68     13402996.86      2283887.72     13403246.85
      2282287.73     13404646.84
#Sta/Elev= 30
  3431.5  322.53  3521.6  318.04    3553  318.89  3593.5  316.17  3650.2  315.66
  3725.2  311.77  3835.6   309.4  4101.9  299.42  4223.4  295.24  4393.7  291.15
  4444.4   288.2  4731.6  282.23  4886.4  281.78  4981.2  283.03  4991.4  281.09
    4996  278.02  4998.7  277.52    5002  278.02  5015.2  282.45  5079.8  279.64
  5121.6  283.06  5236.5  282.03  5598.1  280.22  5838.1  283.11  6347.8  293.59
  6879.3  313.04  7028.3   320.3  7077.7  321.07  7106.2  324.49  7127.5  323.56
#Mann= 9 ,-1 , 0
  3431.5     .05       0  4101.9      .1       0  4223.4     .05       0
  4731.6      .1       0  4886.4     .16       0    4996     .07       0
    5002     .16       0  5236.5      .1       0  5598.1     .05       0
Bank Sta=4981.2,5015.2
XS Rating Curve= 0 ,0
Exp/Cntr=0.3,0.1

Type RM Length L Ch R = 1 ,42759   ,636,636,636
BEGIN DESCRIPTION:
Mapping XS 54c2b3d9
END DESCRIPTION:
XS GIS Cut Line= 3
      2285081.95     13402599.56      2283581.94     13403002.35
       2282332.3     13403939.57
#Sta/Elev= 30
  3565.7  313.11  3992.6  297.83  4191.7  290.97  4201.7  290.98    4212  293.15
  4228.8  290.46  4308.8  287.32  4325.9  288.48  4408.8  284.89  4553.2  282.08
  4758.3  281.03  4824.1  280.98  4864.4  280.14  4976.2  281.83  5002.7  277.85
  5009.3   281.7  5054.6  281.76    5168  279.94  5288.8  280.56  5388.8  278.95
    5415  277.16  5417.7  276.66    5421  277.16  5437.4  280.36  5453.4  281.03
  5482.5  279.12  5638.8   280.1  6053.4  286.49  6311.6  294.41  6680.9  310.19
#Mann= 11 ,-1 , 0
  3565.7     .05       0  3992.6      .1       0  4191.7     .05       0
  4553.2      .1       0  4758.3     .16       0  4824.1      .1       0
  4976.2     .16       0  5054.6      .1       0    5415     .07       0
    5421      .1       0  5437.4     .05       0
Bank Sta=4976.2,5009.3
XS Rating Curve= 0 ,0
Exp/Cntr=0.3,0.1

Type RM Length L Ch R = 1 ,42123   ,1680,1680,1680
BEGIN DESCRIPTION:
SALT CREEK 57.0
END DESCRIPTION:
XS GIS Cut Line= 3
      2285026.34      13402259.3      2283762.49     13402488.46
      2282131.62     13403335.12
#Sta/Elev= 30
  3882.5   309.2  4344.4  294.05  4663.6  288.24  4882.6  281.89  4917.7  280.67
  4938.1  279.39  4978.7  279.59    4999  276.93  5016.1   280.4  5045.5  280.11
  5353.1  280.58  5523.1  279.18  5585.1  277.23  5645.6  278.54  5692.7   276.9
  5695.5   276.4  5698.7   276.9    6044  280.32  6303.8  284.52  6445.5  289.67
  6468.1  289.25    6525  292.66  6547.1  291.81    6592   294.6  6607.8  293.89
  6794.8  303.49  6845.5  304.68  6896.2  308.32    6934  308.72  7004.5  312.26
#Mann= 6 ,-1 , 0
  3882.5     .05       0  4882.6      .1       0  5045.5     .05       0
  5523.1      .1       0  5692.7     .07       0  5698.7     .05       0
Bank Sta=4917.7,5016.1
XS Rating Curve= 0 ,0
Exp/Cntr=0.3,0.1

Type RM Length L Ch R = 1 ,40443   ,553,553,553
BEGIN DESCRIPTION:
SALT CREEK 56.0
END DESCRIPTION:
XS GIS Cut Line= 5
      2284970.78     13401967.63      2283519.44     13402002.35
      2283304.16     13402016.24      2283109.71     13402294.01
      2282033.37     13402828.71
#Sta/Elev= 30
  3198.1  306.54  3314.8  302.86  3331.2  303.23  3521.3  296.63  3541.3  297.12
  3581.3  294.93  3651.3  294.21  3701.3  291.49  3741.3  291.91  3941.4  286.35
  4331.5  279.98  4956.6  278.24  4997.6  272.65  5000.4  272.15  5003.6  272.65
  5020.7  275.92  5058.3  276.52  5072.6  276.88  5129.2  275.61  5135.3  273.54
    5144  273.55  5150.1  275.45  5158.9  275.83  5374.2  277.76  5743.8  284.16
  5990.3   292.1    6290  306.98  6312.3  306.94  6326.4  308.41  6406.5  308.84
#Mann= 6 ,-1 , 0
  3198.1     .08       0  3314.8     .05       0  4997.6     .03       0
  5003.6     .05       0  5020.7      .1       0  5058.3     .05       0
Bank Sta=4956.6,5072.6
XS Rating Curve= 0 ,0
Exp/Cntr=0.3,0.1