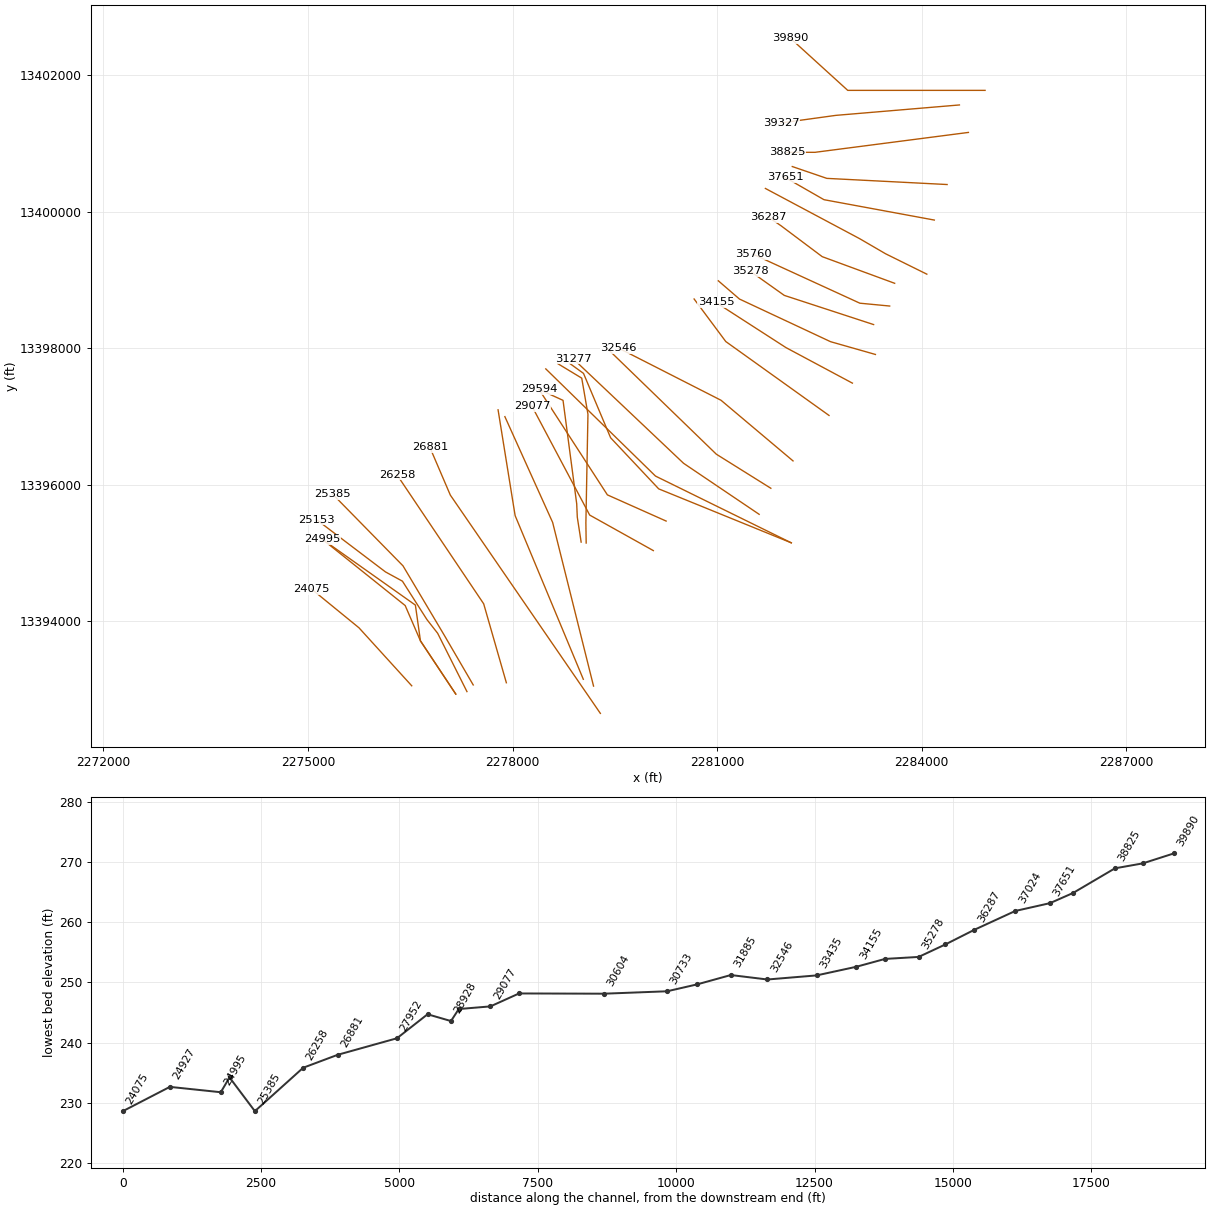
HEC-RAS study SALT CREEK.prj: SALT CREEK Base Level Engineering

--- SALT CREEK.g01 (geometry) --- (continued)

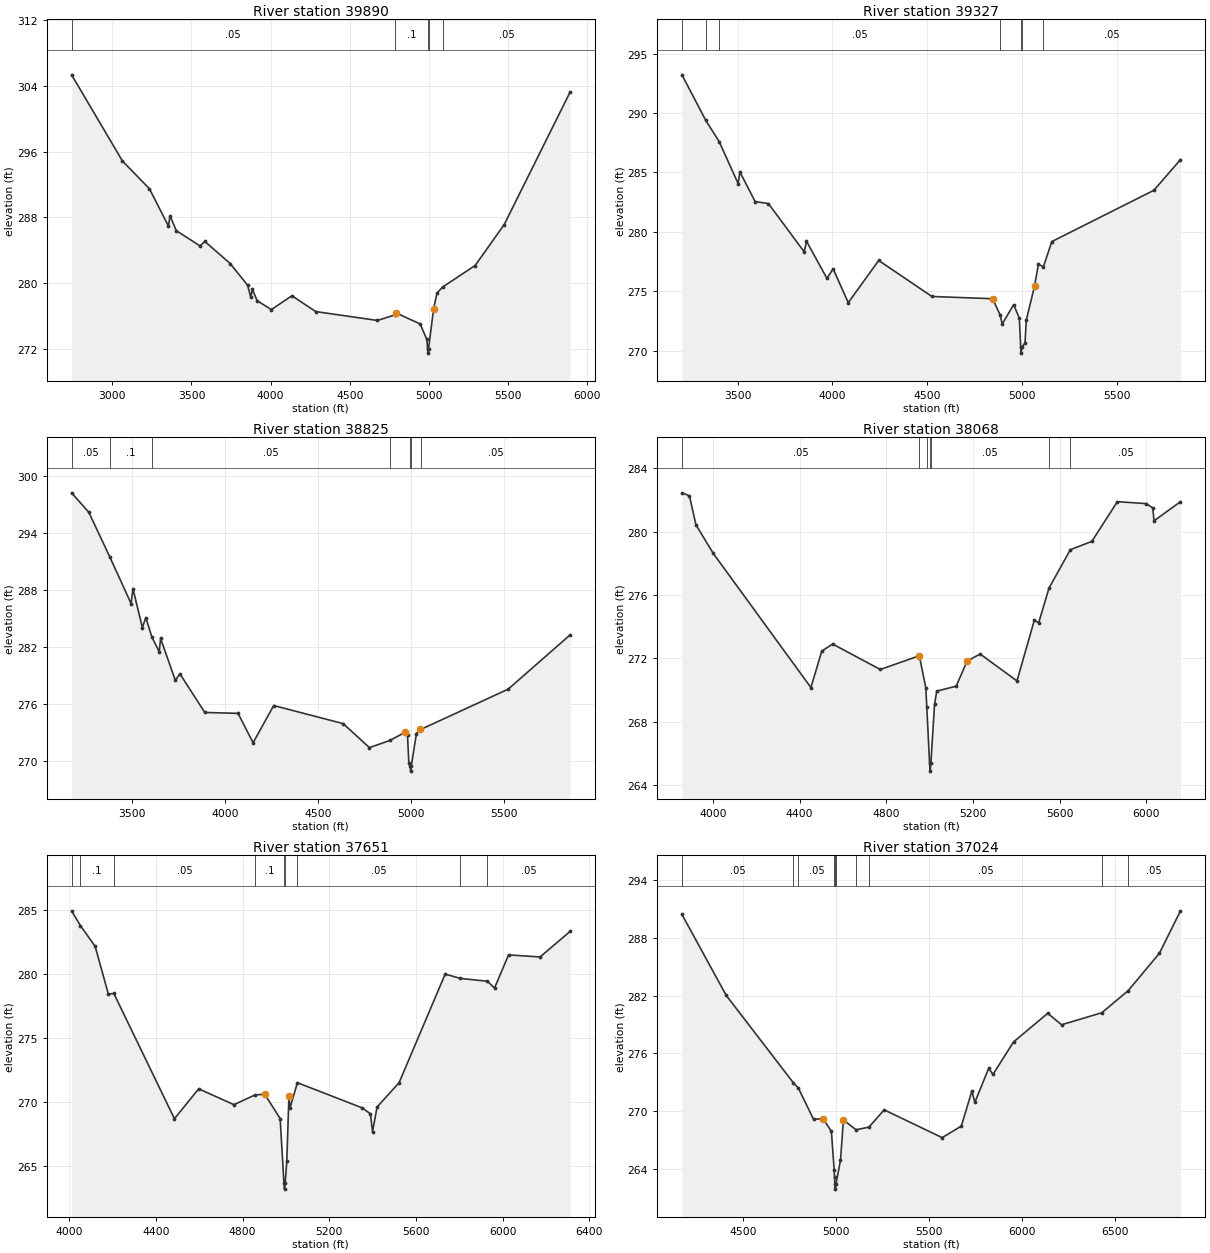
Type RM Length L Ch R = 1 ,39890   ,563,563,563
BEGIN DESCRIPTION:
SALT CREEK 55.0
END DESCRIPTION:
XS GIS Cut Line= 3
      2284929.17     13401780.13      2282915.27     13401780.13
      2282076.18     13402542.94
#Sta/Elev= 30
  2743.1  305.34  3064.5  294.84  3234.5  291.47  3354.5  286.93  3364.5  288.16
  3404.5  286.36  3554.5   284.5  3584.5  285.05  3744.5  282.36  3854.5  279.72
  3874.5  278.26  3884.5  279.22  3914.5  277.84  4004.5  276.75  4134.5  278.44
  4284.5  276.51  4674.5  275.43  4785.2  276.11  4788.4  276.37  4943.8  275.01
  4986.4  273.11  4990.8  271.95  4993.6  271.45  4996.8  271.95  5028.9  276.83
  5050.6  278.77  5085.9   279.5  5291.1  282.12  5474.9  287.11    5891  303.25
#Mann= 5 ,-1 , 0
  2743.1     .05       0  4785.2      .1       0  4990.8     .07       0
  4996.8      .1       0  5085.9     .05       0
Bank Sta=4788.4,5028.9
XS Rating Curve= 0 ,0
Exp/Cntr=0.3,0.1

Type RM Length L Ch R = 1 ,39327   ,502,502,502
BEGIN DESCRIPTION:
SALT CREEK 54.0
END DESCRIPTION:
XS GIS Cut Line= 3
      2284552.76     13401566.38      2282740.28      13401413.6
      2281934.72     13401302.49
#Sta/Elev= 30
  3205.5  293.22  3331.1  289.39    3402   287.6    3502  284.07  3511.6  285.04
  3591.9  282.55  3662.2  282.38  3851.2  278.31  3862.9  279.22    3971  276.08
  4003.4  276.89  4083.6  274.04  4244.2  277.59  4525.2  274.56  4846.3  274.37
  4885.2     273  4896.5  272.24  4956.7  273.87  4986.8  272.74  4993.9  270.29
  4996.6  269.79  4999.9  270.29  5016.9  270.63  5023.2  272.55  5067.4  275.46
  5087.6  277.28  5113.8  277.05  5158.2  279.18  5697.1   283.5  5837.6  286.08
#Mann= 7 ,-1 , 0
  3205.5     .05       0  3331.1      .1       0    3402     .05       0
  4885.2      .1       0  4993.9     .07       0  4999.9      .1       0
  5113.8     .05       0
Bank Sta=4846.3,5067.4
XS Rating Curve= 0 ,0
Exp/Cntr=0.3,0.1

Type RM Length L Ch R = 1 ,38825   ,757,757,757
BEGIN DESCRIPTION:
SALT CREEK 53.0
END DESCRIPTION:
XS GIS Cut Line= 3
      2284684.74      13401163.6      2282434.72     13400871.93
      2282024.97     13400871.93
#Sta/Elev= 30
  3176.7   298.2  3268.8  296.17  3381.4  291.49  3496.4  286.57  3506.5  288.13
  3556.9  284.05  3575.6   285.1  3608.2  283.04  3647.6  281.51  3654.8  282.91
  3734.1   278.5  3758.6  279.19  3892.5  275.13  4071.1  275.04  4151.8  271.95
  4262.7  275.86  4635.8  273.96    4777  271.44  4887.9   272.2  4968.6  273.05
  4981.6  272.73  4988.8   269.8  4995.8  269.47  4998.6  268.97  5001.8  269.47
  5029.1  272.88  5049.3  273.41  5051.7  273.34  5522.5  277.58  5855.3  283.28
#Mann= 7 ,-1 , 0
  3176.7     .05       0  3381.4      .1       0  3608.2     .05       0
  4887.9      .1       0  4995.8     .07       0  5001.8      .1       0
  5051.7     .05       0
Bank Sta=4968.6,5049.3
XS Rating Curve= 0 ,0
Exp/Cntr=0.3,0.1

Type RM Length L Ch R = 1 ,38068   ,417,417,417
BEGIN DESCRIPTION:
SALT CREEK 52.0
END DESCRIPTION:
XS GIS Cut Line= 3
      2284372.27     13400399.71      2282608.33     13400489.99
      2282102.05     13400663.37
#Sta/Elev= 30
  3856.6  282.45  3891.2  282.26  3921.2  280.43  4001.3  278.62  4451.9  270.15
    4502  272.45  4552.1   272.9  4772.3  271.29  4952.4  272.16  4982.6  270.11
  4986.9  268.91  4999.7  265.37  5002.4  264.87  5005.7  265.37  5022.7  269.09
  5032.7  269.92  5122.8  270.24  5172.9  271.82    5233  272.27  5403.2  270.57
  5483.3   274.4  5503.3  274.24  5551.3  276.44  5649.7  278.86  5748.6  279.38
  5866.6  281.89  5998.9  281.77  6030.1   281.5  6035.7  280.68    6158  281.89
#Mann= 7 ,-1 , 0
  3856.6     .05       0  4952.4      .1       0  4986.9     .05       0
  4999.7     .03       0  5005.7     .05       0  5551.3      .1       0
  5649.7     .05       0
Bank Sta=4952.4,5172.9
XS Rating Curve= 0 ,0
Exp/Cntr=0.3,0.1

Type RM Length L Ch R = 1 ,37651   ,627,627,627
BEGIN DESCRIPTION:
SALT CREEK 51.0
END DESCRIPTION:
XS GIS Cut Line= 3
      2284184.67     13399878.89      2282566.67     13400177.49
      2281997.21     13400503.89
#Sta/Elev= 30
  4010.2  284.96  4051.1   283.8    4119  282.18    4180  278.44  4205.3  278.49
    4485  268.69  4596.9  271.03  4759.6  269.79  4858.4  270.56    4902   270.6
  4973.1   268.7  4990.5  263.68  4993.2  263.18  4996.5  263.68  5003.7  265.35
  5013.6  270.43  5018.6  269.53  5052.8  271.51  5351.7  269.54  5390.1  269.07
  5399.6  267.68  5420.6  269.61  5522.3  271.51    5735  280.01  5805.5  279.67
  5929.7  279.45  5962.9  278.92  6027.6  281.51    6173  281.35  6311.9  283.35
#Mann= 9 ,-1 , 0
  4010.2     .05       0  4051.1      .1       0  4205.3     .05       0
  4858.4      .1       0  4990.5     .07       0  4996.5      .1       0
  5052.8     .05       0  5805.5     .08       0  5929.7     .05       0
Bank Sta=4902,5013.6
XS Rating Curve= 0 ,0
Exp/Cntr=0.3,0.1

Type RM Length L Ch R = 1 ,37024   ,737,737,737
BEGIN DESCRIPTION:
SALT CREEK 50.0
END DESCRIPTION:
XS GIS Cut Line= 4
      2284075.01     13399085.67      2283470.83     13399384.29
      2283088.88     13399606.51      2281707.65     13400342.24
#Sta/Elev= 30
  4173.1  290.42  4411.3  282.01  4772.6  272.92  4799.7  272.36  4880.8  269.13
  4931.6  269.21  4976.8  267.88  4991.7  263.86  4993.4  263.16  4995.3  262.38
    4998  261.88  5001.3  262.38  5025.6  264.88  5041.3  269.07  5109.1  268.05
  5178.3  268.32  5260.6  270.12  5572.3  267.23  5675.5  268.43  5732.1  272.07
  5748.1   270.9  5822.8  274.45  5845.4   273.8  5956.4  277.18    6140  280.15
  6214.3  278.96  6430.9  280.21  6572.3   282.5  6740.5  286.39  6853.9   290.8
#Mann= 11 ,-1 , 0
  4173.1     .05       0  4772.6      .1       0  4799.7     .05       0
  4991.7      .1       0  4993.4     .05       0  4995.3     .04       0
  5001.3     .05       0  5109.1      .1       0  5178.3     .05       0
  6430.9     .08       0  6572.3     .05       0
Bank Sta=4931.6,5041.3
XS Rating Curve= 0 ,0
Exp/Cntr=0.3,0.1

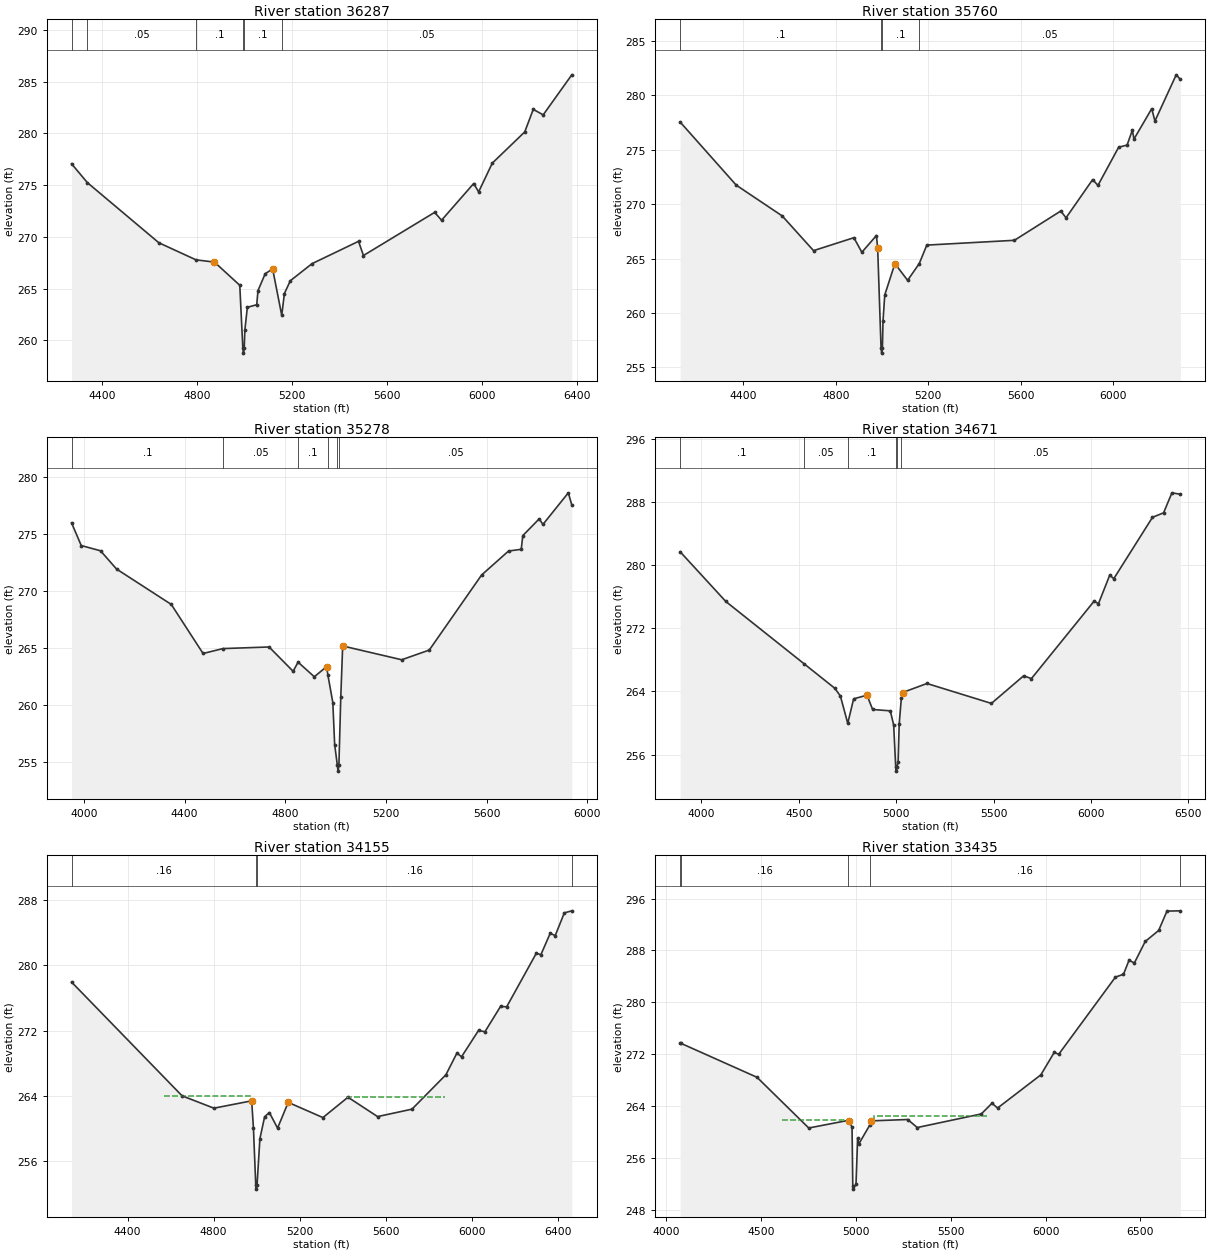
Type RM Length L Ch R = 1 ,36287   ,527,527,527
BEGIN DESCRIPTION:
SALT CREEK 49.0
END DESCRIPTION:
XS GIS Cut Line= 4
      2283603.13     13398951.79      2282540.63     13399342.42
      2281936.46     13399795.54      2281754.15     13399920.56
#Sta/Elev= 30
    4271  277.07  4337.5  275.25    4639  269.43  4795.6  267.78  4873.4  267.56
    4980  265.32  4992.8  259.26  4995.6  258.76  4998.8  259.26  5001.3  260.96
  5011.9  263.19  5051.4  263.44  5056.8  264.81  5087.2  266.44  5118.5   266.9
  5156.9  262.41    5168  264.52    5193  265.76  5284.5  267.41  5480.4  269.57
  5501.3   268.2  5801.3  272.37  5830.4  271.61  5965.8  275.16  5986.7  274.35
  6044.2  277.13    6181  280.15  6216.9  282.33  6258.8   281.8  6379.3  285.67
#Mann= 6 ,-1 , 0
    4271      .1       0  4337.5     .05       0  4795.6      .1       0
  4992.8     .07       0  4998.8      .1       0  5156.9     .05       0
Bank Sta=4873.4,5118.5
XS Rating Curve= 0 ,0
Exp/Cntr=0.3,0.1

Type RM Length L Ch R = 1 ,35760   ,482,482,482
BEGIN DESCRIPTION:
SALT CREEK 48.0
END DESCRIPTION:
XS GIS Cut Line= 3
      2283530.19     13398618.46      2283092.71     13398660.13
      2281524.98     13399378.89
#Sta/Elev= 30
  4126.4  277.55    4369  271.75  4567.9  268.92  4703.4  265.73  4877.9  266.92
  4912.4  265.58  4975.4  267.12  4980.9  265.94  4995.4  256.81  4998.1  256.31
  5001.4  256.81  5003.9  259.22  5011.4  261.65  5055.4  264.54  5110.4     263
  5160.7  264.54  5193.4  266.24  5572.4  266.68  5772.8  269.37  5795.8  268.75
  5910.8  272.26  5933.8  271.73  6023.5  275.24  6059.8  275.43  6082.8  276.81
  6089.5  275.98  6166.5  278.78  6180.3  277.64  6272.3  281.89  6290.5  281.47
#Mann= 4 ,-1 , 0
  4126.4      .1       0  4995.4     .07       0  5001.4      .1       0
  5160.7     .05       0
Bank Sta=4980.9,5055.4
XS Rating Curve= 0 ,0
Exp/Cntr=0.3,0.1

Type RM Length L Ch R = 1 ,35278   ,607,607,607
BEGIN DESCRIPTION:
SALT CREEK 47.0
END DESCRIPTION:
XS GIS Cut Line= 3
       2283294.3     13398346.86      2281984.85     13398774.44
      2281487.79     13399127.19
#Sta/Elev= 30
  3951.3     276  3989.8  274.01  4066.4  273.55  4130.1  271.95  4347.4  268.85
  4473.7  264.55  4552.7  264.98    4736  265.12  4831.4  262.99  4851.1  263.79
  4915.5  262.51  4964.5   263.4  4969.6  262.65  4989.1  260.25  4996.4  256.56
  5007.2  254.74  5009.9  254.24  5013.2  254.74  5020.7  260.72  5028.2  265.21
  5262.7     264  5372.2  264.85  5580.1  271.43  5687.1  273.53  5737.5  273.68
  5743.7  274.88  5808.9  276.35  5823.7  275.86  5924.5  278.63  5938.3  277.57
#Mann= 6 ,-1 , 0
  3951.3      .1       0  4552.7     .05       0  4851.1      .1       0
  4969.6     .05       0  5007.2     .03       0  5013.2     .05       0
Bank Sta=4964.5,5028.2
XS Rating Curve= 0 ,0
Exp/Cntr=0.3,0.1

Type RM Length L Ch R = 1 ,34671   ,516,516,516
BEGIN DESCRIPTION:
SALT CREEK 46.0
END DESCRIPTION:
XS GIS Cut Line= 4
      2283321.04     13397908.59      2282663.63     13398095.66
      2281327.44     13398720.99      2281017.42     13398988.25
#Sta/Elev= 30
  3891.4  281.67  4125.7  275.38  4526.3  267.52  4685.1   264.4  4713.9  263.42
  4751.7  259.96    4782  263.06  4850.5  263.52  4879.5  261.71  4970.2  261.54
  4987.5  259.74    4998  254.41  5000.7  253.91    5004  254.41  5010.3  255.06
  5015.9   259.9  5026.9  263.15  5033.2  263.86  5158.4     265  5489.2  262.48
  5654.5  265.97  5694.7  265.62  6016.8  275.43  6038.8   275.1  6096.7  278.71
  6117.6  278.27  6316.2  286.03  6373.2   286.6    6416  289.13  6459.5  288.95
#Mann= 6 ,-1 , 0
  3891.4      .1       0  4526.3     .05       0  4751.7      .1       0
    4998     .07       0    5004      .1       0  5026.9     .05       0
Bank Sta=4850.5,5033.2
XS Rating Curve= 0 ,0
Exp/Cntr=0.3,0.1

Type RM Length L Ch R = 1 ,34155   ,720,720,720
BEGIN DESCRIPTION:
SALT CREEK 45.0
END DESCRIPTION:
XS GIS Cut Line= 3
      2282983.36     13397488.24      2282009.38     13398009.09
      2280983.32     13398670.55
#Sta/Elev= 30
  4139.4  277.96  4653.2  264.03  4801.2  262.52  4976.7  263.42    4985  260.04
  4995.6  253.11  4998.4  252.61  5001.6  253.11  5014.9  258.78  5036.9  261.47
  5058.8  261.99    5097  260.08  5146.6  263.23  5307.9  261.37  5424.3  263.86
    5562  261.49  5721.8   262.4  5879.5  266.61  5930.9  269.27  5952.1  268.81
  6031.1  272.03    6061  271.88  6133.6  274.98    6162  274.93  6299.9  281.49
    6321  281.31  6364.3  283.92  6387.7  283.65    6430  286.43  6464.7  286.68
#Mann= 4 ,-1 , 0
  4139.4     .16       0  4995.6     .07       0  5001.6     .16       0
  6464.7     .05       0
#XS Ineff= 2 ,-1
 4571.02 4971.59  264.07 5417.61 5873.58  263.92
Permanent Ineff=
       T       T
Bank Sta=4976.7,5146.6
XS Rating Curve= 0 ,0
Exp/Cntr=0.3,0.1

Type RM Length L Ch R = 1 ,33435   ,889,889,889
BEGIN DESCRIPTION:
SALT CREEK 44.0
END DESCRIPTION:
XS GIS Cut Line= 3
      2282640.77     13397014.54      2281126.91     13398097.85
      2280662.53     13398721.64
#Sta/Elev= 30
  4072.4  273.65  4077.3  273.65    4478  268.42  4750.7   260.6  4958.4  261.77
  4964.5  261.69  4979.2   260.7  4983.1  251.67  4985.8  251.17  5000.1  251.97
  5008.7  258.98  5014.9  258.14  5072.2  261.02    5080   261.7  5272.9  261.91
  5323.2  260.67  5661.1  262.77  5717.6  264.42  5747.1  263.68  5975.4   268.8
  6046.3  272.28  6069.3  271.96    6369  283.88  6411.3  284.31  6440.5  286.47
  6468.8  286.06    6526  289.37  6596.9  291.07  6640.7  294.06  6711.6   294.1
#Mann= 5 ,-1 , 0
  4072.4     .05       0  4077.3     .16       0  4958.4     .12       0
  5072.2     .16       0  6711.6     .05       0
#XS Ineff= 2 ,-1
 4608.52 4946.02  261.83 5094.32 5690.91  262.39
Permanent Ineff=
       T       T
Bank Sta=4964.5,5080
XS Rating Curve= 0 ,0
Exp/Cntr=0.3,0.1

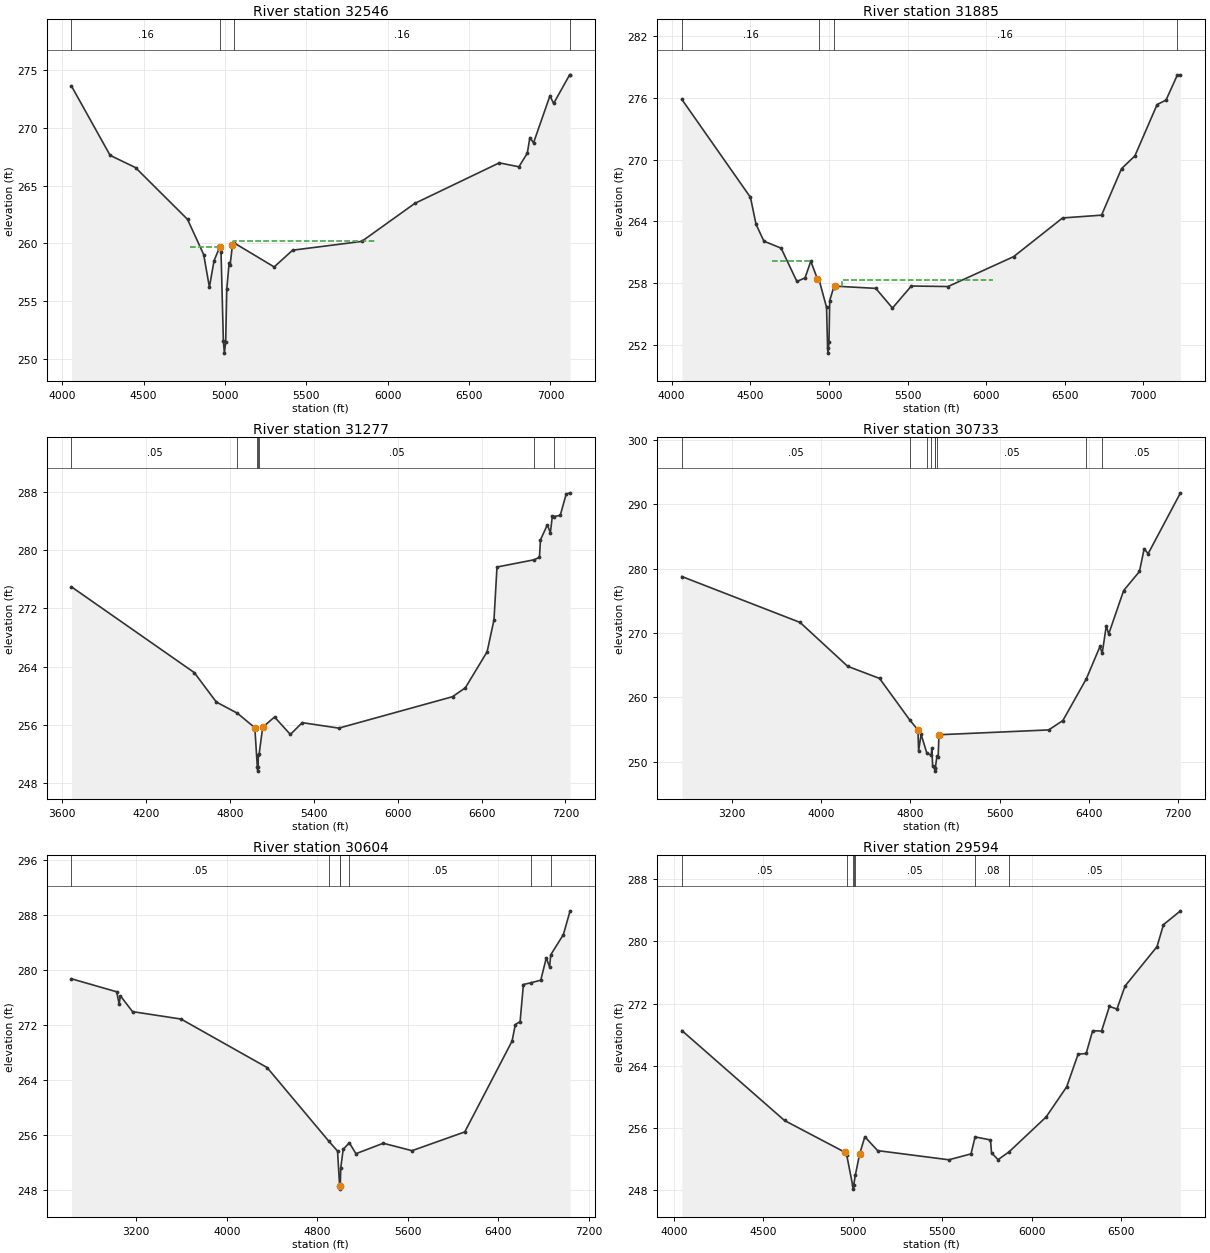
Type RM Length L Ch R = 1 ,32546   ,661,661,661
BEGIN DESCRIPTION:
SALT CREEK 43.0
END DESCRIPTION:
XS GIS Cut Line= 3
      2282113.02     13396347.85      2281057.46     13397236.74
      2279557.44     13398000.64
#Sta/Elev= 30
  4057.4  273.61  4294.8  267.61  4450.9  266.55  4770.3  262.07  4869.6  259.02
  4904.8   256.2  4933.3  258.49  4968.5  259.69  4976.2  259.25  4990.5  251.57
  4996.8  250.49  5004.8  251.49  5011.4     256  5025.7  258.28  5032.2  258.15
  5046.5  259.85  5054.3  260.05  5302.7  257.95  5415.8   259.4  5840.4  260.16
  6166.5  263.45  6685.5  266.96  6806.2  266.62  6857.8   267.8  6873.5  269.15
  6895.9  268.69  6996.9  272.77  7019.4   272.1  7117.7  274.58  7120.7  274.58
#Mann= 4 ,-1 , 0
  4057.4     .16       0  4968.5     .12       0  5054.3     .16       0
  7117.7     .05       0
#XS Ineff= 2 ,-1
  4787.5 4960.51  259.67 5051.99 5923.01  260.17
Permanent Ineff=
       T       T
Bank Sta=4968.5,5046.5
XS Rating Curve= 0 ,0
Exp/Cntr=0.3,0.1

Type RM Length L Ch R = 1 ,31885   ,608,608,608
BEGIN DESCRIPTION:
SALT CREEK 42.0
END DESCRIPTION:
XS GIS Cut Line= 3
      2281787.69     13395946.88      2280987.72     13396446.85
      2279387.74     13397996.84
#Sta/Elev= 30
  4064.8  275.84  4501.1  266.34  4536.5  263.73  4586.6  262.09  4696.2  261.41
  4796.5  258.18  4848.4  258.53  4884.9  260.14  4927.4  258.41  4936.8  258.38
  4985.2  255.66  4991.6  251.73  4994.3  251.23  5000.5  252.28  5005.2  256.33
  5029.4  257.56  5036.3  257.73  5298.2  257.51  5404.2   255.6  5524.3  257.74
  5757.9  257.69  6175.1  260.59  6486.1  264.34  6733.8  264.61  6860.9  269.12
  6945.8  270.36  7087.3  275.34  7143.9  275.77  7214.6  278.16  7235.8  278.22
#Mann= 4 ,-1 , 0
  4064.8     .16       0  4936.8     .12       0  5029.4     .16       0
  7214.6     .05       0
#XS Ineff= 2 ,-1
 4640.34 4878.98  260.21  5085.8 6044.32  258.37
Permanent Ineff=
       T       T
Bank Sta=4927.4,5036.3
XS Rating Curve= 0 ,0
Exp/Cntr=0.3,0.1

Type RM Length L Ch R = 1 ,31277   ,544,544,544
BEGIN DESCRIPTION:
SALT CREEK 41.0
END DESCRIPTION:
XS GIS Cut Line= 3
      2281616.16     13395565.02      2280507.42     13396313.37
      2278887.74     13397846.83
#Sta/Elev= 30
  3665.8  274.96  4544.6   263.2  4702.2  259.16  4853.5  257.62  4977.9  255.63
  4995.9  250.18  4998.7  249.68  5001.9  250.18  5002.1  251.92  5009.1  252.09
  5033.9  255.69  5118.9  257.11  5232.1  254.71  5317.1  256.33  5578.8  255.58
  6392.3  259.89  6484.1  261.11  6639.9  266.05  6689.2  270.43  6710.6  277.68
  6977.6  278.68  7014.5  279.02  7021.8  281.41  7071.1  283.47  7092.5  282.38
  7106.7  284.65  7116.8   284.6  7163.3  284.77  7205.8  287.69  7233.9  287.86
#Mann= 7 ,-1 , 0
  3665.8     .05       0  4853.5      .1       0  4995.9     .07       0
  5001.9      .1       0  5009.1     .05       0  6977.6     .08       0
  7116.8     .05       0
Bank Sta=4977.9,5033.9
XS Rating Curve= 0 ,0
Exp/Cntr=0.3,0.1

Type RM Length L Ch R = 1 ,30733   ,1139,1139,1139
BEGIN DESCRIPTION:
SALT CREEK 40.0
END DESCRIPTION:
XS GIS Cut Line= 3
      2282087.69     13395146.87      2280096.17     13396125.65
      2278487.69     13397696.89
#Sta/Elev= 30
  2753.2  278.76  3812.3  271.63  4239.4  264.81  4524.8  262.93  4794.5  256.49
  4868.8  254.92  4874.4  251.68  4896.9  254.25  4948.2  251.33  4986.8  250.99
  4993.2  252.12  5000.2  249.35  5018.5  249.03  5021.3  248.53  5024.5  249.03
  5038.6  250.85  5049.8  250.78  5056.8  254.18  6039.8  254.93  6167.1  256.39
  6378.1   262.9  6499.4  267.89  6519.5  266.81    6556  271.12  6577.3  269.81
  6711.6  276.58  6853.1  279.54  6895.5  283.08  6930.8   282.3  7220.8  291.76
#Mann= 9 ,-1 , 0
  2753.2     .05       0  4794.5      .1       0  4948.2     .05       0
  4986.8      .1       0  5018.5     .07       0  5024.5      .1       0
  5038.6     .05       0  6378.1     .08       0  6519.5     .05       0
Bank Sta=4868.8,5056.8
XS Rating Curve= 0 ,0
Exp/Cntr=0.3,0.1

Type RM Length L Ch R = 1 ,30604   ,1535,1535,1535
BEGIN DESCRIPTION:
SALT CREEK 40.0
END DESCRIPTION:
XS GIS Cut Line= 5
      2282087.71     13395146.86       2280143.1     13395938.19
      2279438.04     13396687.24      2279040.66      13397630.9
      2278836.69     13397778.45
#Sta/Elev= 30
  2629.1  278.76  3028.5  276.87  3050.1  275.07  3060.9  276.29  3168.2  273.98
  3596.4   272.9  4356.5  265.84    4900  255.15    4979  253.67    4997  248.63
  4999.8  248.13    5003  248.63  5007.3  251.24  5028.7  253.92  5082.9  254.88
  5141.6  253.29  5382.4  254.81  5636.8  253.73  6102.3  256.46    6520  269.68
  6549.1   272.1  6591.2  272.53  6620.3  277.93  6685.8  278.18  6773.6  278.56
  6822.4  281.79  6851.8  280.49  6861.7  282.25  6973.3   285.2  7032.9  288.66
#Mann= 7 ,-1 , 0
  2629.1     .05       0    4900      .1       0    4997     .07       0
    5003      .1       0  5082.9     .05       0  6685.8     .08       0
  6861.7     .05       0
Bank Sta=4997,5003
XS Rating Curve= 0 ,0
Exp/Cntr=0.3,0.1

Type RM Length L Ch R = 1 ,29594   ,517,517,517
BEGIN DESCRIPTION:
SALT CREEK 39.0
END DESCRIPTION:
XS GIS Cut Line= 3
      2280252.08     13395466.18      2279390.89     13395850.03
      2278387.72     13397396.86
#Sta/Elev= 30
  4045.5  268.55  4619.2  256.99    4959  252.88  4967.2  252.52  4999.9  248.67
  5002.7  248.17  5005.9  248.67  5015.2  249.99  5039.2  252.69    5068   254.9
  5139.5  253.12  5537.6  251.94  5661.5   252.7  5684.3  254.88  5770.3  254.49
  5776.2  252.83  5812.5  251.96  5873.5  252.95  6081.1  257.44  6196.1  261.32
  6259.9  265.51  6304.9   265.6  6341.2  268.53    6391  268.48  6434.8  271.65
    6477  271.31  6522.1  274.26  6700.9  279.33  6736.8  282.15    6832  283.93
#Mann= 7 ,-1 , 0
  4045.5     .05       0  4967.2      .1       0  4999.9     .07       0
  5005.9      .1       0  5015.2     .05       0  5684.3     .08       0
  5873.5     .05       0
Bank Sta=4959,5039.2
XS Rating Curve= 0 ,0
Exp/Cntr=0.3,0.1

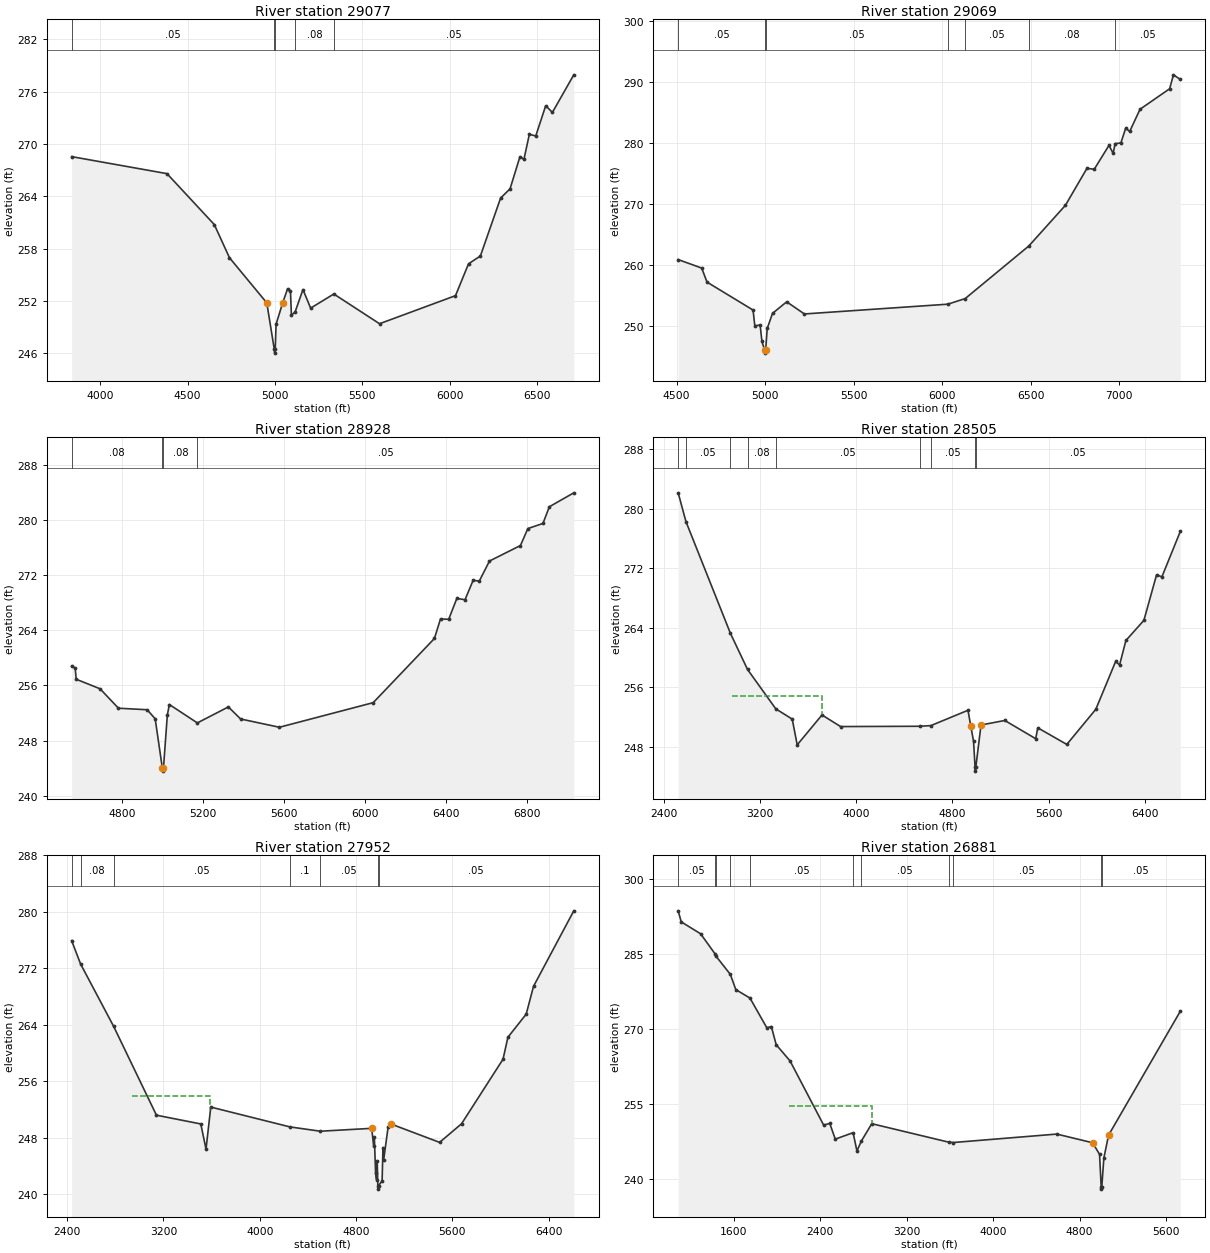
Type RM Length L Ch R = 1 ,29077   ,572,572,572
BEGIN DESCRIPTION:
SALT CREEK 38.0
END DESCRIPTION:
XS GIS Cut Line= 3
      2280064.43     13395033.17      2279131.25     13395554.02
      2278284.89     13397149.08
#Sta/Elev= 30
  3836.1  268.55  4381.9   266.6  4652.7  260.76  4739.5  256.96  4953.3  251.78
  4995.6  246.52  4998.3  246.02  5001.6  246.52  5006.3  249.33  5043.9  251.77
  5072.3  253.41  5088.6  253.16  5094.2  250.38  5114.9  250.72  5160.2  253.31
  5204.2  251.18  5336.9   252.8  5598.6  249.39  6033.4  252.61    6108  256.26
  6175.9  257.16  6291.6   263.8  6345.7  264.86  6402.3  268.54    6425  268.23
  6456.2  271.11  6492.9  270.92  6549.8  274.39  6588.1  273.62  6710.5  277.93
#Mann= 5 ,-1 , 0
  3836.1     .05       0  4995.6     .03       0  5001.6     .05       0
  5114.9     .08       0  5336.9     .05       0
Bank Sta=4953.3,5043.9
XS Rating Curve= 0 ,0
Exp/Cntr=0.3,0.1

Type RM Length L Ch R = 1 ,29069   ,141,141,141
BEGIN DESCRIPTION:
SALT CREEK 39.0
END DESCRIPTION:
XS GIS Cut Line= 5
      2279079.73     13395143.92      2279075.39     13395439.06
      2279105.77     13397031.94      2279014.62     13397561.45
      2278663.08     13397774.11
#Sta/Elev= 30
  4508.7  260.91  4641.6  259.52  4671.6  257.22  4931.7  252.64  4941.7  250.06
  4971.7  250.19  4981.7  247.52    4997  246.08  4999.8  245.58    5003  246.08
  5011.7  249.63  5041.7   252.1  5121.7  253.99  5221.7     252  6031.6   253.6
    6130  254.52  6489.5  263.14  6696.3  269.81  6818.1  275.88  6858.6   275.7
  6942.4  279.63  6965.8  278.32  6976.9  279.91  7009.5  280.03  7036.7  282.45
  7059.3  281.91  7117.7  285.55    7285  288.91  7306.4  291.19  7345.2  290.44
#Mann= 7 ,-1 , 0
  4508.7     .05       0    4997     .03       0    5003     .05       0
  6031.6     .08       0    6130     .05       0  6489.5     .08       0
  6976.9     .05       0
Bank Sta=4997,5003
XS Rating Curve= 0 ,0
Exp/Cntr=0.3,0.1

Type RM Length L Ch R = 1 ,28928   ,423,423,423
BEGIN DESCRIPTION:
SALT CREEK 38.0
END DESCRIPTION:
XS GIS Cut Line= 5
      2279005.95     13395158.09      2278949.52     13395522.69
      2278940.84     13395718.87      2278740.32     13397235.93
      2278387.77     13397396.83
#Sta/Elev= 30
  4548.8  258.83  4566.3  258.52  4571.4   256.9  4689.2  255.52  4780.3   252.7
  4922.3  252.48  4961.9  251.17    4997  244.08  4999.8  243.58    5003  244.08
    5022  251.73    5032  253.24  5170.4  250.57  5323.8  252.89  5384.4  251.14
  5576.1  249.94  6040.1  253.51  6342.7  262.81  6372.9  265.65  6413.3  265.59
  6453.6  268.62    6494  268.43  6534.3  271.25  6564.6  271.13    6615  274.04
  6768.1  276.29  6804.9  278.75  6879.5  279.49    6911  281.91  7031.9  283.93
#Mann= 4 ,-1 , 0
  4548.8     .08       0    4997     .07       0    5003     .08       0
  5170.4     .05       0
Bank Sta=4997,5003
XS Rating Curve= 0 ,0
Exp/Cntr=0.3,0.1

Type RM Length L Ch R = 1 ,28505   ,553,553,553
BEGIN DESCRIPTION:
SALT CREEK 37.0
END DESCRIPTION:
XS GIS Cut Line= 3
      2279187.72     13393046.86      2278587.72     13395446.85
      2277887.72     13396996.86
#Sta/Elev= 30
  2520.3  282.12  2584.8  278.26  2954.7  263.23  3096.8  258.38    3332  253.08
  3468.6   251.7  3509.8  248.24    3716  252.26  3870.6   250.7  4527.5  250.74
  4621.3  250.83  4929.7  252.89  4952.9  250.77  4976.1  248.71  4988.6  245.21
  4991.3  244.71  4994.6  245.21    5038  250.91  5235.6  251.52  5492.8  249.07
  5509.9  250.53  5751.3   248.3  5992.7  253.03  6157.2  259.45  6190.2  258.99
  6242.5  262.27  6392.2  264.98  6497.4  271.09  6541.9  270.83  6694.9  276.93
#Mann= 9 ,-1 , 0
  2520.3      .1       0  2584.8     .05       0  2954.7      .1       0
  3096.8     .08       0    3332     .05       0  4527.5      .1       0
  4621.3     .05       0  4988.6     .03       0  4994.6     .05       0
#XS Ineff= 1 ,-1
 2965.91 3713.07  254.81
Permanent Ineff=
       F
Bank Sta=4952.9,5038
XS Rating Curve= 0 ,0
Exp/Cntr=0.3,0.1

Type RM Length L Ch R = 1 ,27952   ,1071,1071,1071
BEGIN DESCRIPTION:
SALT CREEK 36.0
END DESCRIPTION:
XS GIS Cut Line= 3
      2279037.73     13393146.83      2278037.72     13395546.85
      2277787.71      13397096.9
#Sta/Elev= 30
  2437.8  275.91  2512.1   272.6  2787.1  263.75    3142  251.19  3510.3  249.95
  3553.7  246.38  3593.2  252.34  4251.1  249.53  4503.2  248.92  4929.5  249.33
  4946.3  246.79  4951.7  248.09    4962  242.97  4970.1  242.05  4975.5  244.76
  4980.7  241.22  4983.4  240.72  4986.7  241.22  5016.2  241.89  5023.2  246.61
  5028.6  244.81  5066.2  249.55  5088.5  249.95  5493.6  247.34    5676  249.98
  6020.4  259.12  6060.9  262.23  6212.8   265.5  6273.6  269.44  6607.9  280.13
#Mann= 7 ,-1 , 0
  2437.8     .05       0  2512.1     .08       0  2787.1     .05       0
  4251.1      .1       0  4503.2     .05       0  4980.7     .03       0
  4986.7     .05       0
#XS Ineff= 1 ,-1
 2940.34 3590.91  253.89
Permanent Ineff=
       F
Bank Sta=4929.5,5088.5
XS Rating Curve= 0 ,0
Exp/Cntr=0.3,0.1

Type RM Length L Ch R = 1 ,26881   ,623,623,623
BEGIN DESCRIPTION:
SALT CREEK 35.0
END DESCRIPTION:
XS GIS Cut Line= 3
      2279287.71     13392646.86      2277087.72     13395846.85
      2276787.71     13396546.89
#Sta/Elev= 30
  1086.2  293.68  1114.6  291.47  1293.9  289.08  1428.7  285.02    1438  284.55
    1569  280.95  1619.3  277.91  1750.2  276.22  1906.1  270.27  1948.1  270.52
  1992.8  266.88  2121.3  263.63  2431.8  250.79  2488.6  251.12  2539.4  247.98
  2704.4  249.27  2739.6  245.62  2781.8  247.63    2877  251.07    3587  247.38
  3631.1   247.3  4588.6  248.99  4920.1  247.25    4984  244.94  4999.1  238.47
  5001.9  237.97  5005.1  238.47  5023.9   244.2  5067.4  248.77  5731.1  273.58
#Mann= 11 ,-1 , 0
  1086.2     .05       0  1428.7      .1       0    1438     .05       0
    1569     .08       0  1750.2     .05       0  2704.4      .1       0
  2781.8     .05       0    3587      .1       0  3631.1     .05       0
  4999.1     .03       0  5005.1     .05       0
#XS Ineff= 1 ,-1
  2110.8 2880.68  254.62
Permanent Ineff=
       F
Bank Sta=4920.1,5067.4
XS Rating Curve= 0 ,0
Exp/Cntr=0.3,0.1

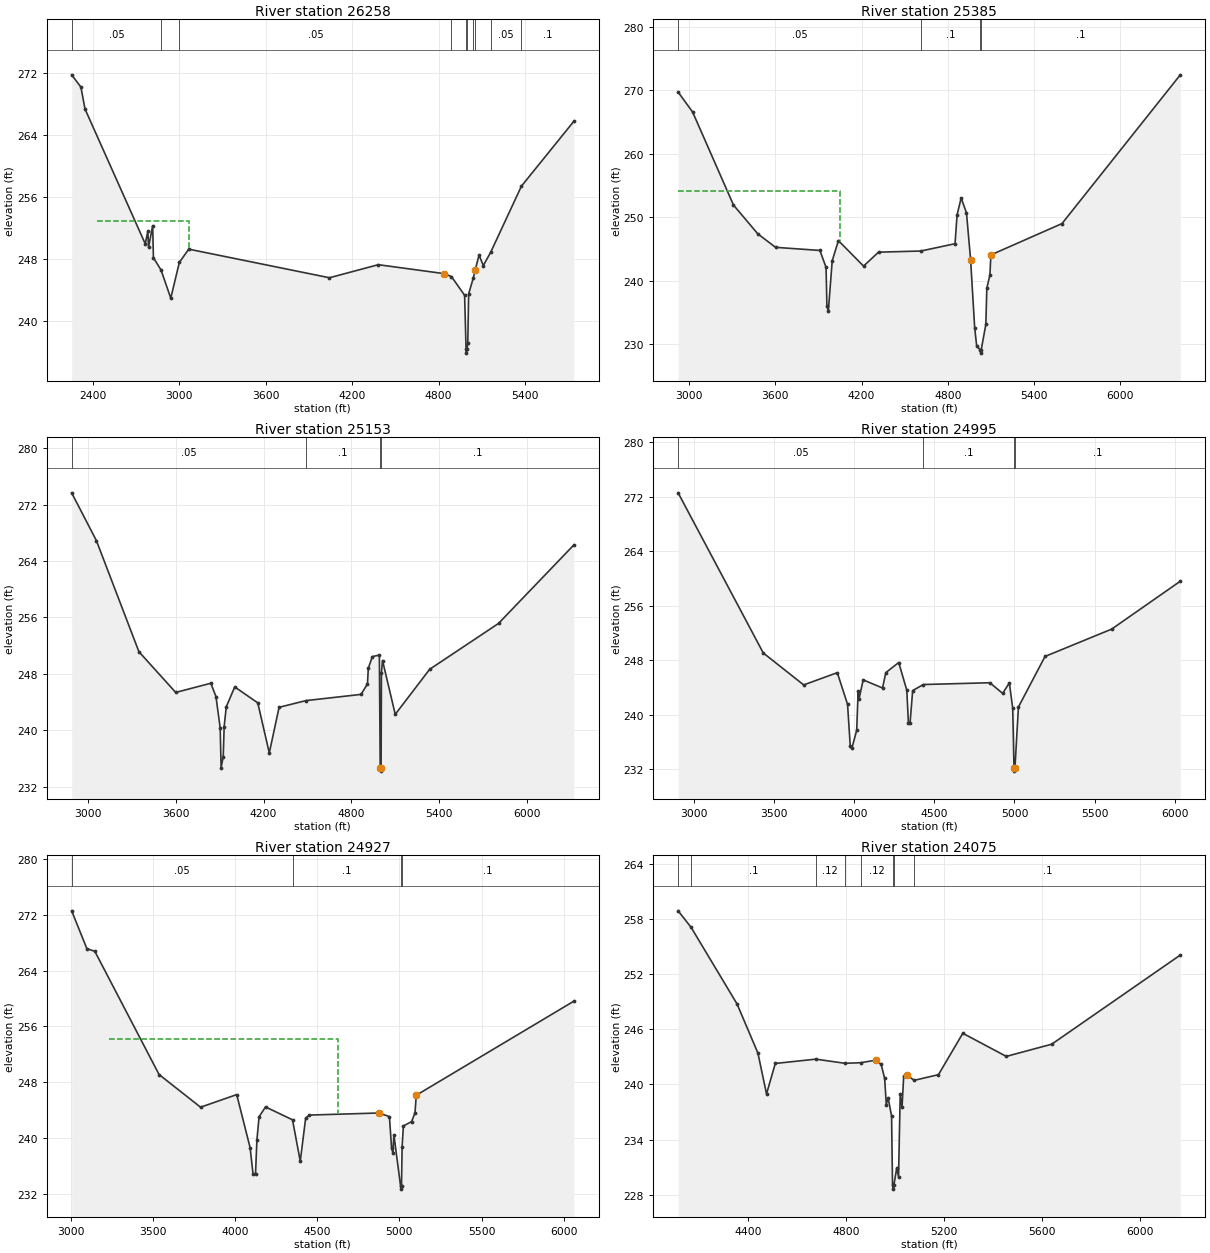
Type RM Length L Ch R = 1 ,26258   ,873,873,873
BEGIN DESCRIPTION:
SALT CREEK 34.0
END DESCRIPTION:
XS GIS Cut Line= 3
      2277909.22     13393095.82      2277576.72     13394253.17
      2276304.28     13396145.84
#Sta/Elev= 30
  2253.5  271.82  2317.7  270.24  2346.2   267.4  2764.4  249.95    2782  251.59
  2787.2  249.52  2815.7  252.31  2820.9  248.17  2873.6  246.58  2941.3  242.93
  3000.7  247.55  3066.1  249.27  4042.4  245.57  4381.4  247.26  4835.8  246.11
  4888.8  245.73  4980.4   243.3  4990.4  236.32  4993.1  235.82  4996.4  236.32
  5002.3   237.1  5008.4   243.5  5040.5  245.52  5052.7  246.52  5054.7  246.64
  5080.4   248.5  5110.3  247.15  5162.1   248.9  5374.6  257.42  5738.3  265.81
#Mann= 10 ,-1 , 0
  2253.5     .05       0  2873.6      .1       0  3000.7     .05       0
  4888.8      .1       0  4990.4     .07       0  4996.4      .1       0
  5040.5     .05       0  5054.7      .1       0  5162.1     .05       0
  5374.6      .1       0
#XS Ineff= 1 ,-1
 2427.27 3065.91  252.92
Permanent Ineff=
       F
Bank Sta=4835.8,5052.7
XS Rating Curve= 0 ,0
Exp/Cntr=0.3,0.1

Type RM Length L Ch R = 1 ,25385   ,458,458,458
BEGIN DESCRIPTION:
SALT CREEK 33.0
END DESCRIPTION:
XS GIS Cut Line= 4
      2277423.27     13393063.85      2276994.86     13393799.19
      2276393.81     13394809.46      2275364.34     13395858.11
#Sta/Elev= 30
  2923.3  269.69  3024.4  266.54  3308.7  251.91  3478.6  247.36  3601.8  245.25
  3910.4  244.76  3953.3  242.08  3959.1  236.08  3968.9  235.16  3996.1  243.13
  4039.2  246.31  4214.2   242.3  4318.5  244.49  4612.7  244.67  4851.1  245.82
  4865.4  250.37  4893.9  253.02  4930.9  250.67  4959.5   243.3  4987.8  232.62
  5001.9  229.71  5027.2   229.1  5029.9   228.6  5033.2   229.1  5065.5  233.11
  5072.5  238.82  5093.8  240.88  5100.8  244.06  5595.8  248.99  6419.4   272.4
#Mann= 4 ,-1 , 0
  2923.3     .05       0  4612.7      .1       0  5027.2     .07       0
  5033.2      .1       0
#XS Ineff= 1 ,-1
 2788.64 4047.73  254.17
Permanent Ineff=
       F
Bank Sta=4959.5,5100.8
XS Rating Curve= 0 ,0
Exp/Cntr=0.3,0.1

Type RM Length L Ch R = 1 ,25153   ,158,158,158
BEGIN DESCRIPTION:
SALT CREEK 31.1
END DESCRIPTION:
XS GIS Cut Line= 6
      2277331.48     13392966.11      2276901.81     13393821.11
      2276745.56     13394020.76      2276385.32       13394585.
      2276136.84     13394720.63      2275127.13     13395486.05
#Sta/Elev= 30
  2889.5  273.67  3058.2  266.91    3349  251.14  3600.2  245.37  3840.2  246.67
    3875  244.79    3904  240.35  3910.3  234.71  3924.8  236.25  3931.1  240.53
  3945.6  243.33  4003.4  246.15  4160.7  243.89  4239.4  236.79  4306.3  243.26
  4489.9  244.21    4866  245.09    4910  246.57  4915.7   248.8  4943.6  250.45
  4991.2  250.67    4997  234.71  4999.8  234.21    5003  234.71  5005.4  248.18
  5012.8  249.89  5099.7  242.26  5334.8  248.65    5805  255.15  6319.5  266.28
#Mann= 4 ,-1 , 0
  2889.5     .05       0  4489.9      .1       0    4997     .07       0
    5003      .1       0
Bank Sta=4997,5003
XS Rating Curve= 0 ,0
Exp/Cntr=0.3,0.1

Type RM Length L Ch R = 1 ,24995   ,920,920,920
BEGIN DESCRIPTION:
SALT CREEK 31.0
END DESCRIPTION:
XS GIS Cut Line= 4
      2277167.47     13392929.63      2276649.58     13393709.67
      2276575.42      13394234.3      2275211.83     13395198.84
#Sta/Elev= 30
  2899.2  272.59  3431.1  249.09  3683.6   244.4  3893.3   246.2  3957.4  241.56
  3974.1   235.5  3984.2  235.09  4014.5  237.74  4023.5  243.46  4028.5  242.28
  4054.9  245.14    4176  243.95  4196.2   246.2    4277  247.69  4327.5  243.62
  4337.6  238.78  4347.7  238.79  4364.1  243.57    4431  244.46  4846.2  244.72
    4926  243.16    4968   244.7  4988.9  240.97    4997  232.25  4999.8  231.75
    5003  232.25  5024.6  241.16  5190.8  248.58  5606.9  252.59  6035.6  259.62
#Mann= 4 ,-1 , 0
  2899.2     .05       0    4431      .1       0    4997     .07       0
    5003      .1       0
Bank Sta=4997,5003
XS Rating Curve= 0 ,0
Exp/Cntr=0.3,0.1

Type RM Length L Ch R = 1 ,24927   ,852,852,852
BEGIN DESCRIPTION:
SALT CREEK 31.0
END DESCRIPTION:
XS GIS Cut Line= 4
      2277167.49     13392929.61      2276649.58     13393709.67
      2276425.78     13394227.59       2275211.8     13395198.78
#Sta/Elev= 30
  3006.2  272.59  3098.9  267.16  3147.2  266.78  3538.1  249.09  3790.7   244.4
  4010.3  246.21    4092  238.58  4109.7  234.82  4124.7  234.76  4133.2  239.67
  4146.5  243.03  4185.7  244.44  4349.9  242.59    4397  236.65  4429.7   242.8
  4451.5  243.27  4875.5  243.57  4939.5  243.05  4952.5  238.52  4960.3  237.89
  4966.7  240.45    5007  233.14  5009.7  232.64    5013  233.14  5016.5   238.7
  5024.4  241.71    5074  242.33  5094.8  243.55  5102.8  246.12  6061.4  259.62
#Mann= 4 ,-1 , 0
  3006.2     .05       0  4349.9      .1       0    5007     .07       0
    5013      .1       0
#XS Ineff= 1 ,-1
 3232.67 4628.69  254.16
Permanent Ineff=
       F
Bank Sta=4875.5,5102.8
XS Rating Curve= 0 ,0
Exp/Cntr=0.3,0.1

Type RM Length L Ch R = 1 ,24075   ,589,589,589
BEGIN DESCRIPTION:
SALT CREEK 30.0
END DESCRIPTION:
XS GIS Cut Line= 3
      2276521.69     13393051.08      2275748.01     13393901.49
      2275051.88     13394469.89
#Sta/Elev= 30
  4115.6  258.93  4168.3  257.14  4355.9  248.78  4441.1  243.42  4476.2  238.97
    4512  242.29  4677.1  242.76  4795.8  242.31  4859.8  242.37  4922.2  242.65
  4943.8  242.19    4958  240.67  4964.7  237.81  4972.2  238.54  4986.3  236.56
  4990.1  229.09  4992.9  228.59  4996.1  229.09  5007.3   230.9  5014.7  229.93
  5021.5  238.94  5028.9  237.51  5035.7  240.89  5049.9     241  5078.6  240.45
  5177.6  241.07  5276.9  245.58  5454.2  243.06  5639.5  244.39    6164  254.11
#Mann= 8 ,-1 , 0
  4115.6     .05       0  4168.3      .1       0  4677.1     .12       0
  4795.8      .1       0  4859.8     .12       0  4990.1     .07       0
  4996.1     .12       0  5078.6      .1       0
Bank Sta=4922.2,5049.9
XS Rating Curve= 0 ,0
Exp/Cntr=0.3,0.1