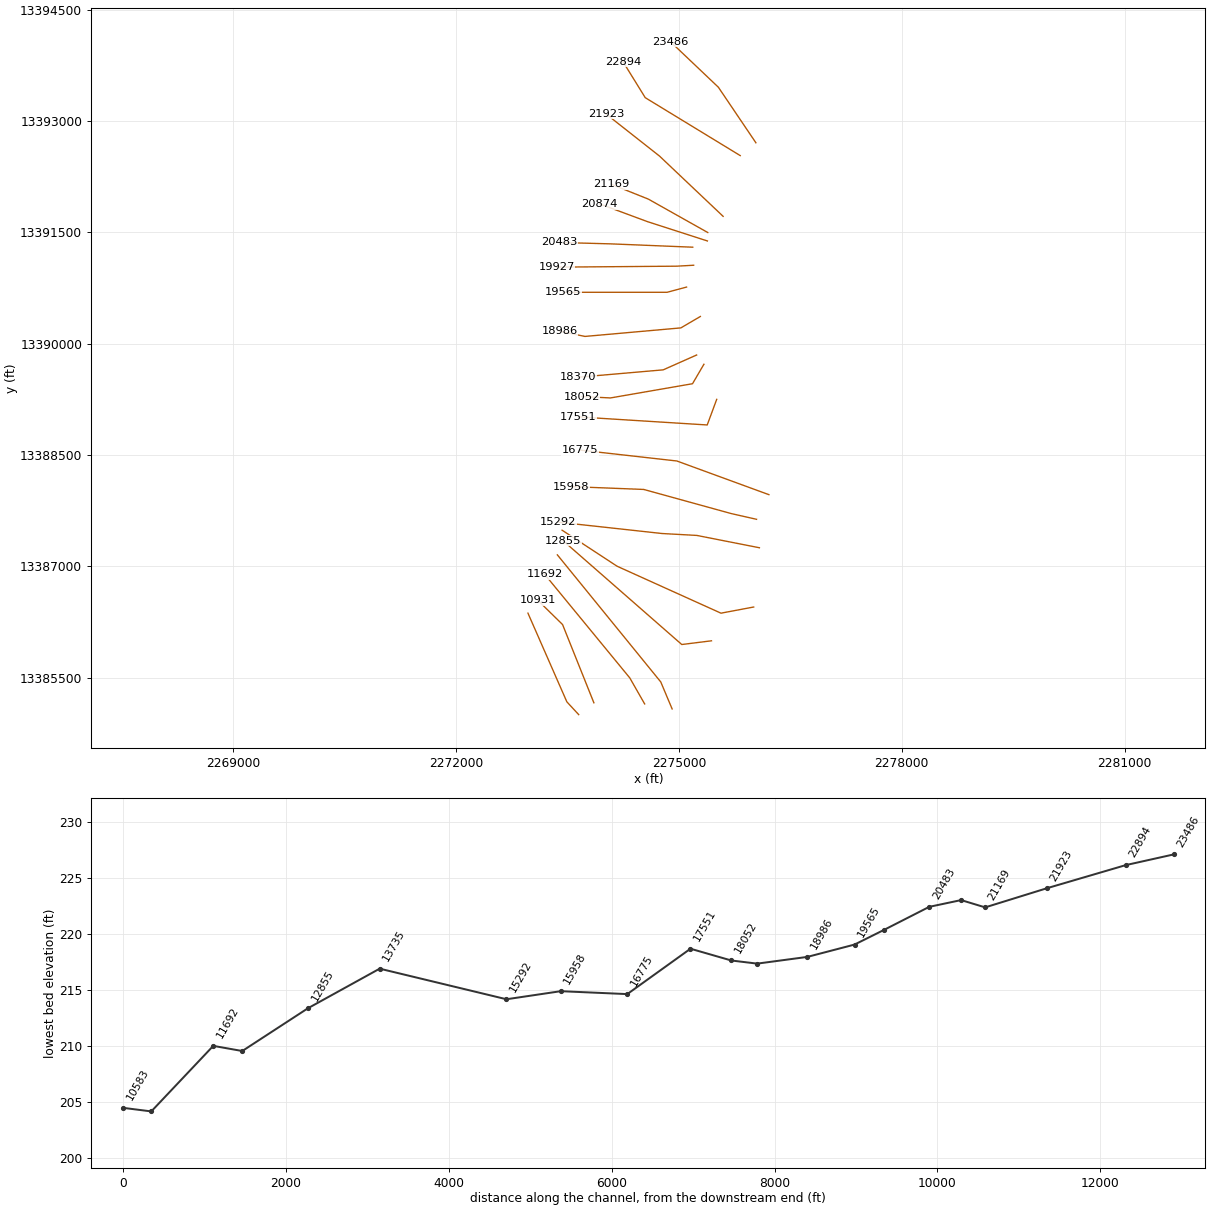
HEC-RAS study SALT CREEK.prj: SALT CREEK Base Level Engineering

--- SALT CREEK.g01 (geometry) --- (continued)

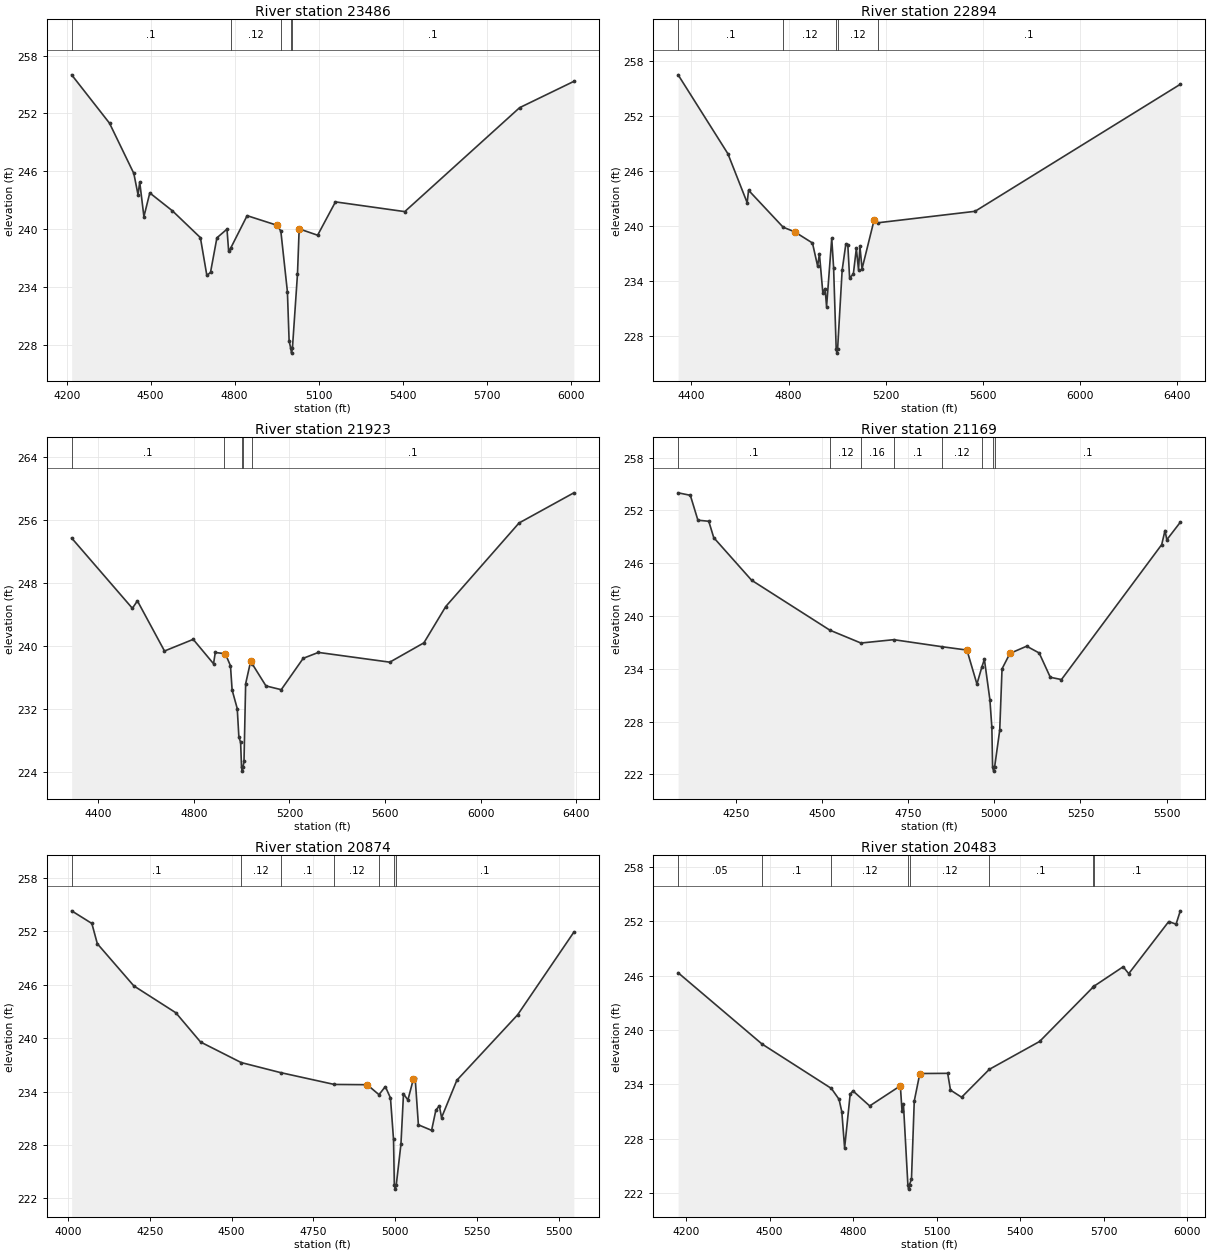
Type RM Length L Ch R = 1 ,23486   ,592,592,592
BEGIN DESCRIPTION:
SALT CREEK 29.0
END DESCRIPTION:
XS GIS Cut Line= 3
      2276035.73     13392705.82      2275530.61     13393453.91
      2274884.83     13394067.71
#Sta/Elev= 30
  4217.8     256    4353  250.98  4439.9  245.76  4454.9  243.55  4460.9  244.87
  4475.9  241.28  4496.9  243.74  4577.8  241.88  4677.6   239.1  4700.7  235.17
  4713.8   235.5  4736.6  239.08  4772.6  239.98  4778.6  237.66  4785.3  237.98
  4844.5  241.38  4952.5  240.37    4965  239.76  4988.4  233.48  4994.5  228.37
  5000.3  227.61  5003.1  227.11  5006.3  227.61  5024.4  235.33  5030.4  240.01
  5096.3  239.35    5160  242.81  5407.5   241.8  5817.7  252.59  6011.4  255.32
#Mann= 5 ,-1 , 0
  4217.8      .1       0  4785.3     .12       0    4965      .1       0
  5000.3     .07       0  5006.3      .1       0
Bank Sta=4952.5,5030.4
XS Rating Curve= 0 ,0
Exp/Cntr=0.3,0.1

Type RM Length L Ch R = 1 ,22894   ,971,971,971
BEGIN DESCRIPTION:
SALT CREEK 28.0
END DESCRIPTION:
XS GIS Cut Line= 3
       2275824.7     13392533.18      2274545.92     13393313.24
      2274245.39     13393799.19
#Sta/Elev= 30
  4345.1  256.45  4550.2  247.86  4629.6  242.53  4635.4  243.88  4777.9  239.86
  4825.2  239.36  4898.7  238.14    4920  235.62  4927.3  236.98  4941.3  232.75
  4950.7  233.17  4956.8  231.21  4978.1  238.64  4985.8  235.47  4996.4  226.65
  4999.2  226.15  5002.4  226.65    5021  235.17  5036.2  238.03  5044.4  237.92
  5051.7  234.35  5067.1  234.75  5079.5  237.55  5088.4  235.23  5094.3  237.78
    5103  235.33  5152.4  240.61  5167.7  240.34  5568.6  241.59  6414.4  255.42
#Mann= 5 ,-1 , 0
  4345.1      .1       0  4777.9     .12       0  4996.4     .07       0
  5002.4     .12       0  5167.7      .1       0
Bank Sta=4825.2,5152.4
XS Rating Curve= 0 ,0
Exp/Cntr=0.3,0.1

Type RM Length L Ch R = 1 ,21923   ,754,754,754
BEGIN DESCRIPTION:
SALT CREEK 27.0
END DESCRIPTION:
XS GIS Cut Line= 3
      2275594.53     13391714.74      2274737.74     13392526.76
       2274015.2     13393095.85
#Sta/Elev= 30
  4289.1  253.73  4543.1  244.79  4564.1  245.74  4677.4  239.36  4797.5  240.84
  4882.5  237.74  4889.8  239.17  4927.2  239.03  4932.2  238.99  4953.3  237.48
  4960.2   234.4  4981.6  232.04  4988.5   228.4  4995.7  227.75  4999.6  224.58
  5002.4  224.08  5005.6  224.58  5009.9  225.34  5016.8   235.2  5038.2  238.12
  5044.3  237.72  5101.7  234.92  5165.6  234.44  5257.5  238.43    5321  239.18
  5619.6  237.94  5762.3   240.4  5853.7  245.02    6160  255.64  6389.3  259.48
#Mann= 5 ,-1 , 0
  4289.1      .1       0  4927.2     .12       0  4999.6     .07       0
  5005.6     .12       0  5044.3      .1       0
Bank Sta=4932.2,5038.2
XS Rating Curve= 0 ,0
Exp/Cntr=0.3,0.1

Type RM Length L Ch R = 1 ,21169   ,295,295,295
BEGIN DESCRIPTION:
SALT CREEK 26.0
END DESCRIPTION:
XS GIS Cut Line= 3
      2275387.72     13391496.86      2274587.72     13391946.85
      2274087.71     13392146.86
#Sta/Elev= 30
  4083.2  253.99  4118.6  253.71  4140.6  250.88  4172.1  250.76  4186.5   248.9
  4296.4  244.06  4523.3  238.39  4613.3  236.93  4708.6  237.31  4848.7  236.51
  4920.8  236.13  4949.8  232.27  4964.2  234.22  4971.4  235.08  4987.4  230.49
  4993.1  227.34  4995.2  222.88    4998  222.38  5001.2  222.88  5015.9  227.03
  5022.6     234  5045.5  235.75    5094  236.57  5130.3   235.8  5162.6  233.04
  5194.9  232.78  5485.7  248.11  5495.2  249.71  5500.5  248.66  5539.6  250.65
#Mann= 8 ,-1 , 0
  4083.2      .1       0  4523.3     .12       0  4613.3     .16       0
  4708.6      .1       0  4848.7     .12       0  4964.2      .1       0
  4995.2     .07       0  5001.2      .1       0
Bank Sta=4920.8,5045.5
XS Rating Curve= 0 ,0
Exp/Cntr=0.3,0.1

Type RM Length L Ch R = 1 ,20874   ,391,391,391
BEGIN DESCRIPTION:
SALT CREEK 25.0
END DESCRIPTION:
XS GIS Cut Line= 3
      2275382.35      13391383.2      2274575.08     13391643.61
      2273932.78     13391881.89
#Sta/Elev= 30
  4011.8  254.32  4073.5   252.9  4090.2  250.62  4201.7  245.88  4329.9  242.86
  4405.4  239.57  4529.5  237.26  4649.8  236.13  4813.5   234.8  4914.2  234.77
  4950.1  233.65  4969.6  234.56  4985.2  233.28  4994.6  228.61    4997  223.53
  4999.7  223.03    5003  223.53  5017.2  228.08    5025  233.74  5038.5  233.05
  5055.4  235.44  5060.7  235.47  5070.5  230.26  5110.8  229.64  5123.9  231.92
  5134.5  232.39  5141.2  231.07  5187.9  235.27  5373.5  242.63  5545.1  251.92
#Mann= 7 ,-1 , 0
  4011.8      .1       0  4529.5     .12       0  4649.8      .1       0
  4813.5     .12       0  4950.1      .1       0    4997     .07       0
    5003      .1       0
Bank Sta=4914.2,5055.4
XS Rating Curve= 0 ,0
Exp/Cntr=0.3,0.1

Type RM Length L Ch R = 1 ,20483   ,556,556,556
BEGIN DESCRIPTION:
Mapping XS 802da3ce
END DESCRIPTION:
XS GIS Cut Line= 3
      2275185.31      13391299.1      2274085.54     13391343.86
      2273382.49     13391363.03
#Sta/Elev= 30
  4171.7  246.33    4473  238.46  4722.3  233.55  4749.8  232.35  4759.8  230.96
  4769.8  226.98  4789.8  232.92  4799.8  233.28  4859.9  231.62    4970  233.84
  4976.1  231.04  4981.1  231.82    4997  222.93  4999.7  222.43    5003  222.93
    5010  223.55    5020  232.16    5040   235.2  5140.1  235.22  5150.1  233.37
  5190.1  232.58  5289.6  235.66  5470.3  238.74  5662.6  244.75  5664.5  244.82
  5770.4  246.99  5790.4  246.23    5934  251.98  5960.5   251.7  5975.7  253.17
#Mann= 8 ,-1 , 0
  4171.7     .05       0    4473      .1       0  4722.3     .12       0
    4997     .07       0    5003     .12       0  5289.6      .1       0
  5662.6     .05       0  5664.5      .1       0
Bank Sta=4970,5040
XS Rating Curve= 0 ,0
Exp/Cntr=0.3,0.1

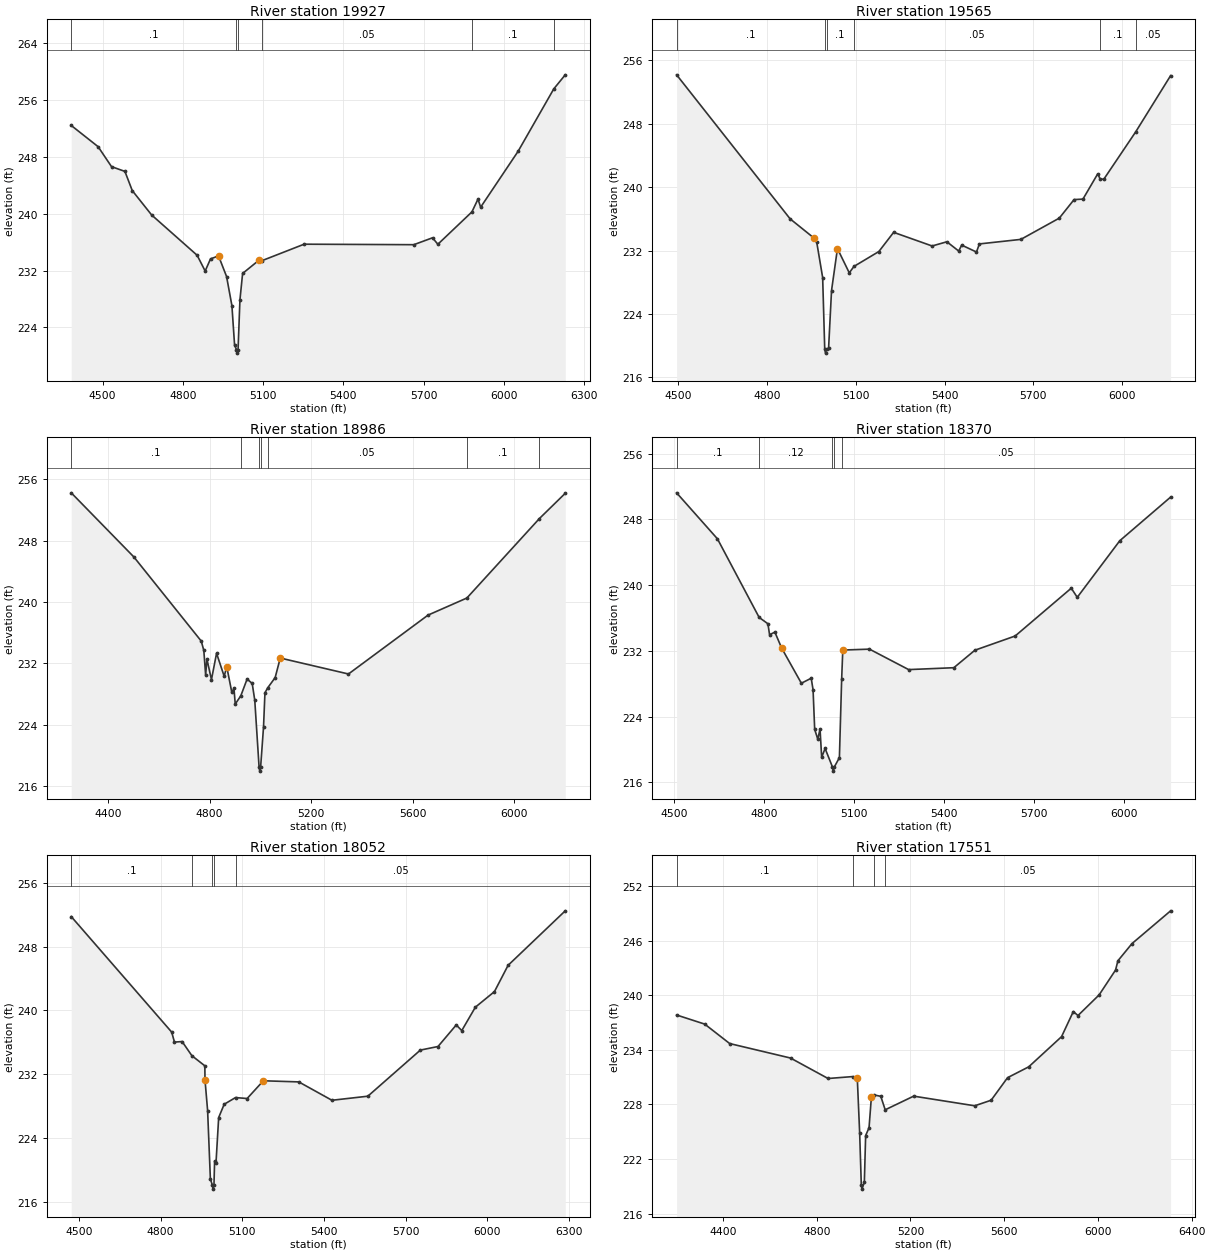
Type RM Length L Ch R = 1 ,19927   ,362,362,362
BEGIN DESCRIPTION:
SALT CREEK 24.0
END DESCRIPTION:
XS GIS Cut Line= 3
      2275198.07     13391056.12      2274967.93     13391043.33
      2273351.47     13391030.56
#Sta/Elev= 30
  4382.6  252.43  4483.1  249.44  4533.2  246.63  4583.3  245.96  4610.7  243.26
  4683.3  239.82  4853.3  234.15  4883.3  231.93  4903.3  233.64  4933.3  234.06
  4963.3  231.16  4983.3  227.06  4993.3   221.5  5000.3  220.87  5003.1  220.37
  5006.3  220.87  5013.3  227.86  5023.3  231.59  5083.3  233.42    5095  233.38
  5253.3  235.71  5663.3  235.64  5733.3  236.61  5753.3   235.7  5880.7  240.26
  5903.3  242.06  5913.3  240.92  6053.3  248.79  6186.7  257.58  6229.6  259.56
#Mann= 6 ,-1 , 0
  4382.6      .1       0  5000.3     .07       0  5006.3      .1       0
    5095     .05       0  5880.7      .1       0  6186.7     .05       0
Bank Sta=4933.3,5083.3
XS Rating Curve= 0 ,0
Exp/Cntr=0.3,0.1

Type RM Length L Ch R = 1 ,19565   ,579,579,579
BEGIN DESCRIPTION:
SALT CREEK 23.0
END DESCRIPTION:
XS GIS Cut Line= 3
      2275102.21       13390762.      2274840.05     13390691.66
      2273441.28     13390691.66
#Sta/Elev= 30
  4493.9  254.15  4877.7  235.99  4957.7  233.59  4967.7  233.03  4987.7  228.59
  4994.7  219.56  4997.4  219.06  5000.7  219.56  5007.7  219.65  5017.7  226.95
  5037.7  232.24  5077.7  229.18  5093.4  229.99  5177.7  231.87  5227.7  234.29
  5357.7  232.57  5407.7   233.1  5447.7  231.93  5457.7  232.68  5507.7  231.81
  5517.7  232.83  5657.7   233.4  5787.7  236.08  5837.7  238.42  5867.7  238.48
  5917.7  241.67  5925.4  241.05  5937.7  240.96  6045.9  246.95  6164.1  254.05
#Mann= 6 ,-1 , 0
  4493.9      .1       0  4994.7     .07       0  5000.7      .1       0
  5093.4     .05       0  5925.4      .1       0  6045.9     .05       0
Bank Sta=4957.7,5037.7
XS Rating Curve= 0 ,0
Exp/Cntr=0.3,0.1

Type RM Length L Ch R = 1 ,18986   ,616,616,616
BEGIN DESCRIPTION:
SALT CREEK 22.0
END DESCRIPTION:
XS GIS Cut Line= 4
      2275287.61     13390365.55      2275025.48      13390212.1
      2273733.87     13390097.01      2273394.96     13390167.35
#Sta/Elev= 30
  4254.9  254.26  4501.8  245.89  4767.2  234.92  4777.3   233.7  4784.5  230.49
  4789.5  232.58  4807.4  229.89  4827.5  233.33  4857.6  230.33  4867.6  231.59
  4887.7  228.22  4896.1  228.75  4901.1  226.71    4923  227.78  4947.9  229.97
    4968  229.39  4978.1   227.2  4995.1  218.46  4997.9  217.96  5001.1  218.46
  5012.6  223.73  5018.2  228.18    5029  228.82  5058.4  230.16  5078.5  232.71
  5347.3  230.63  5660.8  238.31  5813.9  240.54  6099.8  250.91  6201.5   254.2
#Mann= 7 ,-1 , 0
  4254.9      .1       0    4923     .12       0  4995.1     .07       0
  5001.1     .12       0    5029     .05       0  5813.9      .1       0
  6099.8     .05       0
Bank Sta=4867.6,5078.5
XS Rating Curve= 0 ,0
Exp/Cntr=0.3,0.1

Type RM Length L Ch R = 1 ,18370   ,318,318,318
BEGIN DESCRIPTION:
SALT CREEK 21.0
END DESCRIPTION:
XS GIS Cut Line= 3
      2275237.75     13389846.87      2274787.72     13389646.85
      2273637.74     13389546.86
#Sta/Elev= 30
  4508.6  251.24  4644.7  245.64  4783.8  236.07    4813   235.3  4818.5  233.97
  4836.2  234.28  4858.8  232.34  4924.5  228.06  4957.3  228.67  4963.5  227.27
  4968.9  222.44  4979.2  221.25  4986.7  222.49  4992.2  219.04  5003.6  220.12
  5028.2  217.86  5030.9  217.36  5034.2  217.86  5051.3     219  5058.8  228.56
  5062.6   232.1  5151.6  232.21  5282.1  229.72  5432.7  229.95    5503  232.08
  5637.2  233.81  5824.2  239.63  5844.2  238.52    5986  245.41  6155.4  250.72
#Mann= 5 ,-1 , 0
  4508.6      .1       0  4783.8     .12       0  5028.2     .07       0
  5034.2     .12       0  5058.8     .05       0
Bank Sta=4858.8,5062.6
XS Rating Curve= 0 ,0
Exp/Cntr=0.3,0.1

Type RM Length L Ch R = 1 ,18052   ,501,501,501
BEGIN DESCRIPTION:
SALT CREEK 20.0
END DESCRIPTION:
XS GIS Cut Line= 4
      2275335.66     13389721.92      2275182.37     13389460.06
      2274077.52     13389268.47      2273687.96     13389287.62
#Sta/Elev= 30
  4471.7  251.75  4840.7  237.29  4850.9  236.04    4879  236.11  4914.9  234.34
  4962.5  233.07 4963.07  231.32  4972.7  227.46  4982.8  218.94    4990  218.14
  4992.7  217.64    4996  218.14  4998.4  221.17  5003.5  220.94  5013.3   226.6
  5033.6  228.26  5075.2   229.1  5117.8  228.98  5177.5   231.2  5307.6  231.06
  5429.4  228.76  5561.3  229.27  5754.2  235.04  5819.1  235.49  5886.1  238.19
  5906.3  237.48  5956.3  240.41  6026.4  242.36  6076.5  245.65  6286.5  252.47
#Mann= 5 ,-1 , 0
  4471.7      .1       0  4914.9     .12       0    4990     .07       0
    4996     .12       0  5075.2     .05       0
Bank Sta=4963.07,5177.5
XS Rating Curve= 0 ,0
Exp/Cntr=0.3,0.1

Type RM Length L Ch R = 1 ,17551   ,776,776,776
BEGIN DESCRIPTION:
SALT CREEK 19.0
END DESCRIPTION:
XS GIS Cut Line= 3
      2275508.08     13389249.32      2275380.35     13388904.44
      2273643.21     13389013.01
#Sta/Elev= 30
  4201.9  237.83  4321.8  236.83  4428.5  234.69    4688   233.1  4848.3  230.85
    4953  231.06  4973.1  230.85  4983.1  224.88  4990.1  219.19  4992.9  218.69
  5003.1  219.45  5008.7  224.58  5023.2  225.44  5033.2  228.83  5043.2  229.05
  5073.3  228.89  5092.1  227.41  5213.6  228.91  5474.1  227.85  5544.2  228.46
  5614.3  230.94  5704.5  232.13  5844.8  235.45  5894.9  238.21  5914.9  237.77
  6005.1  240.04  6075.2  242.77  6085.3  243.79  6145.4  245.68  6310.2  249.28
#Mann= 4 ,-1 , 0
  4201.9      .1       0    4953     .07       0  5043.2      .1       0
  5092.1     .05       0
Bank Sta=4973.1,5033.2
XS Rating Curve= 0 ,0
Exp/Cntr=0.3,0.1

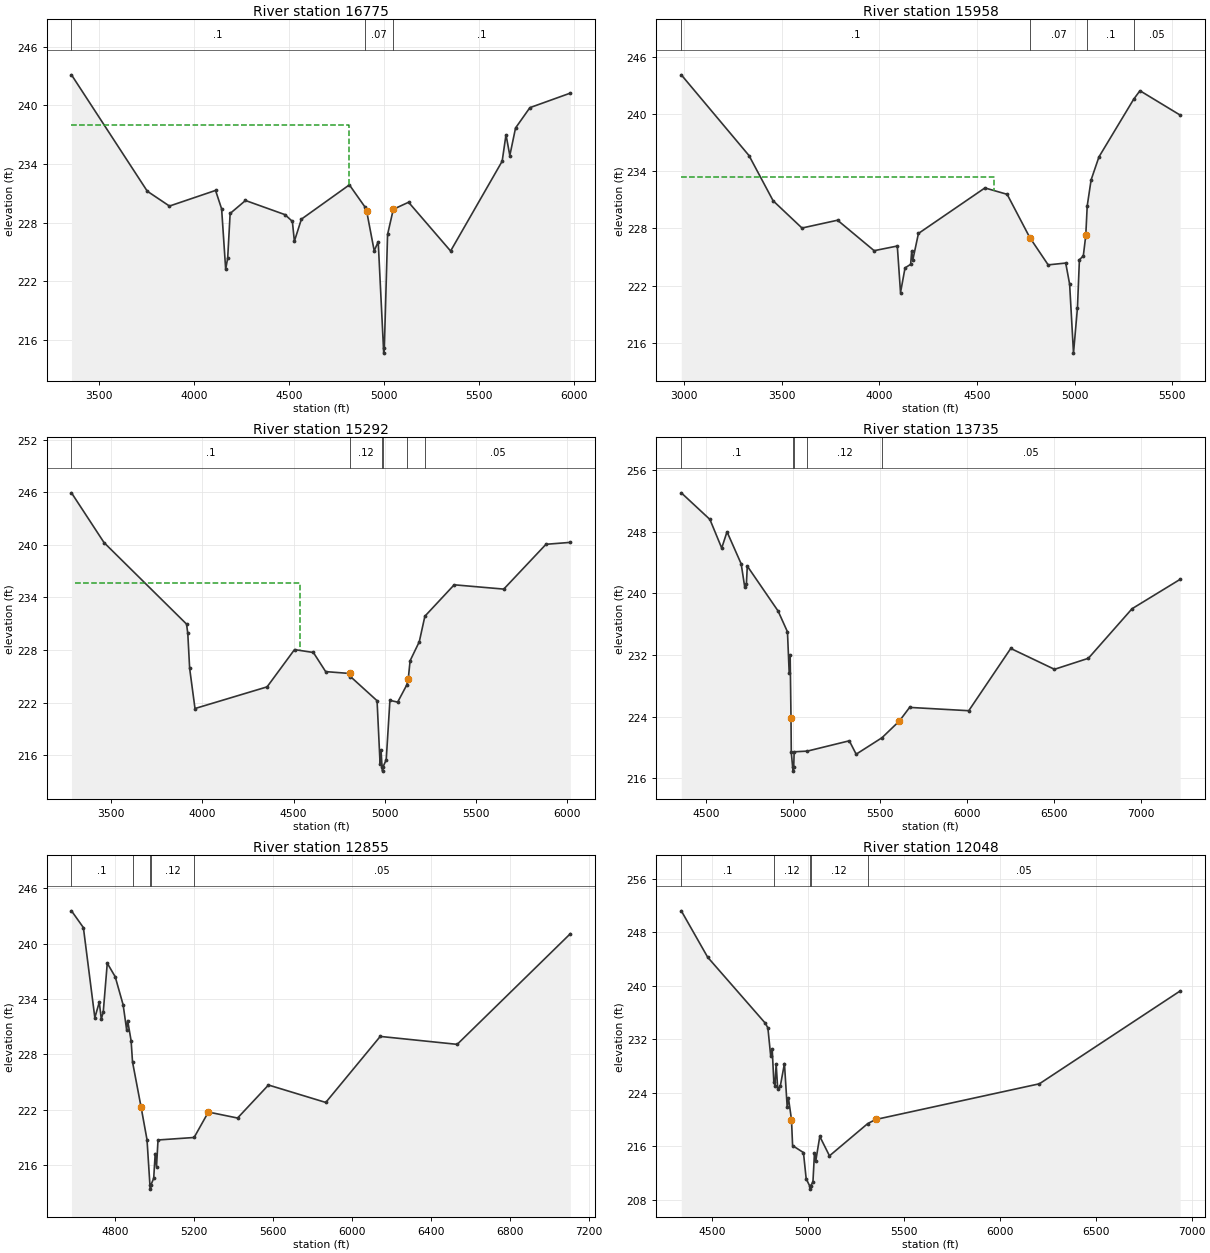
Type RM Length L Ch R = 1 ,16775   ,817,817,817
BEGIN DESCRIPTION:
SALT CREEK 18.0
END DESCRIPTION:
XS GIS Cut Line= 3
      2276210.62     13387965.62      2274971.62     13388419.07
      2273670.73     13388565.74
#Sta/Elev= 30
  3354.1  243.12  3753.5  231.21  3870.3  229.69  4113.2  231.29  4145.2   229.4
  4166.5  223.23  4177.1  224.37    4190  228.93  4270.9  230.26  4479.3  228.81
  4517.9  228.12  4528.5  226.09  4565.5  228.35  4818.3  231.86  4898.8  229.64
  4908.9  229.21  4949.1  225.11  4970.2  226.04  4999.2  214.64  5002.4  215.14
  5019.5  226.78  5049.7  229.36  5130.2  230.08  5351.6  225.09  5623.3  234.28
  5643.5  236.99  5663.6  234.86  5693.8  237.68  5769.3  239.76  5982.6  241.25
#Mann= 3 ,-1 , 0
  3354.1      .1       0  4898.8     .07       0  5049.7      .1       0
#XS Ineff= 1 ,-1
 3351.14 4818.75  237.95
Permanent Ineff=
       F
Bank Sta=4908.9,5049.7
XS Rating Curve= 0 ,0
Exp/Cntr=0.3,0.1

Type RM Length L Ch R = 1 ,15958   ,666,666,666
BEGIN DESCRIPTION:
SALT CREEK 17.0
END DESCRIPTION:
XS GIS Cut Line= 4
      2276044.51     13387633.55      2275706.06     13387710.18
      2274524.57     13388035.89       2273541.9     13388074.17
#Sta/Elev= 30
    2985  244.13    3332  235.65  3455.6   230.9  3603.4  228.04  3785.7  228.86
  3973.1  225.66  4091.8  226.15  4108.3  221.26  4131.4  223.85  4160.1  224.23
  4165.7  225.65  4170.9  224.66  4200.1  227.47  4540.6  232.25  4654.5  231.58
  4770.6  227.04  4864.7  224.17  4954.7  224.36  4974.7  222.14  4994.5   214.9
  5014.8  219.67  5024.8  224.71  5044.8  225.11 5057.39  227.26  5064.8  230.36
  5084.8   233.1  5124.9  235.51  5302.9  241.57    5335  242.46    5541   239.9
#Mann= 4 ,-1 , 0
    2985      .1       0  4770.6     .07       0  5064.8      .1       0
  5302.9     .05       0
#XS Ineff= 1 ,-1
 2983.24 4588.07  233.39
Permanent Ineff=
       F
Bank Sta=4770.6,5057.39
XS Rating Curve= 0 ,0
Exp/Cntr=0.3,0.1

Type RM Length L Ch R = 1 ,15292   ,1557,1557,1557
BEGIN DESCRIPTION:
SALT CREEK 16.0
END DESCRIPTION:
XS GIS Cut Line= 4
       2276082.9     13387250.35      2275239.85     13387416.41
      2274773.64     13387441.95      2273374.97     13387595.23
#Sta/Elev= 30
  3283.4  245.92  3461.9  240.24  3913.8  230.95  3920.6  229.88  3930.8  225.89
  3960.1  221.32  4355.1  223.79  4505.3  228.04  4608.7  227.71  4675.9  225.53
  4806.7  225.32  4811.5  224.97  4957.6  222.21  4974.2  214.99  4979.3   216.6
  4984.7  214.68  4987.5  214.18  4990.7  214.68  5007.8  215.48    5028  222.25
  5070.4  222.05  5120.4  224.01  5128.6  224.72  5138.6  226.77  5188.9  228.94
  5219.6  231.85  5380.1  235.43  5651.7  234.94  5883.1  240.05  6016.6  240.27
#Mann= 6 ,-1 , 0
  3283.4      .1       0  4811.5     .12       0  4984.7     .07       0
  4990.7     .12       0  5120.4      .1       0  5219.6     .05       0
#XS Ineff= 1 ,-1
 3300.28 4533.24  235.68
Permanent Ineff=
       F
Bank Sta=4806.7,5128.6
XS Rating Curve= 0 ,0
Exp/Cntr=0.3,0.1

Type RM Length L Ch R = 1 ,13735   ,880,880,880
BEGIN DESCRIPTION:
SALT CREEK 15.0
END DESCRIPTION:
XS GIS Cut Line= 4
      2276006.19     13386452.05      2275565.56     13386369.04
      2274166.93     13387001.29      2273426.14     13387486.64
#Sta/Elev= 30
  4355.4  253.07  4520.1  249.61  4587.9  245.89  4618.4  248.01  4699.8  243.84
  4720.2  240.84  4729.9  241.26    4735  243.55  4912.2  237.71    4966  235.01
    4976  229.64  4981.5  231.96 4986.36  223.81    4988  219.34  4995.9  217.41
  4998.7  216.91  5001.9  217.41  5004.6  219.42  5080.1  219.51  5321.6  220.85
  5361.1  219.11  5509.6  221.25  5609.9  223.43  5668.4  225.19  6008.6  224.76
    6250  232.85  6501.5  230.14  6696.4  231.57  6947.6  238.01  7224.3  241.83
#Mann= 5 ,-1 , 0
  4355.4      .1       0  4995.9     .07       0  5001.9      .1       0
  5080.1     .12       0  5509.6     .05       0
Bank Sta=4986.36,5609.9
XS Rating Curve= 0 ,0
Exp/Cntr=0.3,0.1

Type RM Length L Ch R = 1 ,12855   ,807,807,807
BEGIN DESCRIPTION:
SALT CREEK 14.0
END DESCRIPTION:
XS GIS Cut Line= 3
      2275437.67     13385996.85      2275037.72     13385946.85
      2273437.72     13387346.86
#Sta/Elev= 30
  4578.6  243.56    4639  241.74    4697  231.97  4719.6  233.66  4729.7   231.8
  4739.8  232.63    4760  237.88  4800.3  236.41  4840.6  233.35  4858.2  230.66
  4863.3  231.66  4880.9  229.47    4888  227.18  4931.3  222.29  4961.5  218.74
  4976.1  213.88  4978.9  213.38  4982.1  213.88  4995.4  214.55    5003  217.23
  5009.7  215.82  5017.3  218.71  5200.2  218.98  5272.6  221.74  5420.6  221.09
  5577.2  224.67  5867.7  222.78  6143.9  229.94    6534  229.08  7107.7  241.08
#Mann= 5 ,-1 , 0
  4578.6      .1       0    4888     .12       0  4976.1     .07       0
  4982.1     .12       0  5200.2     .05       0
Bank Sta=4931.3,5272.6
XS Rating Curve= 0 ,0
Exp/Cntr=0.3,0.1

Type RM Length L Ch R = 1 ,12048   ,356,356,356
BEGIN DESCRIPTION:
SALT CREEK 13.0
END DESCRIPTION:
XS GIS Cut Line= 3
      2274907.76     13385078.97      2274754.48     13385443.01
      2273362.24     13387154.57
#Sta/Elev= 30
    4339   251.2  4476.6  244.26  4777.6  234.37  4790.6  233.67    4805  229.54
  4812.9  230.57  4821.5  225.66  4827.3  225.04  4833.7  228.31  4841.7  224.59
    4855  224.92  4876.9  228.35  4891.2  221.87  4897.7  223.18 4913.64  219.97
  4919.4  216.07    4976  215.03  4990.3   211.1  5008.1  210.06  5010.9  209.56
  5014.1  210.06  5025.5  210.63  5033.4  214.92  5039.9  213.72  5061.2  217.45
  5111.7  214.54  5311.3  219.37    5353  219.98  6206.3  225.32  6940.3  239.21
#Mann= 5 ,-1 , 0
    4339      .1       0  4821.5     .12       0  5008.1     .07       0
  5014.1     .12       0  5311.3     .05       0
Bank Sta=4913.64,5353
XS Rating Curve= 0 ,0
Exp/Cntr=0.3,0.1

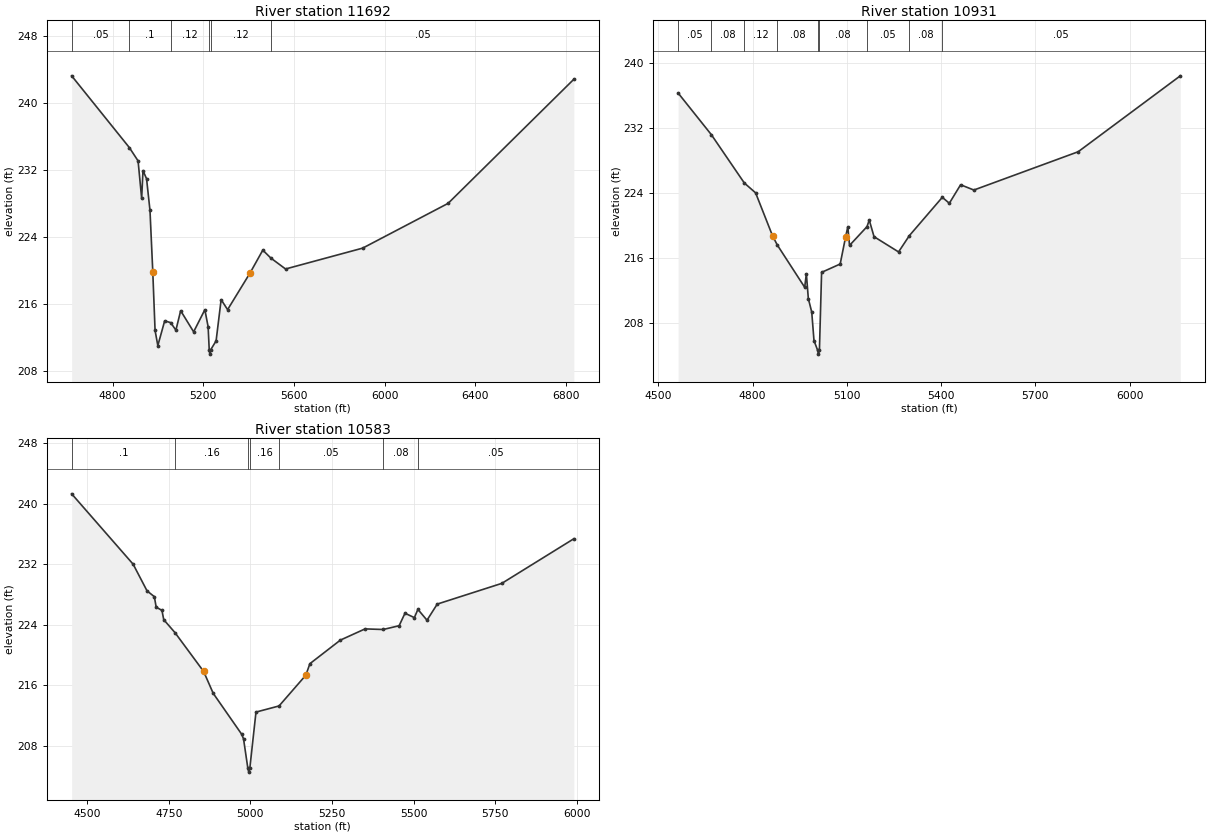
Type RM Length L Ch R = 1 ,11692   ,761,761,761
BEGIN DESCRIPTION:
SALT CREEK 12.0
END DESCRIPTION:
XS GIS Cut Line= 3
      2274537.73     13385146.84      2274337.72     13385496.85
      2273187.72     13386896.86
#Sta/Elev= 30
  4619.7  243.23  4874.1  234.67  4912.7  233.08  4928.5   228.6  4934.3  231.92
  4950.1  230.95  4965.2  227.17  4977.5  219.86  4987.6  212.85  4999.8  211.04
    5030  213.99  5056.3  213.78  5079.5  212.88  5100.5   215.2  5157.7  212.68
  5207.2  215.32  5221.6  213.29  5226.5  210.52  5229.2  210.02  5232.5  210.52
  5256.8   211.6    5279  216.52  5307.5  215.33  5406.7  219.71  5462.8  222.43
    5498  221.49  5563.1  220.18  5903.3  222.67    6280  228.01  6834.6  242.82
#Mann= 6 ,-1 , 0
  4619.7     .05       0  4874.1      .1       0  5056.3     .12       0
  5226.5     .07       0  5232.5     .12       0    5498     .05       0
Bank Sta=4977.5,5406.7
XS Rating Curve= 0 ,0
Exp/Cntr=0.3,0.1

Type RM Length L Ch R = 1 ,10931   ,348,348,348
BEGIN DESCRIPTION:
SALT CREEK 11.0
END DESCRIPTION:
XS GIS Cut Line= 3
      2273854.01     13385161.98      2273432.49     13386215.76
      2273101.55     13386540.34
#Sta/Elev= 30
  4563.1  236.36  4668.8  231.23  4773.8  225.27  4809.8  224.05  4863.6  218.76
  4878.7  217.63    4966  212.41  4971.3  214.08  4977.6  211.01  4988.4  209.36
  4995.6  205.84  5006.9  204.67  5009.7  204.17  5012.9  204.67  5019.8  214.25
    5079  215.28  5096.1   218.6  5103.3  219.87  5108.7  217.57  5164.4  219.89
  5171.5   220.7  5186.7  218.65  5264.8  216.77    5299  218.77    5404   223.5
  5426.4  222.77  5462.3  225.05  5504.5   224.4  5836.5  229.12  6161.6  238.48
#Mann= 9 ,-1 , 0
  4563.1     .05       0  4668.8     .08       0  4773.8     .12       0
  4878.7     .08       0  5006.9     .07       0  5012.9     .08       0
  5164.4     .05       0    5299     .08       0    5404     .05       0
Bank Sta=4863.6,5096.1
XS Rating Curve= 0 ,0
Exp/Cntr=0.3,0.1

Type RM Length L Ch R = 1 ,10583   ,570,570,570
BEGIN DESCRIPTION:
SALT CREEK 10.0
END DESCRIPTION:
XS GIS Cut Line= 3
      2273649.64     13385002.34      2273489.97     13385174.78
       2272966.3       13386369.
#Sta/Elev= 30
  4452.1  241.29  4640.6  231.98  4683.1  228.46  4705.5  227.69  4711.2   226.3
  4728.8  225.88  4734.3  224.65  4768.7  222.94  4856.6   217.8  4885.9  214.91
  4973.3  209.49  4978.9  208.88  4992.1  204.99  4994.9  204.49  4998.1  204.99
    5017  212.43  5087.7  213.24  5169.8  217.31  5182.2  218.83  5275.7  221.95
  5351.3  223.43  5406.8  223.35  5455.7  223.85  5473.6   225.5  5502.4  224.92
  5513.2  226.01  5541.1  224.58  5572.5  226.71  5770.4  229.45  5991.1  235.35
#Mann= 7 ,-1 , 0
  4452.1      .1       0  4768.7     .16       0  4992.1     .07       0
  4998.1     .16       0  5087.7     .05       0  5406.8     .08       0
  5513.2     .05       0
Bank Sta=4856.6,5169.8
XS Rating Curve= 0 ,0
Exp/Cntr=0.3,0.1