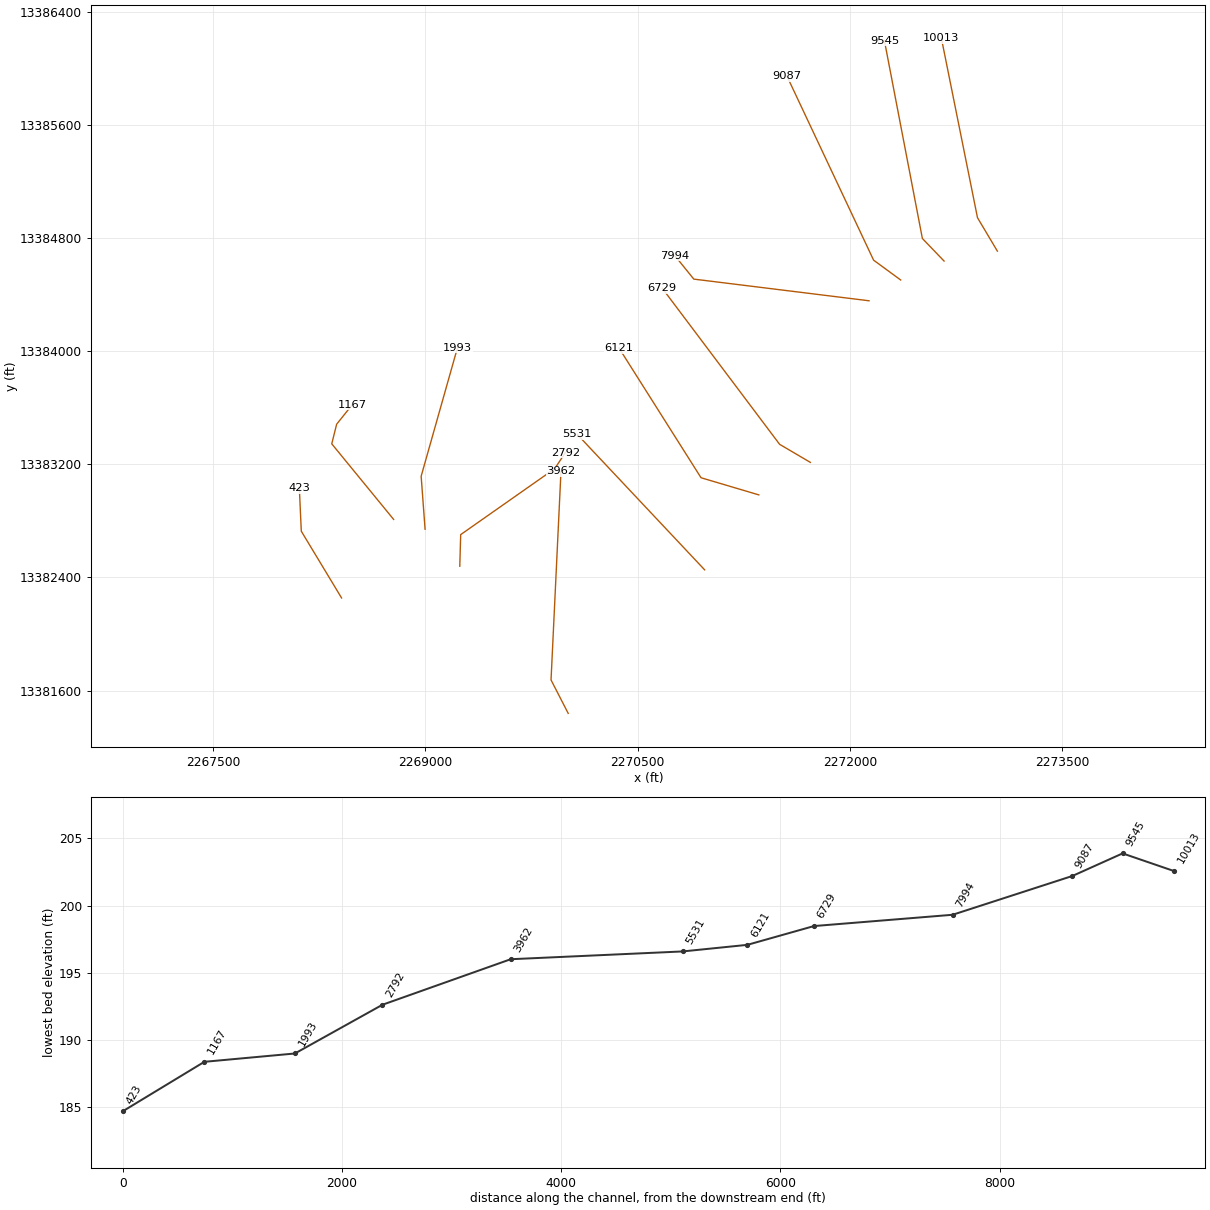
HEC-RAS study SALT CREEK.prj: SALT CREEK Base Level Engineering

--- SALT CREEK.g01 (geometry) --- (continued)

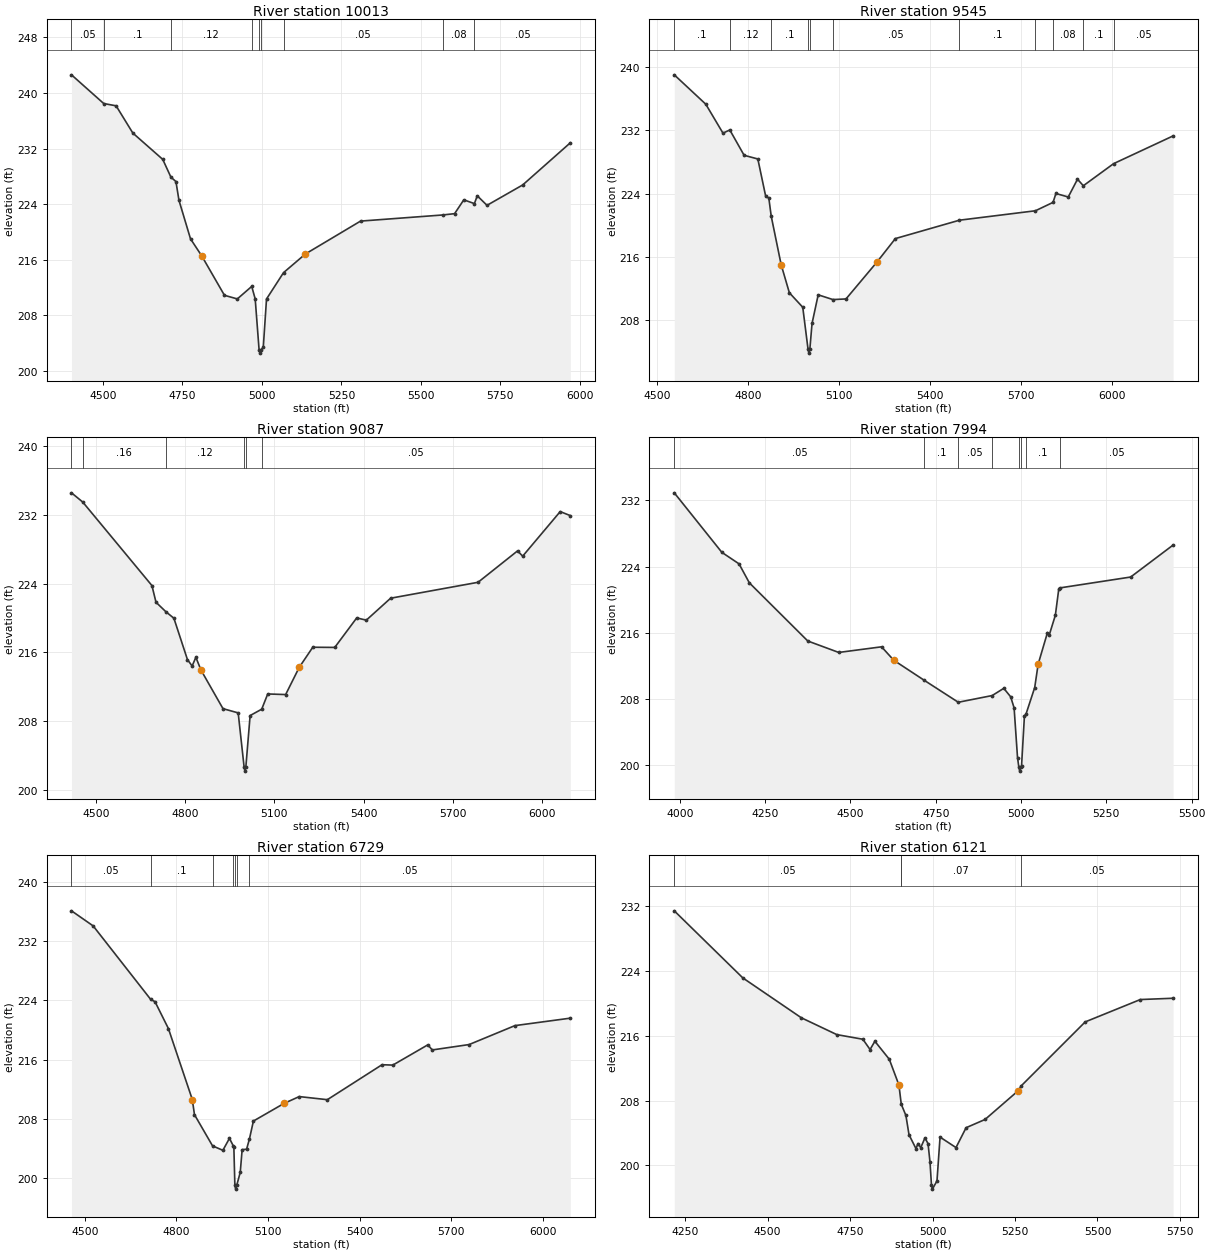
Type RM Length L Ch R = 1 ,10013   ,468,468,468
BEGIN DESCRIPTION:
SALT CREEK 9.0
END DESCRIPTION:
XS GIS Cut Line= 3
      2273042.92     13384708.57      2272902.42     13384944.87
      2272647.37     13386213.77
#Sta/Elev= 30
  4400.9  242.62  4502.3  238.49  4541.3  238.16  4593.9  234.24    4688  230.45
  4713.6   227.9  4729.5  227.26    4739  224.56  4775.3  219.02  4810.4  216.58
  4882.1  210.89  4922.6  210.37  4967.9  212.17  4978.8  210.37    4991  203.07
  4993.8  202.57    4997  203.07  5004.2  203.38  5014.4  210.36  5067.9  214.15
  5136.8  216.84  5310.2  221.57  5568.2  222.45    5606  222.64    5635  224.63
  5668.3  224.09  5677.4  225.21    5708  223.84  5820.2  226.77  5970.1  232.84
#Mann= 9 ,-1 , 0
  4400.9     .05       0  4502.3      .1       0  4713.6     .12       0
  4967.9      .1       0    4991     .07       0    4997      .1       0
  5067.9     .05       0  5568.2     .08       0  5668.3     .05       0
Bank Sta=4810.4,5136.8
XS Rating Curve= 0 ,0
Exp/Cntr=0.3,0.1

Type RM Length L Ch R = 1 ,9545    ,458,458,458
BEGIN DESCRIPTION:
SALT CREEK 8.0
END DESCRIPTION:
XS GIS Cut Line= 3
      2272666.12     13384638.33      2272512.85     13384797.98
      2272244.63     13386196.58
#Sta/Elev= 30
  4555.6  239.01  4659.6   235.3  4716.2  231.65  4738.8  232.05    4786  228.85
  4831.2  228.39  4857.2  223.67  4867.4  223.47  4875.4  221.16  4908.1  215.05
  4935.2   211.5  4979.4  209.67  4996.8  204.38  4999.5  203.88  5002.8  204.38
    5010  207.62  5030.3  211.24  5078.9  210.64    5122  210.72  5223.8  215.36
  5284.9  218.34  5496.3  220.66  5746.8  221.85    5805  222.91  5814.4  224.03
  5855.1  223.59  5885.6  225.83  5904.9  225.01  6004.8   227.8    6201   231.3
#Mann= 11 ,-1 , 0
  4555.6      .1       0  4738.8     .12       0  4875.4      .1       0
  4996.8     .07       0  5002.8      .1       0  5078.9     .05       0
  5496.3      .1       0  5746.8     .05       0    5805     .08       0
  5904.9      .1       0  6004.8     .05       0
Bank Sta=4908.1,5223.8
XS Rating Curve= 0 ,0
Exp/Cntr=0.3,0.1

Type RM Length L Ch R = 1 ,9087    ,1093,1093,1093
BEGIN DESCRIPTION:
SALT CREEK 7.0
END DESCRIPTION:
XS GIS Cut Line= 3
      2272359.57     13384504.21      2272167.99     13384644.71
      2271554.87     13385947.58
#Sta/Elev= 30
  4417.8  234.55  4455.6  233.48  4688.3  223.77    4702  221.83  4734.9  220.74
  4762.2  219.97  4807.8  215.16  4823.5  214.42  4836.1  215.43  4853.4  213.94
  4927.3  209.46  4978.4  208.97  4998.2   202.7    5001   202.2  5004.2   202.7
  5018.5  208.66  5057.5   209.4  5077.7  211.17    5138   211.1  5183.6  214.26
  5229.2   216.6  5303.1  216.58    5377  220.01  5409.3  219.75    5491   222.3
    5785  224.15  5917.8   227.8  5935.1  227.19  6061.3  232.37  6095.3   231.9
#Mann= 6 ,-1 , 0
  4417.8      .1       0  4455.6     .16       0  4734.9     .12       0
  4998.2     .07       0  5004.2     .12       0  5057.5     .05       0
Bank Sta=4853.4,5183.6
XS Rating Curve= 0 ,0
Exp/Cntr=0.3,0.1

Type RM Length L Ch R = 1 ,7994    ,1265,1265,1265
BEGIN DESCRIPTION:
SALT CREEK 6.0
END DESCRIPTION:
XS GIS Cut Line= 3
      2272136.06     13384357.32      2270897.09     13384510.59
      2270762.95     13384676.67
#Sta/Elev= 30
  3983.8  232.89  4123.2  225.71  4173.6  224.32  4203.8  222.03  4375.1  215.01
  4465.8  213.63  4591.3  214.31    4627  212.69  4716.7  210.26  4816.1  207.62
  4915.5  208.43  4949.4   209.3  4969.6  208.28  4979.7  206.94  4989.7  200.95
  4993.5  199.81  4996.2  199.31  4999.5  199.81  5001.5  199.92  5009.9  205.92
  5014.8  206.22  5040.1   209.4  5050.2  212.22  5077.5  216.03  5082.5  215.71
  5100.6  218.12  5110.7  221.32  5114.2  221.42  5321.3  222.73  5445.7  226.59
#Mann= 8 ,-1 , 0
  3983.8     .05       0  4716.7      .1       0  4816.1     .05       0
  4915.5     .12       0  4993.5     .07       0  4999.5     .12       0
  5014.8      .1       0  5114.2     .05       0
Bank Sta=4627,5050.2
XS Rating Curve= 0 ,0
Exp/Cntr=0.3,0.1

Type RM Length L Ch R = 1 ,6729    ,608,608,608
BEGIN DESCRIPTION:
SALT CREEK 5.0
END DESCRIPTION:
XS GIS Cut Line= 3
      2271720.98     13383214.13       2271503.8     13383341.88
      2270673.56     13384446.74
#Sta/Elev= 30
  4456.2  236.12  4527.2  234.08  4715.6  224.14  4729.9  223.82  4773.6   220.2
    4852  210.59    4859  208.55  4918.3  204.32  4952.1  203.72  4973.6  205.34
  4986.5   204.3  4988.1  204.13  4991.4  198.97  4994.1  198.47  4997.4  198.97
    5009  200.74  5015.2  203.81  5029.8  203.87  5039.1  205.26  5052.1  207.68
  5152.2  210.06  5202.2  210.99  5294.3  210.57  5473.4   215.3  5508.8  215.25
  5623.4  217.99    5638   217.3  5758.8  218.03  5908.7  220.59  6090.2   221.6
#Mann= 7 ,-1 , 0
  4456.2     .05       0  4715.6      .1       0  4918.3     .12       0
  4986.5      .1       0  4991.4     .07       0  4997.4      .1       0
  5039.1     .05       0
Bank Sta=4852,5152.2
XS Rating Curve= 0 ,0
Exp/Cntr=0.3,0.1

Type RM Length L Ch R = 1 ,6121    ,590,590,590
BEGIN DESCRIPTION:
SALT CREEK 4.0
END DESCRIPTION:
XS GIS Cut Line= 3
       2271356.9     13382984.24      2270948.18     13383105.58
       2270368.1     13384023.51
#Sta/Elev= 30
  4217.2  231.42    4425  223.14  4602.3  218.22    4710  216.14  4788.9  215.57
  4810.7   214.3  4825.3  215.32    4869   213.1  4898.2  209.92  4905.3  207.55
  4919.4  206.16  4928.8  203.78    4950  202.06  4955.9   202.7  4964.4  202.19
  4977.1   203.4  4986.5  202.68  4992.4  200.41  4996.9  197.57  4999.7  197.07
  5013.6  198.09  5022.9  203.49  5071.2   202.2  5101.8  204.65  5159.4  205.67
  5260.2  209.23  5268.8  209.81  5462.9  217.71    5630  220.47  5729.4  220.63
#Mann= 4 ,-1 , 0
  4217.2     .05       0  4905.3     .12       0  4905.3     .07       0
  5268.8     .05       0
Bank Sta=4898.2,5260.2
XS Rating Curve= 0 ,0
Exp/Cntr=0.3,0.1

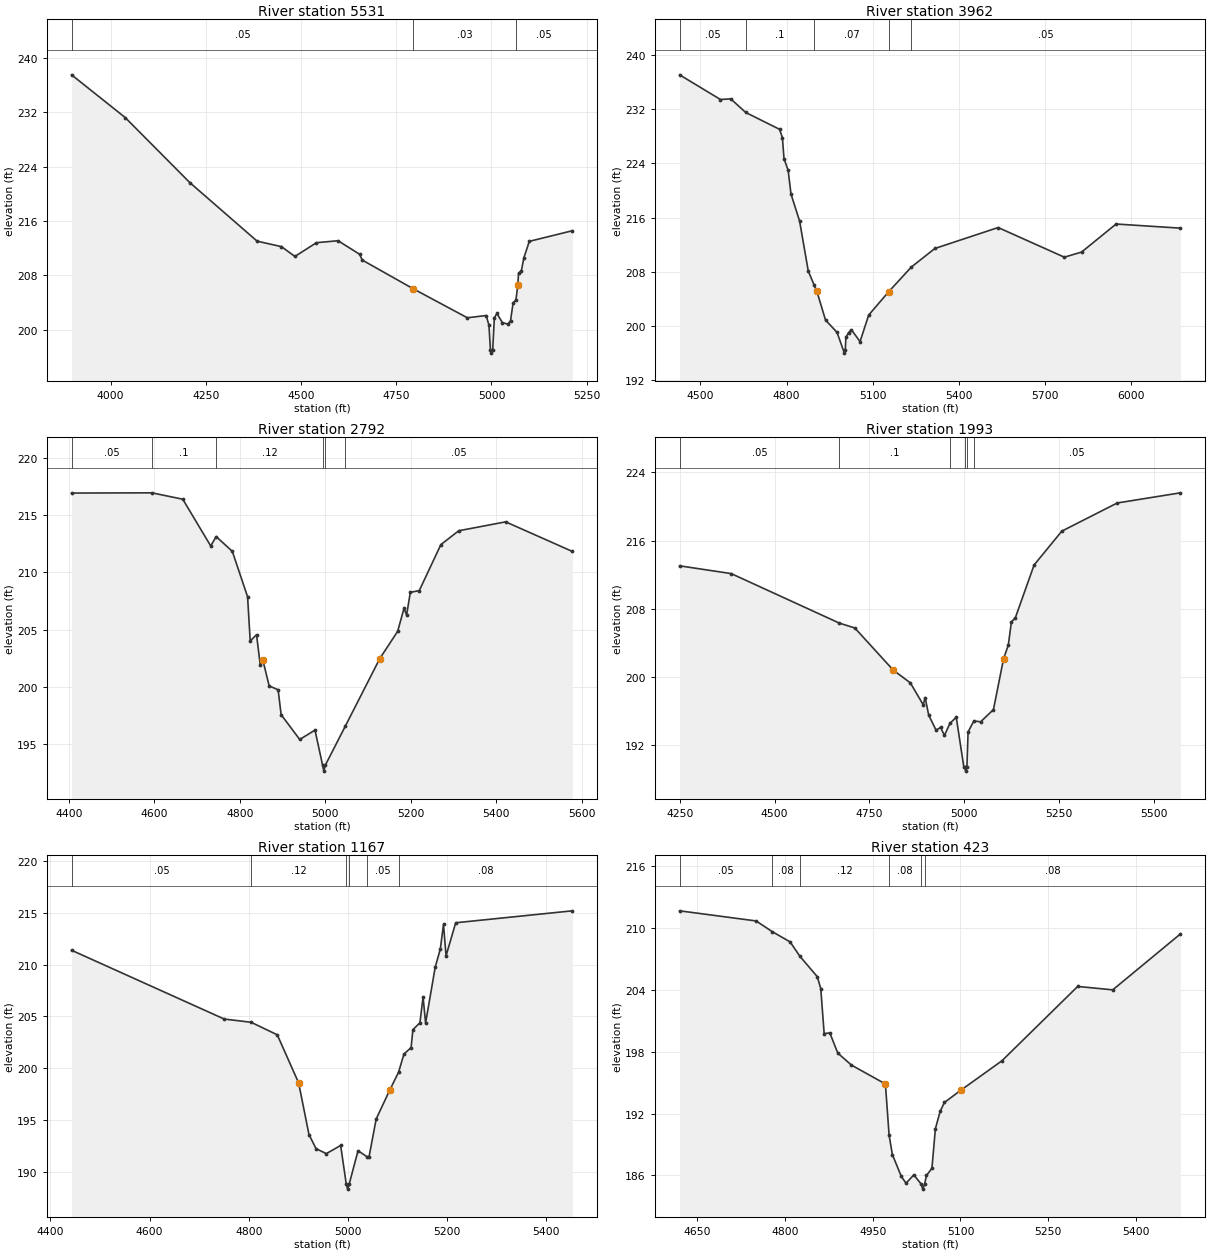
Type RM Length L Ch R = 1 ,5531    ,1569,1569,1569
BEGIN DESCRIPTION:
SALT CREEK 3.0
END DESCRIPTION:
XS GIS Cut Line= 2
      2270973.69      13382454.2      2270073.38     13383411.98
#Sta/Elev= 30
  3897.8  237.51  4038.5  231.23    4208  221.67  4384.8  213.05  4448.8  212.24
    4484   210.8  4540.6  212.82  4597.3  213.11  4653.9  211.12  4660.8  210.27
  4795.1  206.03  4936.7  201.78  4986.1  202.11  4993.4   200.7  4997.3  197.08
    5000  196.58  5003.3  197.08  5007.6  201.79  5014.4  202.41  5028.6  201.07
  5042.7  200.85    5050  201.33  5056.9  203.98  5064.2   204.4 5069.13  206.55
  5071.1  208.33  5078.4  208.67  5085.2  210.62  5099.4  213.02  5212.3  214.58
#Mann= 3 ,-1 , 0
  3897.8     .05       0  4795.1     .03       0  5064.2     .05       0
Bank Sta=4795.1,5069.13
XS Rating Curve= 0 ,0
Exp/Cntr=0.3,0.1

Type RM Length L Ch R = 1 ,3962    ,1170,1170,1170
BEGIN DESCRIPTION:
Mapping XS 67d42a6b
END DESCRIPTION:
XS GIS Cut Line= 3
      2270009.38     13381438.72      2269888.04     13381675.03
      2269958.29     13383150.31
#Sta/Elev= 30
  4427.6  237.04  4569.8   233.4  4605.4   233.5  4657.5  231.49  4775.2  229.01
  4785.2  227.79  4790.9  224.66  4805.2  222.96  4815.2  219.45  4845.2  215.46
  4875.3   208.1  4895.3  206.08  4905.3   205.1  4935.3  200.88  4975.4  199.06
  5000.9     196  5004.2   196.5  5006.2  198.32  5015.4  199.02  5025.4  199.45
  5055.5   197.7  5085.5  201.61  5155.6  205.08  5233.9  208.69  5315.8  211.43
    5536  214.52  5766.3  210.15  5826.4   210.9  5946.5  215.04  6170.2  214.43
#Mann= 5 ,-1 , 0
  4427.6     .05       0  4657.5      .1       0  4895.3     .07       0
  5155.6      .1       0  5233.9     .05       0
Bank Sta=4905.3,5155.6
XS Rating Curve= 0 ,0
Exp/Cntr=0.3,0.1

Type RM Length L Ch R = 1 ,2792    ,799,799,799
BEGIN DESCRIPTION:
Mapping XS 2efd2277
END DESCRIPTION:
XS GIS Cut Line= 4
      2269243.01     13382479.67       2269249.4     13382703.24
      2269913.58     13383169.45      2269989.39     13383283.16
#Sta/Elev= 30
  4406.6  216.95  4594.6  216.97  4666.8  216.41  4732.2  212.32    4745  213.14
  4782.7  211.85  4818.5  207.87  4824.6     204  4839.4  204.55  4848.1  201.91
  4854.2  202.33    4869  200.07  4889.9  199.73    4897  197.55  4940.5  195.38
  4976.2   196.2  4994.1  193.11  4996.9  192.61  5000.1  193.11  5047.2  196.55
  5127.8  202.46  5169.7  204.85  5184.5  206.86  5190.6  206.28  5199.3  208.26
  5220.2  208.41  5270.8  212.44  5312.6  213.65  5422.4  214.43  5578.4  211.84
#Mann= 6 ,-1 , 0
  4406.6     .05       0  4594.6      .1       0    4745     .12       0
  4994.1     .07       0  5000.1     .12       0  5047.2     .05       0
Bank Sta=4854.2,5127.8
XS Rating Curve= 0 ,0
Exp/Cntr=0.3,0.1

Type RM Length L Ch R = 1 ,1993    ,826,826,826
BEGIN DESCRIPTION:
SALT CREEK 2.0
END DESCRIPTION:
XS GIS Cut Line= 3
      2268997.73     13382741.18      2268969.95     13383116.22
       2269226.9     13384025.96
#Sta/Elev= 30
  4249.5  213.05  4385.6  212.14  4670.2  206.35  4711.9  205.76  4813.3  200.82
  4858.3  199.33  4892.3  196.76  4897.4   197.6  4906.8  195.54  4926.2  193.78
    4938   194.1  4948.4  193.17  4962.9  194.59  4979.5  195.29  4999.4  189.49
  5001.6  189.48  5004.3  188.98  5007.6  189.48  5010.7  193.57  5025.9  194.87
  5043.8  194.76  5077.7   196.2  5104.2  202.13  5116.9  203.77    5125  206.47
  5135.4  206.96  5184.9  213.15  5258.1  217.12  5404.4  220.42  5570.9  221.61
#Mann= 6 ,-1 , 0
  4249.5     .05       0  4670.2      .1       0  4962.9     .12       0
  5001.6     .07       0  5007.6     .12       0  5025.9     .05       0
Bank Sta=4813.3,5104.2
XS Rating Curve= 0 ,0
Exp/Cntr=0.3,0.1

Type RM Length L Ch R = 1 ,1167    ,744,744,744
BEGIN DESCRIPTION:
Mapping XS 385ccf6e
END DESCRIPTION:
XS GIS Cut Line= 4
       2268775.5     13382810.67      2268338.01     13383345.39
      2268372.73     13383484.28      2268482.77     13383621.83
#Sta/Elev= 30
  4442.7  211.38  4750.7  204.75  4804.9  204.44  4857.7  203.23  4900.8  198.59
  4921.6  193.62  4935.9  192.26  4956.7  191.78  4985.5  192.57  4996.8  188.86
  4999.6  188.36  5002.8  188.86  5020.6  192.06  5039.1  191.47  5042.9   191.5
  5057.2  195.12  5084.5   197.9  5102.3  199.62  5113.2  201.37  5127.6     202
  5131.3  203.73  5145.4  204.39  5151.8  206.86  5156.9  204.37  5176.3  209.75
  5186.6   211.5    5193  213.88  5198.2  210.85  5217.6  214.03  5452.9  215.18
#Mann= 6 ,-1 , 0
  4442.7     .05       0  4804.9     .12       0  4996.8     .07       0
  5002.8     .12       0  5039.1     .05       0  5102.3     .08       0
Bank Sta=4900.8,5084.5
XS Rating Curve= 0 ,0
Exp/Cntr=0.3,0.1

Type RM Length L Ch R = 1 ,423     ,0,0,0
BEGIN DESCRIPTION:
SALT CREEK 1.0
END DESCRIPTION:
XS GIS Cut Line= 3
      2268407.45      13382255.1      2268122.73     13382727.33
      2268108.86     13383032.39
#Sta/Elev= 30
  4619.5  211.62  4750.4  210.64  4777.8  209.61  4808.6  208.61  4825.3  207.22
  4855.1  205.24    4861  204.09  4866.8  199.74  4876.5   199.8  4890.1  197.85
  4913.4  196.69  4971.6  194.86  4977.9  189.91  4983.5  188.03  4998.8  185.91
  5006.9  185.25  5020.2  186.06  5032.7  185.18  5035.5  184.68  5038.7  185.18
  5041.9     186  5051.2   186.7  5057.1  190.52  5065.3  192.21  5072.6  193.07
  5100.3  194.24  5170.9   197.1  5300.6   204.3  5360.6  203.97  5476.3  209.38
#Mann= 6 ,-1 , 0
  4619.5     .05       0  4777.8     .08       0  4825.3     .12       0
  4977.9     .08       0  5032.7     .07       0  5038.7     .08       0
Bank Sta=4971.6,5100.3
XS Rating Curve= 0 ,0
Exp/Cntr=0.3,0.1

Chan Stop Cuts=-1
Use User Specified Reach Order=0
Composite Channel Slope=5