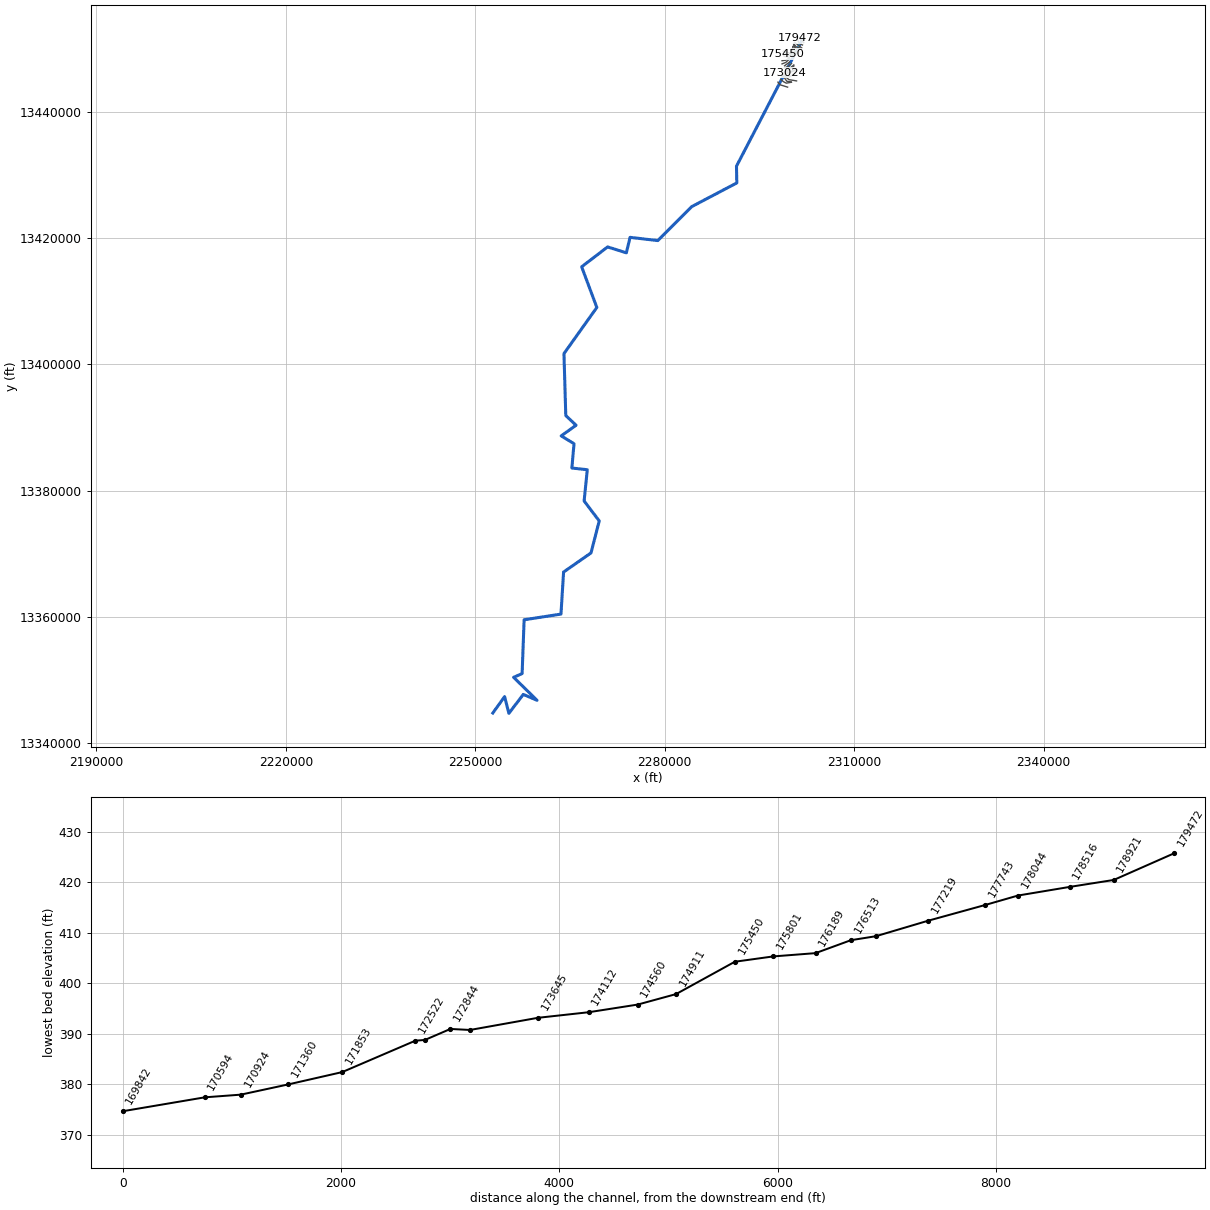
--- SULPHUR CREEK.prj (project) ---

Proj Title=SULPHUR CREEK Base Level Engineering
Current Plan=p01
Default Exp/Contr=0.3,0.1
English Units
Geom File=g01
Flow File=f01
Plan File=p01
Y Axis Title=Elevation
X Axis Title(PF)=Main Channel Distance
X Axis Title(XS)=Station
BEGIN DESCRIPTION:
SULPHUR CREEK
END DESCRIPTION:
DSS Export Rating Curves= 0
DSS Export Rating Curve Sorted= 0
DSS Export Volume Flow Curves= 0
DXF OffsetX= 0
DXF OffsetY= 0
DXF ScaleX= 1
DXF ScaleY= 10

--- SULPHUR CREEK.p01 (plan) ---

Plan Title=Multiple Run
Short Identifier=Multiple
Geom File=g01
Flow File=f01
Subcritical Flow
K Sum by GR= 0
Std Step Tol= 0.01
Critical Tol= 0.01
Num of Std Step Trials= 20
Max Error Tol= 0.3
Flow Tol Ratio= 0.001
Split Flow NTrial= 30
Split Flow Tol= 0.02
Split Flow Ratio= 0.02
Log Output Level= 0
Friction Slope Method= 1
Unsteady Friction Slope Method= 2
Unsteady Bridges Friction Slope Method= 1
Parabolic Critical Depth
Global Vel Dist=  1 , 1 , 1
Global Log Level= 0
CheckData=True
Encroach Param= -1, 0, 0, 0
BEGIN DESCRIPTION:
Multiple Run
END DESCRIPTION:

--- SULPHUR CREEK.f01 (steady flow) ---

Flow Title=Multiple
Program Version=4.10
Number of Profiles= 7
Profile Names=10-year,25-year,50-year,1pct_min,100-year,1pct_plu,500-year
River Rch & RM=SULPHUR CREEK,Reach-1         ,179472
     701    1000    1255    1150    1556    2104    2400
River Rch & RM=SULPHUR CREEK,Reach-1         ,178516
     746    1066    1338    1226    1659    2243    2558
River Rch & RM=SULPHUR CREEK,Reach-1         ,176189
    1125    1644    2093    1944    2629    3555    4164
River Rch & RM=SULPHUR CREEK,Reach-1         ,172611
    1188    1739    2218    2062    2789    3772    4428
River Rch & RM=SULPHUR CREEK,Reach-1         ,171360
    1438    2125    2726    2549    3447    4662    5535
River Rch & RM=SULPHUR CREEK,Reach-1         ,169842
    1918    2872    3717    3503    4737    6406    7728
River Rch & RM=SULPHUR CREEK,Reach-1         ,168184
    2091    3139    4071    3842    5195    7026    8501
River Rch & RM=SULPHUR CREEK,Reach-1         ,167199
    2292    3450    4482    4235    5727    7745    9396
River Rch & RM=SULPHUR CREEK,Reach-1         ,164448
    2412    3629    4713    4451    6019    8140    9864
River Rch & RM=SULPHUR CREEK,Reach-1         ,160808
    2823    4274    5573    5282    7143    9661   11791
River Rch & RM=SULPHUR CREEK,Reach-1         ,159097
    3797    5801    7612    7253    9809   13265   16369
River Rch & RM=SULPHUR CREEK,Reach-1         ,158615
    3797    5801    7612    7253    9809   13265   16369
River Rch & RM=SULPHUR CREEK,Reach-1         ,156197
    3878    5927    7778    7414   10026   13560   16748
River Rch & RM=SULPHUR CREEK,Reach-1         ,155648
    3983    6090    7995    7623   10309   13941   17225
River Rch & RM=SULPHUR CREEK,Reach-1         ,151905
    3941    6014    7883    7504   10148   13725   16905
River Rch & RM=SULPHUR CREEK,Reach-1         ,149926
    4215    6444    8458    8061   10902   14743   18201
River Rch & RM=SULPHUR CREEK,Reach-1         ,146954
    4762    7309    9619    9189   12427   16806   20844
River Rch & RM=SULPHUR CREEK,Reach-1         ,144412
    4830    7415    9760    9325   12612   17056   21163
River Rch & RM=SULPHUR CREEK,Reach-1         ,143359
    4676    7161    9410    8980   12144   16423   20334
River Rch & RM=SULPHUR CREEK,Reach-1         ,140783
    4600    7036    9240    8813   11918   16118   19942
River Rch & RM=SULPHUR CREEK,Reach-1         ,139673
    4534    6929    9096    8673   11729   15863   19625
River Rch & RM=SULPHUR CREEK,Reach-1         ,135961
    4405    6715    8800    8378   11330   15323   18903
River Rch & RM=SULPHUR CREEK,Reach-1         ,133218
    4321    6576    8608    8186   11071   14972   18438
River Rch & RM=SULPHUR CREEK,Reach-1         ,131759
    4195    6366    8318    7897   10680   14443   17728
River Rch & RM=SULPHUR CREEK,Reach-1         ,120812
    4071    6163    8039    7622   10308   13940   17072
River Rch & RM=SULPHUR CREEK,Reach-1         ,112685
    4389    6659    8706    8288   11208   15158   18756
River Rch & RM=SULPHUR CREEK,Reach-1         ,106085
    4314    6530    8525    8103   10958   14820   18285
River Rch & RM=SULPHUR CREEK,Reach-1         ,101930
    4340    6570    8578    8154   11028   14914   18406
River Rch & RM=SULPHUR CREEK,Reach-1         ,100421
    4353    6584    8591    8164   11041   14931   18421
River Rch & RM=SULPHUR CREEK,Reach-1         ,94537
    4338    6554    8547    8118   10979   14847   18300
River Rch & RM=SULPHUR CREEK,Reach-1         ,90368
    4373    6610    8624    8194   11082   14987   18489
River Rch & RM=SULPHUR CREEK,Reach-1         ,88133
    4320    6523    8501    8070   10914   14760   18173
River Rch & RM=SULPHUR CREEK,Reach-1         ,85805
    4330    6538    8522    8091   10942   14798   18226
River Rch & RM=SULPHUR CREEK,Reach-1         ,83565
    4275    6446    8394    7961   10766   14560   17895
River Rch & RM=SULPHUR CREEK,Reach-1         ,78803
    4264    6419    8351    7913   10701   14472   17758
River Rch & RM=SULPHUR CREEK,Reach-1         ,69870
    4346    6546    8519    8076   10922   14771   18147
River Rch & RM=SULPHUR CREEK,Reach-1         ,67230
    5857    8885   11621   11064   14963   20236   25056
River Rch & RM=SULPHUR CREEK,Reach-1         ,62086
    5942    9008   11778   11212   15163   20507   25389
River Rch & RM=SULPHUR CREEK,Reach-1         ,60167
    6035    9155   11977   11409   15430   20867   25871
River Rch & RM=SULPHUR CREEK,Reach-1         ,57258
    6014    9114   11915   11343   15340   20746   25691
River Rch & RM=SULPHUR CREEK,Reach-1         ,51741
    6020    9120   11921   11346   15345   20752   25690
River Rch & RM=SULPHUR CREEK,Reach-1         ,49872
    5926    8961   11697   11119   15037   20336   25108
River Rch & RM=SULPHUR CREEK,Reach-1         ,48267
    5995    9069   11843   11262   15231   20598   25454
River Rch & RM=SULPHUR CREEK,Reach-1         ,42575
    5998    9074   11848   11265   15235   20604   25457
River Rch & RM=SULPHUR CREEK,Reach-1         ,39258
    5948    8989   11730   11147   15075   20387   25158
River Rch & RM=SULPHUR CREEK,Reach-1         ,36460
    6520    9865   12885   12253   16571   22410   27694
River Rch & RM=SULPHUR CREEK,Reach-1         ,34606
    6630   10037   13116   12480   16878   22826   28242
River Rch & RM=SULPHUR CREEK,Reach-1         ,30564
    6613   10004   13067   12427   16807   22729   28096
River Rch & RM=SULPHUR CREEK,Reach-1         ,25547
    6557    9910   12934   12292   16624   22482   27749
River Rch & RM=SULPHUR CREEK,Reach-1         ,22028
    6549    9894   12910   12266   16589   22435   27677
River Rch & RM=SULPHUR CREEK,Reach-1         ,17424
    6479    9776   12745   12099   16362   22128   27250
River Rch & RM=SULPHUR CREEK,Reach-1         ,13907
    6544    9875   12875   12224   16532   22357   27544
River Rch & RM=SULPHUR CREEK,Reach-1         ,10718
    6467    9746   12695   12042   16285   22024   27081
Boundary for River Rch & Prof#=SULPHUR CREEK,Reach-1         , 1
Up Type= 0
Dn Type= 3
Dn Slope=0.0018
Boundary for River Rch & Prof#=SULPHUR CREEK,Reach-1         , 2
Up Type= 0
Dn Type= 3
Dn Slope=0.0018
Boundary for River Rch & Prof#=SULPHUR CREEK,Reach-1         , 3
Up Type= 0
Dn Type= 3
Dn Slope=0.0018
Boundary for River Rch & Prof#=SULPHUR CREEK,Reach-1         , 4
Up Type= 0
Dn Type= 3
Dn Slope=0.0018
Boundary for River Rch & Prof#=SULPHUR CREEK,Reach-1         , 5
Up Type= 0
Dn Type= 3
Dn Slope=0.0018
Boundary for River Rch & Prof#=SULPHUR CREEK,Reach-1         , 6
Up Type= 0
Dn Type= 3
Dn Slope=0.0018
Boundary for River Rch & Prof#=SULPHUR CREEK,Reach-1         , 7
Up Type= 0
Dn Type= 3
Dn Slope=0.0018
DSS Import GetInterval= 0
DSS Import GetPeak= 0
DSS Import FillOption= 0

--- SULPHUR CREEK.g01 (geometry) ---

Geom Title=Existing Conditions
Program Version=4.10

River Reach=SULPHUR CREEK   ,Reach-1
Reach XY= 30
      2301834.96     13451562.15      2291372.98     13431429.39
      2291424.79     13428773.31      2284291.41     13425019.32
      2278909.96     13419632.82      2274518.96     13420143.95
      2273930.35     13417692.73      2270963.12     13418625.88
      2266850.52     13415475.82      2269257.14     13409032.06
      2264050.05     13401715.89      2264338.58     13391886.99
      2265968.31     13390356.82      2263611.59     13388671.84
      2265642.73     13387428.79       2265302.7     13383574.17
      2267745.36     13383305.44      2267240.71     13378358.09
      2269634.93     13375188.01      2268332.11     13370114.37
      2263990.54     13367085.69      2263576.12     13360417.91
      2257740.23     13359515.83      2257423.32     13350983.92
      2256078.32      13350394.3       2259785.6     13346747.54
      2257605.28     13347682.07      2255328.41     13344677.65
      2254648.78     13347334.19      2252787.56     13344739.34

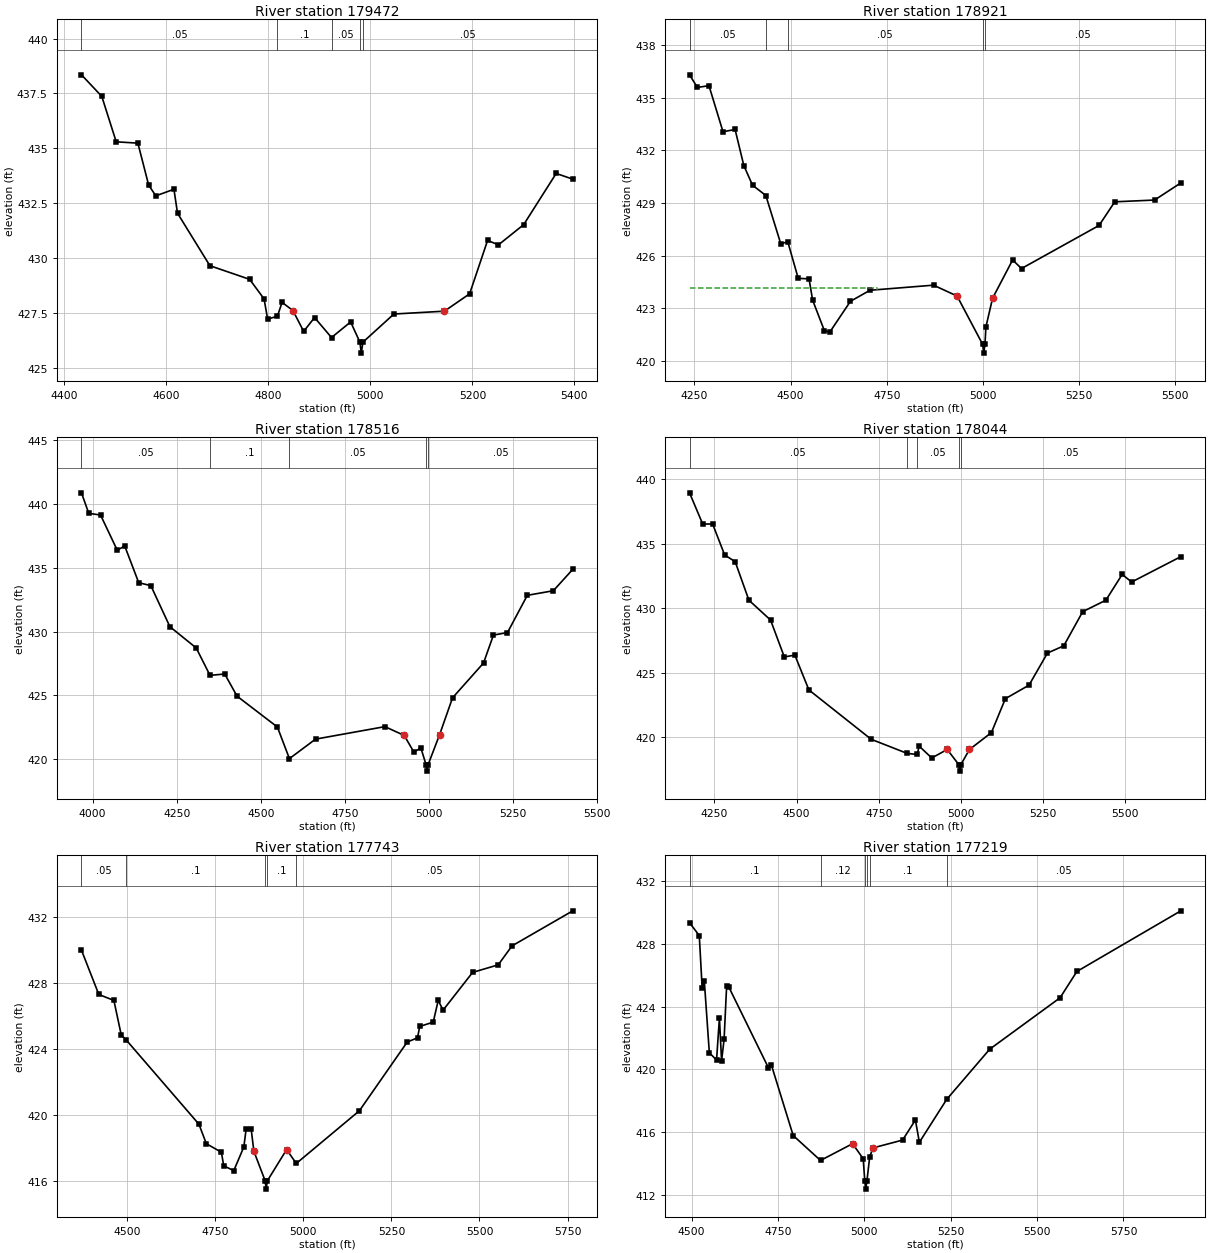
Type RM Length L Ch R = 1 ,179472  ,551,551,551
BEGIN DESCRIPTION:
SULPHUR CREEK 218.0
END DESCRIPTION:
XS GIS Cut Line= 2
      2302024.09       13451007.      2301351.59     13451696.83
#Sta/Elev= 30
  4433.5  438.35  4473.3  437.37  4501.6   435.3  4544.1  435.24  4565.2  433.33
  4579.3  432.84  4614.8  433.14  4621.8  432.05  4685.3  429.66  4763.2  429.04
  4791.5  428.15  4798.5  427.23  4817.7  427.36  4826.8  427.99  4848.1  427.62
  4869.2  426.67  4890.5   427.3  4923.8  426.39  4961.3   427.1  4979.4  426.18
  4982.1  425.68  4985.4  426.18  5046.1  427.46  5145.2  427.59  5194.6  428.38
  5229.8  430.81  5251.2  430.61  5300.6  431.53  5364.3  433.86  5396.9   433.6
#Mann= 5 ,-1 , 0
  4433.5     .05       0  4817.7      .1       0  4923.8     .05       0
  4979.4     .03       0  4985.4     .05       0
Bank Sta=4848.1,5145.2
XS Rating Curve= 0 ,0
Exp/Cntr=0.3,0.1

Type RM Length L Ch R = 1 ,178921  ,405,405,405
BEGIN DESCRIPTION:
SULPHUR CREEK 217.0
END DESCRIPTION:
XS GIS Cut Line= 3
      2301826.11     13450638.98      2301298.37     13450892.44
      2301014.21     13451523.13
#Sta/Elev= 30
  4237.2  436.32  4257.6   435.6  4287.7   435.7  4324.2  433.07  4355.6   433.2
  4378.3  431.14  4400.9  430.02  4435.5  429.43  4474.4  426.67  4492.6  426.79
  4519.7   424.7  4547.9  424.67  4557.1  423.46  4587.6  421.72  4601.5  421.62
  4655.5  423.39  4706.4  424.02  4871.4  424.31  4932.7  423.69  4999.2  420.93
  5001.9  420.43  5005.2  420.93  5007.6  421.92  5024.9  423.56  5077.1  425.75
  5100.2  425.26  5301.8  427.72  5342.6  429.07  5446.1  429.17  5514.4  430.15
#Mann= 5 ,-1 , 0
  4237.2     .05       0  4435.5      .1       0  4492.6     .05       0
  4999.2     .03       0  5005.2     .05       0
#XS Ineff= 2 , 0
          4725.8  424.15
Permanent Ineff=
       T       T
Bank Sta=4932.7,5024.9
XS Rating Curve= 0 ,0
Exp/Cntr=0.3,0.1

Type RM Length L Ch R = 1 ,178516  ,472,472,472
BEGIN DESCRIPTION:
SULPHUR CREEK 216.0
END DESCRIPTION:
XS GIS Cut Line= 3
      2301737.72     13450146.85      2300937.72     13450796.85
      2300587.72     13451046.86
#Sta/Elev= 30
    3967  440.88  3988.6  439.27  4023.7  439.14  4073.3  436.38  4095.6  436.71
  4137.2  433.83  4173.2   433.6  4229.9  430.38  4308.2  428.71  4349.2  426.56
  4392.9  426.67  4429.6  424.93  4549.5  422.51  4585.3  420.03    4663  421.56
  4869.2  422.54  4926.7  421.85  4955.4  420.54  4976.2  420.87  4991.6  419.55
  4994.3  419.05  4997.6  419.55 5031.98  421.92  5070.3   424.8  5162.5  427.53
  5191.9  429.72  5233.7  429.92  5292.7  432.84  5370.1   433.2  5427.9  434.88
#Mann= 5 ,-1 , 0
    3967     .05       0  4349.2      .1       0  4585.3     .05       0
  4991.6     .03       0  4997.6     .05       0
#XS Ineff= 2 , 0
         4807.35  422.24
Permanent Ineff=
       T       T
Bank Sta=4926.7,5031.98
XS Rating Curve= 0 ,0
Exp/Cntr=0.3,0.1

Type RM Length L Ch R = 1 ,178044  ,301,301,301
BEGIN DESCRIPTION:
SULPHUR CREEK 215.0
END DESCRIPTION:
XS GIS Cut Line= 3
      2301637.68     13450046.87      2300837.72     13450346.85
       2300437.7     13450846.88
#Sta/Elev= 30
  4174.4  438.94  4214.4  436.52  4244.7  436.52  4281.2  434.12  4313.2   433.6
    4355  430.61  4420.9  429.07  4462.7  426.21  4494.8  426.35  4537.5  423.65
    4727  419.82  4836.1  418.73    4867  418.64    4873  419.29  4911.3  418.37
  4958.4  419.03  4993.7  417.85  4996.5  417.35  4999.7  417.85  5026.1  419.03
  5092.8  420.34  5135.2  422.97  5207.2  424.02  5263.3  426.51  5312.9  427.07
  5370.5  429.72    5441  430.61  5490.6  432.61  5519.4  432.02  5669.1  433.99
#Mann= 5 ,-1 , 0
  4174.4     .05       0  4836.1      .1       0    4867     .05       0
  4993.7     .03       0  4999.7     .05       0
Bank Sta=4958.4,5026.1
XS Rating Curve= 0 ,0
Exp/Cntr=0.3,0.1

Type RM Length L Ch R = 1 ,177743  ,524,524,524
BEGIN DESCRIPTION:
Mapping XS f12de19e
END DESCRIPTION:
XS GIS Cut Line= 4
      2301232.89     13449562.37       2300869.6     13449987.49
      2300629.97     13450312.15      2300436.74     13450698.62
#Sta/Elev= 30
  4370.2  429.99  4419.4   427.3  4462.2  426.94  4483.1  424.84  4497.9  424.52
  4703.7  419.42  4724.6  418.24  4767.4  417.72    4774   416.9  4802.5   416.6
  4831.1  418.04  4837.7  419.13  4851.9  419.13  4859.6  417.78  4891.7  415.98
  4894.5  415.48  4897.7  415.98  4952.5  417.88  4980.1  417.04  5159.2  420.24
  5294.9  424.41  5324.2  424.67  5330.4  425.36  5368.8  425.62  5382.9  426.94
  5396.8  426.35  5480.6  428.64  5553.3   429.1  5592.4  430.25    5765  432.38
#Mann= 5 ,-1 , 0
  4370.2     .05       0  4497.9      .1       0  4891.7     .03       0
  4897.7      .1       0  4980.1     .05       0
#XS Ineff= 2 , 0
         4839.09  419.03
Permanent Ineff=
       T       T
Bank Sta=4859.6,4952.5
XS Rating Curve= 0 ,0
Exp/Cntr=0.3,0.1

Type RM Length L Ch R = 1 ,177219  ,476,476,476
BEGIN DESCRIPTION:
SULPHUR CREEK 214.0
END DESCRIPTION:
XS GIS Cut Line= 3
      2301037.74     13449296.84      2300637.72     13449596.85
      2300437.72     13450496.87
#Sta/Elev= 30
    4494  429.36  4522.2  428.54  4530.5   425.2  4536.7  425.66  4551.3  421.06
  4572.2   420.6  4580.5  423.29  4586.7  420.54    4594  421.92  4601.3   425.3
  4607.6  425.26  4722.2  420.11  4730.5  420.31    4794  415.78  4873.1  414.19
  4965.9  415.26  4996.6   414.3  5001.3  412.86    5004  412.36  5007.3  412.86
  5015.4  414.41  5024.8  414.99  5110.6  415.49  5147.7  416.77  5159.2  415.35
  5238.4  418.09  5362.8  421.29  5566.4  424.57  5615.1  426.25    5916  430.12
#Mann= 6 ,-1 , 0
    4494      .1       0  4873.1     .12       0  5001.3     .07       0
  5007.3     .12       0  5015.4      .1       0  5238.4     .05       0
Bank Sta=4965.9,5024.8
XS Rating Curve= 0 ,0
Exp/Cntr=0.3,0.1

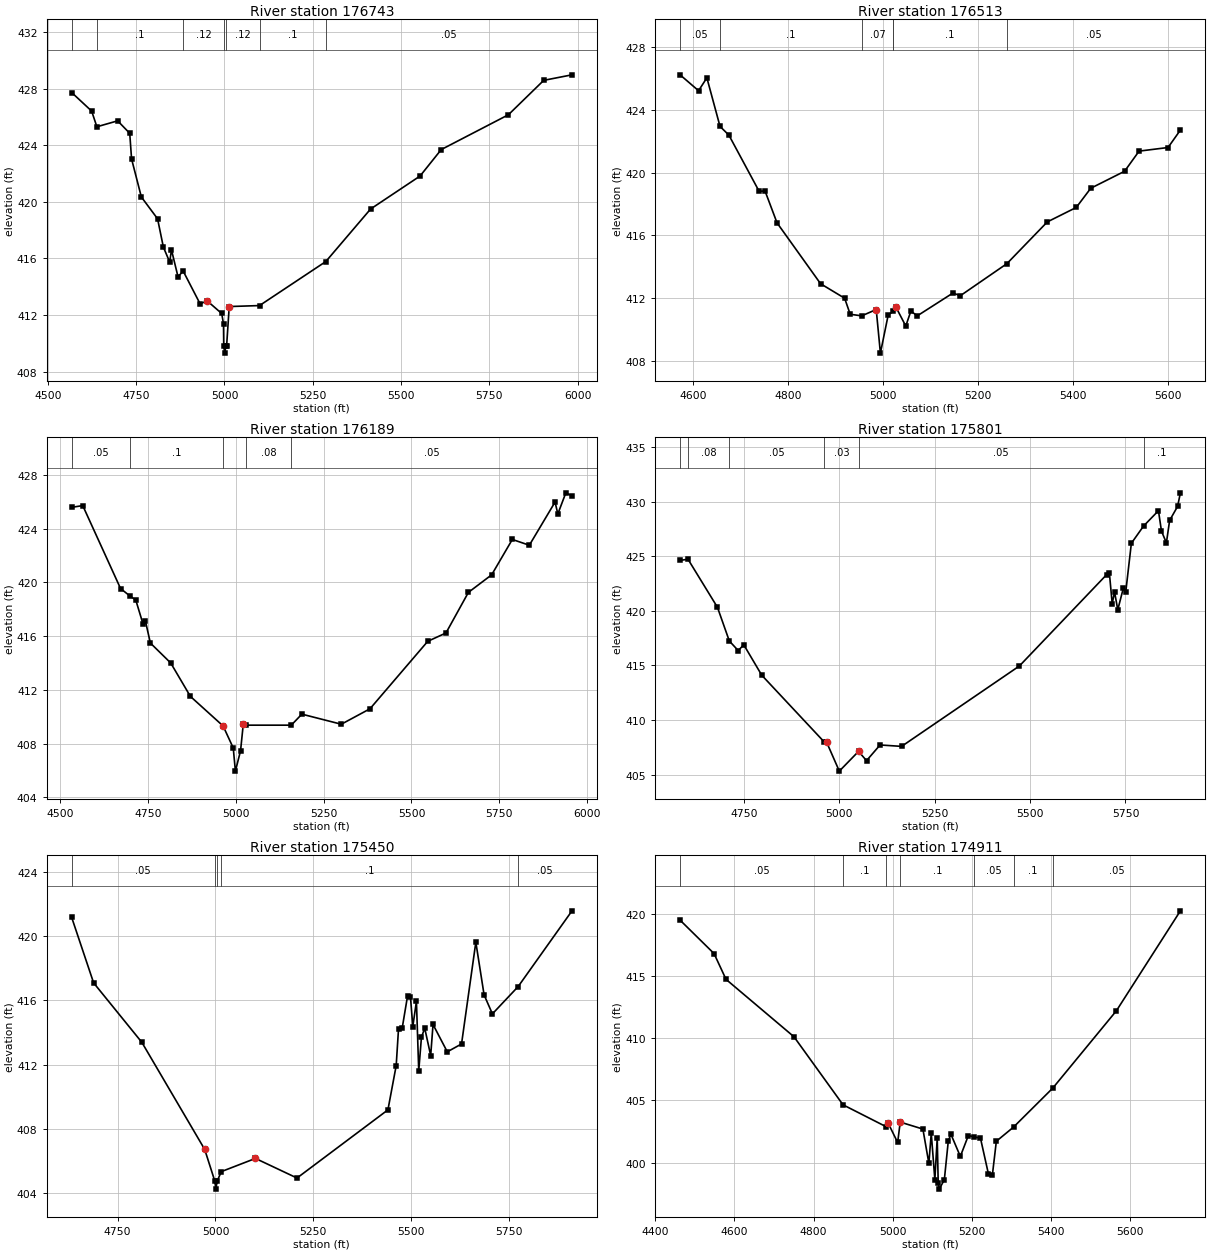
Type RM Length L Ch R = 1 ,176743  ,230,230,230
BEGIN DESCRIPTION:
SULPHUR CREEK 213.0
END DESCRIPTION:
XS GIS Cut Line= 3
      2300387.71     13448996.89      2300270.75       13449417.
      2300287.72     13450396.87
#Sta/Elev= 30
  4567.6  427.72  4624.1  426.41  4638.9   425.3  4697.7  425.72  4731.9  424.84
  4737.1  423.03  4764.8  420.34  4810.7   418.8  4827.1   416.8  4844.9  415.75
  4850.1   416.6  4868.6   414.7  4883.1  415.11  4930.9   412.8  4951.6  412.99
  4992.2  412.11  4997.3  411.38    4998  409.81  5000.8  409.31    5004  409.81
  5006.1  409.81  5013.5   412.6  5099.3  412.67  5286.9  415.78  5413.6  419.49
  5553.6  421.82  5613.6  423.69  5803.7  426.15  5903.7  428.58  5983.7  428.97
#Mann= 7 ,-1 , 0
  4567.6     .05       0  4638.9      .1       0  4883.1     .12       0
    4998     .07       0    5004     .12       0  5099.3      .1       0
  5286.9     .05       0
Bank Sta=4951.6,5013.5
XS Rating Curve= 0 ,0
Exp/Cntr=0.3,0.1

Type RM Length L Ch R = 1 ,176513  ,324,324,324
BEGIN DESCRIPTION:
Mapping XS 4933626d
END DESCRIPTION:
XS GIS Cut Line= 3
      2300212.55     13448990.34      2300027.04      13449500.5
      2300119.69     13450002.38
#Sta/Elev= 30
  4572.8  426.21  4611.7   425.2  4629.2  426.02  4656.9  422.93  4675.5  422.38
  4739.3   418.8  4751.6  418.83  4776.9   416.8  4868.6  412.93  4919.2  412.01
  4930.9  410.99  4955.1  410.89  4985.7  411.29  4994.5  408.52    5011  410.96
  5021.7  411.17  5026.6  411.48  5047.9  410.24  5058.6  411.19  5072.1  410.89
  5147.2  412.34  5162.8  412.17  5260.9  414.21  5345.8  416.86  5406.8  417.78
  5437.3     419  5508.5  420.08    5539  421.36    5600  421.59    5626   422.7
#Mann= 6 ,-1 , 0
  4572.8     .05       0  4656.9      .1       0  4955.1     .07       0
  5021.7     .12       0  5021.7      .1       0  5260.9     .05       0
Bank Sta=4985.7,5026.6
XS Rating Curve= 0 ,0
Exp/Cntr=0.3,0.1

Type RM Length L Ch R = 1 ,176189  ,388,388,388
BEGIN DESCRIPTION:
SULPHUR CREEK 212.0
END DESCRIPTION:
XS GIS Cut Line= 4
      2300058.54     13448942.44      2299699.18     13449400.75
      2299318.97     13449478.87      2298933.52     13449718.48
#Sta/Elev= 30
  4532.6  425.59  4564.1  425.72  4671.7  419.55    4700  418.96    4715   418.7
  4735.8   416.9  4742.2  417.16  4756.7  415.49  4814.5  414.01  4870.6  411.52
  4963.7  409.32  4992.6  407.68  4998.7  405.96  5013.4  407.48  5021.1  409.45
  5027.8  409.38  5157.8  409.38  5187.9   410.2  5300.2  409.45  5381.9   410.6
  5546.3  415.62  5598.2  416.24    5662  419.26  5728.3  420.57  5787.1   423.2
  5835.5  422.77  5908.7  425.98  5916.7   425.1  5939.4  426.67    5957  426.44
#Mann= 5 ,-1 , 0
  4532.6     .05       0    4700      .1       0  4963.7     .05       0
  5027.8     .08       0  5157.8     .05       0
Bank Sta=4963.7,5021.1
XS Rating Curve= 0 ,0
Exp/Cntr=0.3,0.1

Type RM Length L Ch R = 1 ,175801  ,351,351,351
BEGIN DESCRIPTION:
SULPHUR CREEK 211.0
END DESCRIPTION:
XS GIS Cut Line= 3
      2299887.75     13448896.84      2299537.72     13449046.85
       2298787.7     13449596.87
#Sta/Elev= 30
    4583  424.64  4603.7  424.75  4680.9  420.34    4712  417.25  4735.3  416.37
  4749.9   416.9    4797  414.11  4961.1  407.97  4966.9  407.97  5000.2  405.31
  5050.6  407.12  5071.5  406.27    5107  407.71  5163.4  407.58  5472.2  414.96
  5700.5  423.33  5707.9  423.46  5715.2  420.67  5721.4  421.75  5729.8  420.11
  5744.5  422.11  5750.7  421.75  5765.4  426.21  5797.3  427.79  5836.4   429.2
  5844.3  427.33  5857.2  426.25  5865.7  428.31  5886.5  429.59  5893.9  430.84
#Mann= 6 ,-1 , 0
    4583     .05       0  4603.7     .08       0    4712     .05       0
  4961.1     .03       0  5050.6     .05       0  5797.3      .1       0
Bank Sta=4966.9,5050.6
XS Rating Curve= 0 ,0
Exp/Cntr=0.3,0.1

Type RM Length L Ch R = 1 ,175450  ,539,539,539
BEGIN DESCRIPTION:
SULPHUR CREEK 210.0
END DESCRIPTION:
XS GIS Cut Line= 3
      2299733.32     13448719.77      2298937.11     13448820.26
       2298682.5     13449221.47
#Sta/Elev= 30
  4632.8  421.16  4688.8  417.09    4812  413.39  4972.5  406.73  4998.3  404.76
    5001  404.26  5004.3  404.76    5015  405.35  5102.1  406.17  5208.2  404.95
  5440.4  409.19  5461.5  411.94  5467.5  414.24  5476.8  414.27  5490.5  416.27
    5498  416.21  5503.9  414.37  5513.2  415.94  5519.1  411.61    5526  413.71
  5534.4  414.27  5549.6  412.57  5555.6   414.5    5592   412.8  5628.4  413.29
  5664.9  419.62    5686  416.34  5707.2  415.16    5773  416.86  5910.5  421.57
#Mann= 5 ,-1 , 0
  4632.8     .05       0  4998.3     .03       0  5004.3     .05       0
    5015      .1       0    5773     .05       0
Bank Sta=4972.5,5102.1
XS Rating Curve= 0 ,0
Exp/Cntr=0.3,0.1

Type RM Length L Ch R = 1 ,174911  ,351,351,351
BEGIN DESCRIPTION:
SULPHUR CREEK 209.0
END DESCRIPTION:
XS GIS Cut Line= 3
      2299737.74     13448596.87      2299186.29     13448235.83
       2298587.7     13448146.85
#Sta/Elev= 30
  4462.5  419.49  4548.4   416.8  4578.6  414.73  4750.4  410.11  4874.3  404.64
  4982.6  402.89  4988.6  403.15  5012.3  401.61  5018.8  403.25  5076.1  402.69
  5091.2  399.93  5097.2  402.36  5106.3  398.62  5112.3  401.97  5114.8  398.36
  5117.5  397.86  5130.3  398.62  5140.4  401.77  5147.1  402.26  5170.7  400.49
    5191  402.17  5206.3  402.05  5221.5  401.97  5241.5  399.11  5251.6  398.98
  5261.7  401.71  5305.2  402.85  5404.2  405.98    5565   412.2  5726.8  420.24
#Mann= 7 ,-1 , 0
  4462.5     .05       0  4874.3      .1       0  4982.6     .07       0
  5018.8      .1       0  5206.3     .05       0  5305.2      .1       0
  5404.2     .05       0
#XS Ineff= 1 ,-1
 5027.72  5370.3  403.13
Permanent Ineff=
       T
Bank Sta=4988.6,5018.8
XS Rating Curve= 0 ,0
Exp/Cntr=0.3,0.1

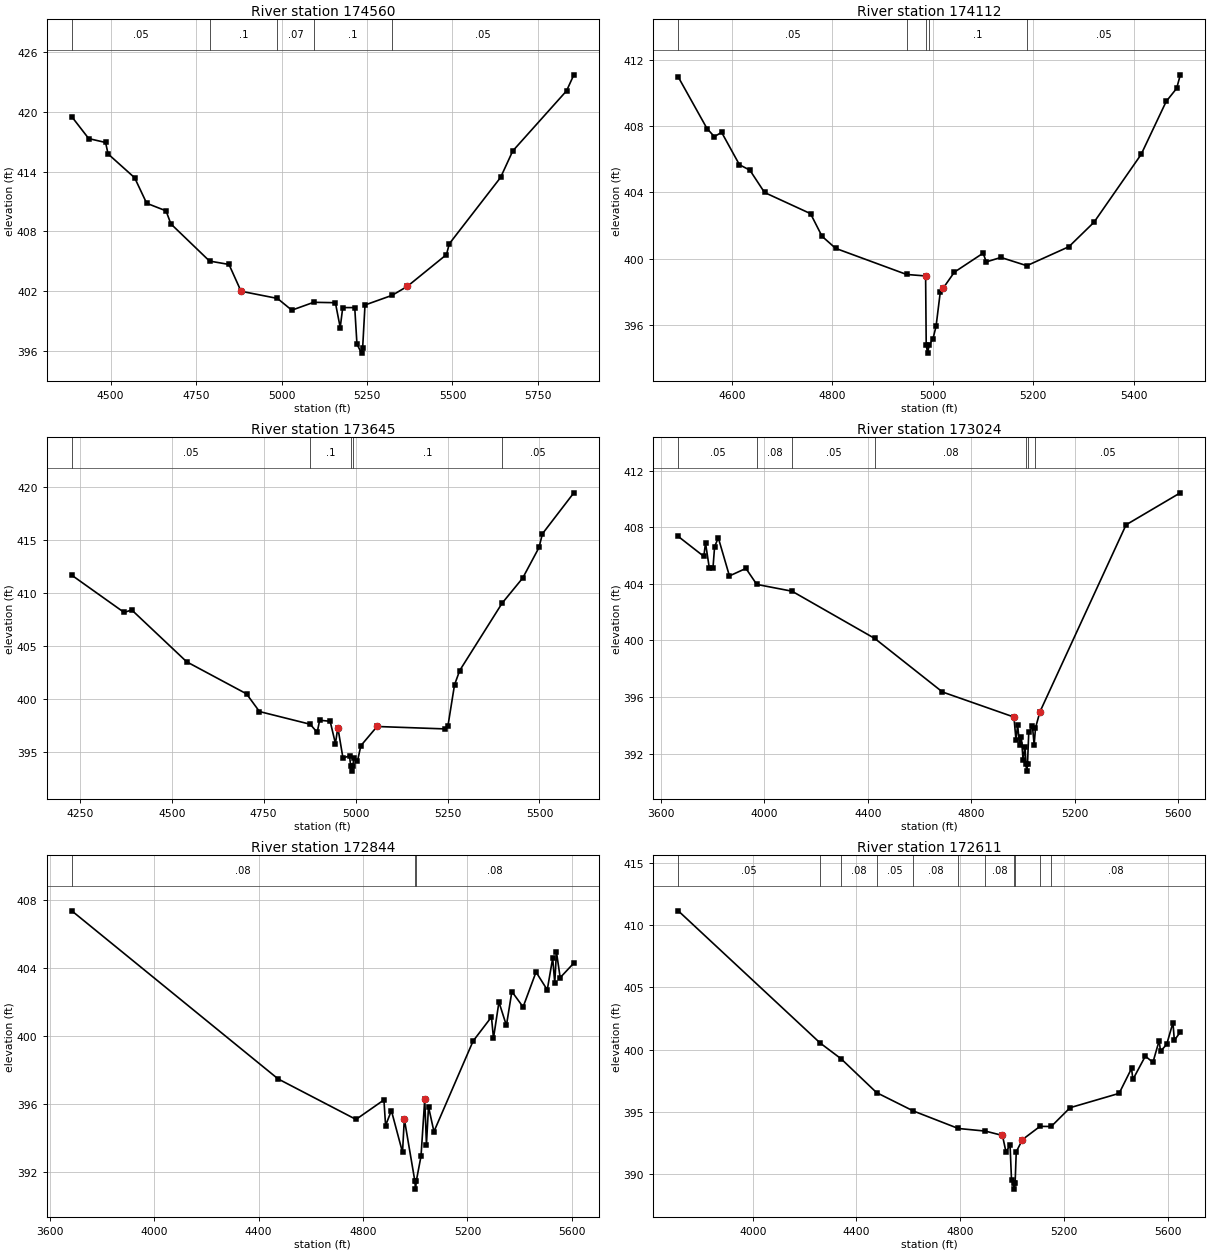
Type RM Length L Ch R = 1 ,174560  ,448,448,448
BEGIN DESCRIPTION:
SULPHUR CREEK 208.0
END DESCRIPTION:
XS GIS Cut Line= 3
      2299787.71     13448446.84      2299174.14     13447872.98
      2298587.74     13447646.86
#Sta/Elev= 30
  4386.5  419.52  4436.1  417.32  4485.4  416.93  4492.7  415.78  4570.4  413.39
  4605.6  410.83  4662.2  410.07  4676.4  408.76  4789.4  405.03  4846.4  404.69
  4881.6     402  4988.1  401.28  5030.1   400.1  5094.1  400.89  5157.6  400.85
  5171.7  398.36  5179.1  400.36  5214.2  400.36  5220.7  396.69    5234  395.79
  5237.3  396.29  5244.2  400.62  5323.4  401.59  5368.1  402.49  5482.6  405.68
  5490.7  406.76  5640.8  413.42  5676.4  416.08  5833.7  422.11  5855.1  423.72
#Mann= 5 ,-1 , 0
  4386.5     .05       0  4789.4      .1       0  4988.1     .07       0
  5094.1      .1       0  5323.4     .05       0
Bank Sta=4881.6,5368.1
XS Rating Curve= 0 ,0
Exp/Cntr=0.3,0.1

Type RM Length L Ch R = 1 ,174112  ,467,467,467
BEGIN DESCRIPTION:
SULPHUR CREEK 207.0
END DESCRIPTION:
XS GIS Cut Line= 3
      2299787.71     13447946.85      2299387.72     13447646.85
      2298987.71     13447346.85
#Sta/Elev= 30
  4493.2  410.99  4550.5  407.87  4565.1  407.38  4579.6  407.64  4615.1  405.68
  4635.9  405.35  4665.1     404  4756.7  402.72  4779.6  401.35  4806.7  400.62
    4948  399.04  4985.9  398.95  4987.1  394.78  4989.8  394.28  4993.1  394.78
  5000.5  395.14  5006.7   395.9  5015.1  397.97  5021.3  398.23  5043.2  399.18
  5100.5  400.33  5106.7   399.8  5135.9  400.07  5187.5  399.57  5271.3  400.72
  5321.3   402.2  5415.1   406.3  5465.1  409.51  5485.9   410.3  5493.2  411.12
#Mann= 5 ,-1 , 0
  4493.2     .05       0    4948      .1       0  4987.1     .07       0
  4993.1      .1       0  5187.5     .05       0
Bank Sta=4985.9,5021.3
XS Rating Curve= 0 ,0
Exp/Cntr=0.3,0.1

Type RM Length L Ch R = 1 ,173645  ,621,621,621
BEGIN DESCRIPTION:
SULPHUR CREEK 206.0
END DESCRIPTION:
XS GIS Cut Line= 3
       2300087.7     13447696.84       2299523.1      13447220.2
      2298937.75     13446996.86
#Sta/Elev= 30
  4228.1  411.65  4370.4  408.14  4391.3  408.37  4540.7  403.48  4703.3  400.46
  4738.5  398.79  4876.7  397.59  4895.5  396.82  4902.2  397.97  4930.8  397.87
  4945.1  395.77  4951.7  397.28  4965.7  394.39  4983.4  394.62  4986.6  393.67
  4989.3  393.17  4992.6  393.67    4995  394.39  5004.9  394.09  5014.3  395.57
  5058.4  397.38  5244.3  397.15    5251  397.41    5269  401.31  5283.1  402.66
  5398.6  409.02  5454.4  411.38  5498.9  414.27  5507.9  415.55  5593.5  419.42
#Mann= 5 ,-1 , 0
  4228.1     .05       0  4876.7      .1       0  4986.6     .07       0
  4992.6      .1       0  5398.6     .05       0
Bank Sta=4951.7,5058.4
XS Rating Curve= 0 ,0
Exp/Cntr=0.3,0.1

Type RM Length L Ch R = 1 ,173024  ,180,180,180
BEGIN DESCRIPTION:
Mapping XS eb20101d
END DESCRIPTION:
XS GIS Cut Line= 2
      2300454.38     13447478.86      2298959.59     13446239.28
#Sta/Elev= 30
  3667.1  407.35  3766.1  405.94  3772.6  406.89    3787  405.15  3801.3  405.09
  3807.8  406.63  3822.1  407.25  3865.1  404.56  3928.9  405.09  3970.8  403.96
  4107.2  403.48  4427.3  400.14  4689.1  396.36  4965.5  394.59  4973.4  392.98
  4979.8  394.03  4987.7  392.59  4994.2  393.18  5000.8  391.57  5008.5  392.49
    5012  391.27  5014.7  390.77    5018  391.27  5022.8   393.5  5037.2  393.93
  5043.7  392.62  5048.9  393.82  5065.8  394.95  5399.2  408.17    5609  410.43
#Mann= 7 ,-1 , 0
  3667.1     .05       0  3970.8     .08       0  4107.2     .05       0
  4427.3     .08       0    5012     .07       0    5018     .08       0
  5048.9     .05       0
Bank Sta=4965.5,5065.8
XS Rating Curve= 0 ,0
Exp/Cntr=0.3,0.1

Type RM Length L Ch R = 1 ,172844  ,233,233,233
BEGIN DESCRIPTION:
SULPHUR CREEK 205.0
END DESCRIPTION:
XS GIS Cut Line= 2
      2300464.81      13447312.2       2298981.6     13446089.21
#Sta/Elev= 30
  3684.8  407.38  4474.7  397.47  4773.1  395.08    4880  396.23  4886.4  394.72
  4908.6   395.6  4951.2  393.14  4958.1  395.11  4998.2  391.47  5000.9  390.97
  5004.2  391.47    5022  392.91  5036.3  396.26  5042.8   393.6  5050.7  395.83
  5071.5  394.36  5221.4   399.7  5291.7  401.12  5299.5  399.87  5320.4     402
    5349  400.62  5369.9  402.62  5412.9  401.71  5462.4  403.77  5505.4  402.72
  5526.2  404.59  5534.1  403.12  5540.6  404.95  5554.9  403.44  5607.2   404.3
#Mann= 3 ,-1 , 0
  3684.8     .08       0  4998.2     .07       0  5004.2     .08       0
Bank Sta=4958.1,5036.3
XS Rating Curve= 0 ,0
Exp/Cntr=0.3,0.1

Type RM Length L Ch R = 1 ,172611  ,89,89,89
BEGIN DESCRIPTION:
SULPHUR CREEK 204.0
END DESCRIPTION:
XS GIS Cut Line= 2
      2300746.06     13446760.12      2298955.98     13446021.19
#Sta/Elev= 30
  3712.7  411.15  4260.3  400.53  4340.7  399.27  4477.8  396.55  4619.1  395.08
    4793  393.67  4897.6  393.46  4963.3  393.11  4976.7   391.8  4992.6  392.32
  4998.3   389.5  5006.1   389.3  5008.9   388.8  5012.1   389.3  5016.5   391.8
  5040.5  392.78  5108.1  393.84  5151.4  393.83  5224.2  395.34  5413.3  396.49
  5461.1  398.49  5466.5  397.61  5514.4  399.48  5543.7  398.98  5567.6  400.72
    5573  399.87  5596.9  400.43  5620.9  402.17  5626.3  400.75  5649.3  401.41
#Mann= 11 ,-1 , 0
  3712.7     .05       0  4260.3      .1       0  4340.7     .08       0
  4477.8     .05       0  4619.1     .08       0    4793     .05       0
  4897.6     .08       0  5006.1     .07       0  5012.1     .08       0
  5108.1     .05       0  5151.4     .08       0
Bank Sta=4963.3,5040.5
XS Rating Curve= 0 ,0
Exp/Cntr=0.3,0.1

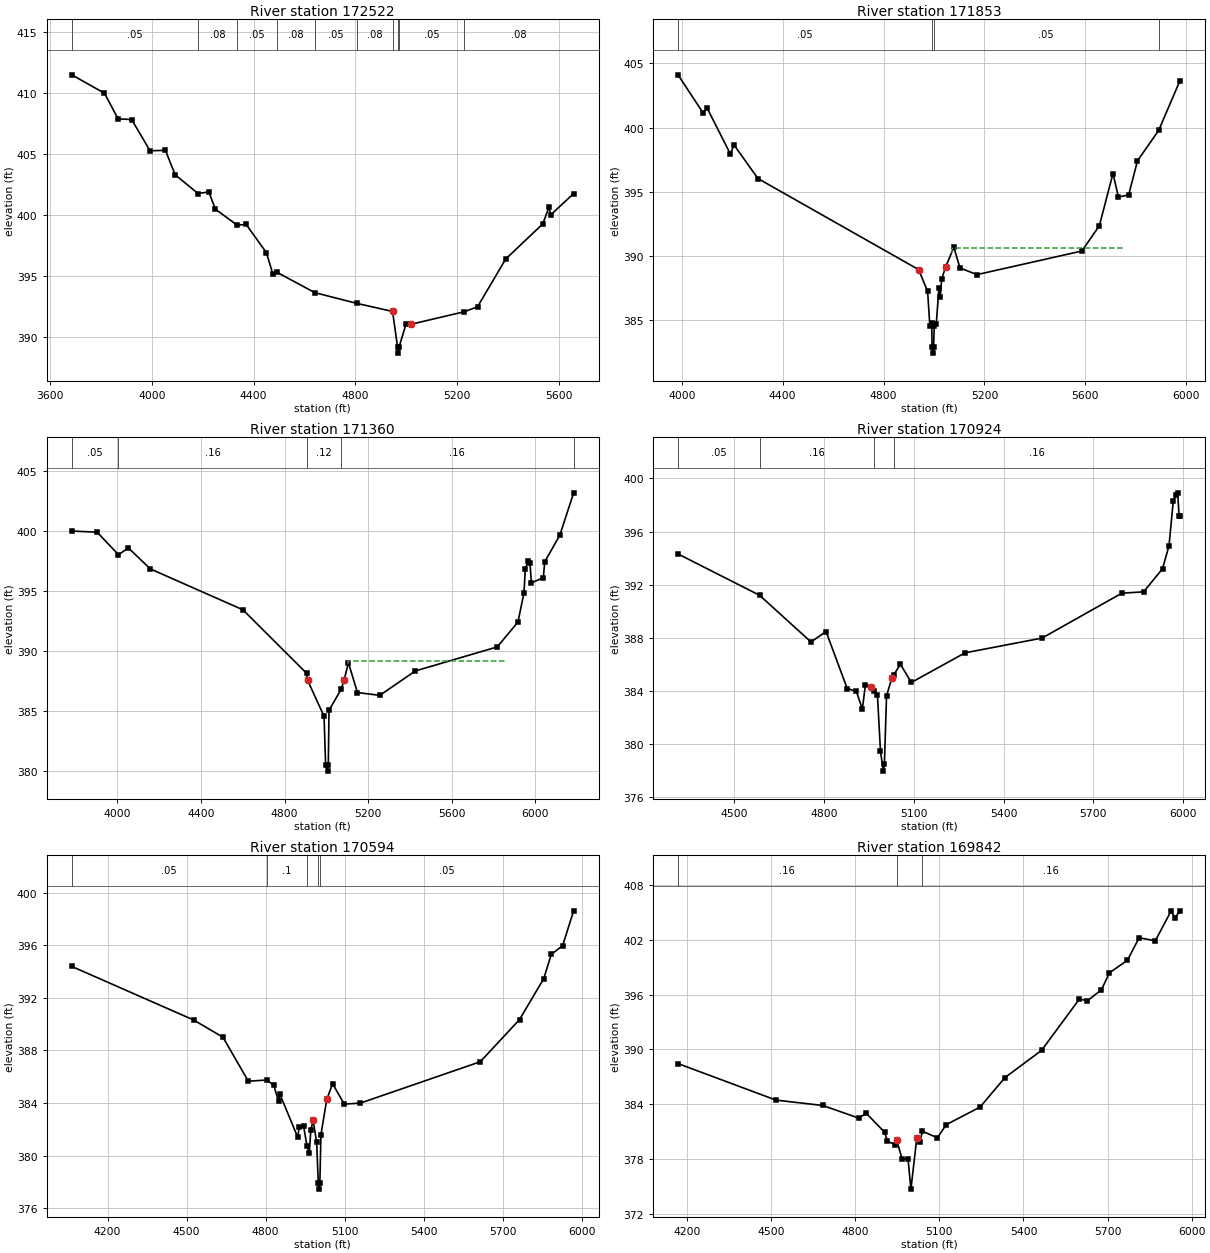
Type RM Length L Ch R = 1 ,172522  ,669,669,669
BEGIN DESCRIPTION:
SULPHUR CREEK 203.0
END DESCRIPTION:
XS GIS Cut Line= 2
      2300798.17     13446650.76      2298950.95      13445958.7
#Sta/Elev= 30
  3685.2  411.48  3813.8  409.97  3867.2  407.87  3920.6  407.81  3992.8  405.25
  4053.4  405.28  4091.5  403.28  4181.5  401.74  4224.3  401.87  4249.2  400.46
  4335.6  399.14  4370.3  399.21  4450.4  396.88  4475.4  395.14  4492.9  395.26
  4640.9   393.6  4804.4  392.73  4946.1  392.06  4965.6  389.14  4968.3  388.64
  4971.6  389.14  4999.2  391.04  5018.5  391.01  5228.7  392.04  5280.2  392.45
  5390.6  396.36  5536.6  399.25  5561.5  400.66  5566.9  399.97  5657.8  401.74
#Mann= 10 ,-1 , 0
  3685.2     .05       0  4181.5     .08       0  4335.6     .05       0
  4492.9     .08       0  4640.9     .05       0  4804.4     .08       0
  4946.1     .05       0  4965.6     .03       0  4971.6     .05       0
  5228.7     .08       0
Bank Sta=4946.1,5018.5
XS Rating Curve= 0 ,0
Exp/Cntr=0.3,0.1

Type RM Length L Ch R = 1 ,171853  ,493,493,493
BEGIN DESCRIPTION:
SULPHUR CREEK 202.0
END DESCRIPTION:
XS GIS Cut Line= 3
      2300587.71     13446146.85      2299764.42     13445569.16
      2298851.48      13445936.7
#Sta/Elev= 30
  3985.1   404.1  4084.9  401.12  4099.7  401.54  4192.8  397.93  4206.9  398.65
  4301.9  396.03    4939  388.94  4974.7  387.24  4983.4  384.58  4990.8  384.78
  4992.4  382.94  4995.1  382.44  4998.4  382.94  5000.8  384.55  5008.9  384.71
  5019.5   387.5  5024.9  386.84  5030.4  388.22  5046.6  389.17  5078.7  390.68
  5102.8  389.07  5170.5  388.55  5586.4  390.39  5655.6  392.36  5709.5  396.42
  5731.1  394.59  5771.7  394.75  5806.7  397.41  5890.6  399.77    5975  403.64
#Mann= 4 ,-1 , 0
  3985.1     .05       0  4992.4     .03       0  4998.4     .05       0
  5890.6     .08       0
#XS Ineff= 1 ,-1
 5070.01 5748.94  390.59
Permanent Ineff=
       T
Bank Sta=4939,5046.6
XS Rating Curve= 0 ,0
Exp/Cntr=0.3,0.1

Type RM Length L Ch R = 1 ,171360  ,436,436,436
BEGIN DESCRIPTION:
SULPHUR CREEK 201.0
END DESCRIPTION:
XS GIS Cut Line= 3
      2300887.73     13444946.85      2299687.72     13445146.85
      2298766.86     13445890.35
#Sta/Elev= 30
  3782.4     400  3904.1   399.9  4005.4  398.03  4053.6  398.59  4157.5  396.85
    4601  393.44  4905.2  388.16  4910.3  387.57  4988.8  384.58  4996.4  380.54
  5005.9  380.01  5009.2  380.51  5012.6  385.07  5070.1  386.81  5084.5  387.57
  5105.3  389.04  5148.5  386.55  5255.6  386.32  5425.2  388.35  5816.9  390.35
  5916.1  392.42  5944.9  394.85  5951.3  396.85  5965.7  397.54  5973.6  397.34
  5980.1  395.67  6037.6  396.13    6044  397.44    6116  399.64  6182.5  403.18
#Mann= 5 ,-1 , 0
  3782.4     .05       0  4005.4     .16       0  4905.2     .12       0
  5070.1     .16       0  6182.5     .08       0
#XS Ineff= 1 ,-1
 5103.96 5855.02  389.19
Permanent Ineff=
       T
Bank Sta=4910.3,5084.5
XS Rating Curve= 0 ,0
Exp/Cntr=0.3,0.1

Type RM Length L Ch R = 1 ,170924  ,330,330,330
BEGIN DESCRIPTION:
SULPHUR CREEK 200.0
END DESCRIPTION:
XS GIS Cut Line= 3
      2300037.69     13444796.86      2299337.72     13444896.85
      2298787.72     13445696.86
#Sta/Elev= 30
  4311.6  394.32  4584.3  391.21    4756   387.7  4806.5  388.48  4877.2  384.19
  4907.6  383.99  4927.8  382.64  4937.9  384.45  4958.1  384.32  4968.2  384.02
  4978.3  383.69  4988.4  379.46  4998.2  377.98  5001.5  378.48  5008.6  383.63
  5026.1  384.97  5032.2   385.2  5055.1  386.02  5091.5  384.65    5271  386.88
  5528.4  387.99  5795.3  391.37  5868.1  391.47  5931.3  393.21  5953.1  394.95
  5967.2  398.29    5976  398.72    5982  398.92  5986.5  397.21  5989.5  397.21
#Mann= 4 ,-1 , 0
  4311.6     .05       0  4584.3     .16       0  4968.2     .12       0
  5032.2     .16       0
Bank Sta=4958.1,5026.1
XS Rating Curve= 0 ,0
Exp/Cntr=0.3,0.1

Type RM Length L Ch R = 1 ,170594  ,752,752,752
BEGIN DESCRIPTION:
SULPHUR CREEK 199.0
END DESCRIPTION:
XS GIS Cut Line= 4
      2300083.05     13444735.99      2299254.07     13444592.76
      2298813.54     13444822.79      2298387.73     13445196.84
#Sta/Elev= 30
    4064  394.39  4526.1  390.32  4637.7  389.01  4734.2  385.66  4803.6  385.75
  4830.5  385.37  4848.8  384.12  4853.9  384.68  4921.5   381.4  4927.1  382.15
  4943.6  382.28  4957.1  380.71  4965.7  380.18  4971.3  381.92  4980.1  382.68
  4993.4  381.04  4999.7  377.95  5002.4  377.45  5005.7  377.95  5009.8  381.59
  5031.9  384.28    5054  385.47  5098.2  383.92  5158.8  383.99  5614.6  387.14
  5763.6  390.35  5855.6  393.47  5884.1  395.31  5926.8  395.96    5969  398.62
#Mann= 5 ,-1 , 0
    4064     .05       0  4803.6      .1       0  4957.1     .05       0
  4999.7     .03       0  5005.7     .05       0
Bank Sta=4980.1,5031.9
XS Rating Curve= 0 ,0
Exp/Cntr=0.3,0.1

Type RM Length L Ch R = 1 ,169842  ,672,672,672
BEGIN DESCRIPTION:
SULPHUR CREEK 198.0
END DESCRIPTION:
XS GIS Cut Line= 3
      2299471.31      13443961.5       2298268.7     13444335.64
       2297940.1     13444753.05
#Sta/Elev= 30
  4167.6  388.45    4517  384.45  4684.5  383.86  4811.9  382.48  4839.2  383.01
  4904.3  380.94  4914.9  379.95  4942.1  379.56  4947.3  380.09  4967.3  377.99
  4988.2  377.99  4998.5   374.7  5019.7  380.35  5030.1  379.86  5039.7  381.04
    5093  380.32  5124.4  381.76  5245.4  383.69  5333.8  386.91  5464.7   389.9
  5599.4  395.51  5628.3  395.34    5678  396.52  5706.9  398.39  5771.1  399.77
  5812.7  402.23  5870.5   401.9  5926.5  405.15    5941  404.43  5958.3  405.18
#Mann= 3 ,-1 , 0
  4167.6     .16       0  4947.3     .12       0  5039.7     .16       0
Bank Sta=4947.3,5019.7
XS Rating Curve= 0 ,0
Exp/Cntr=0.3,0.1