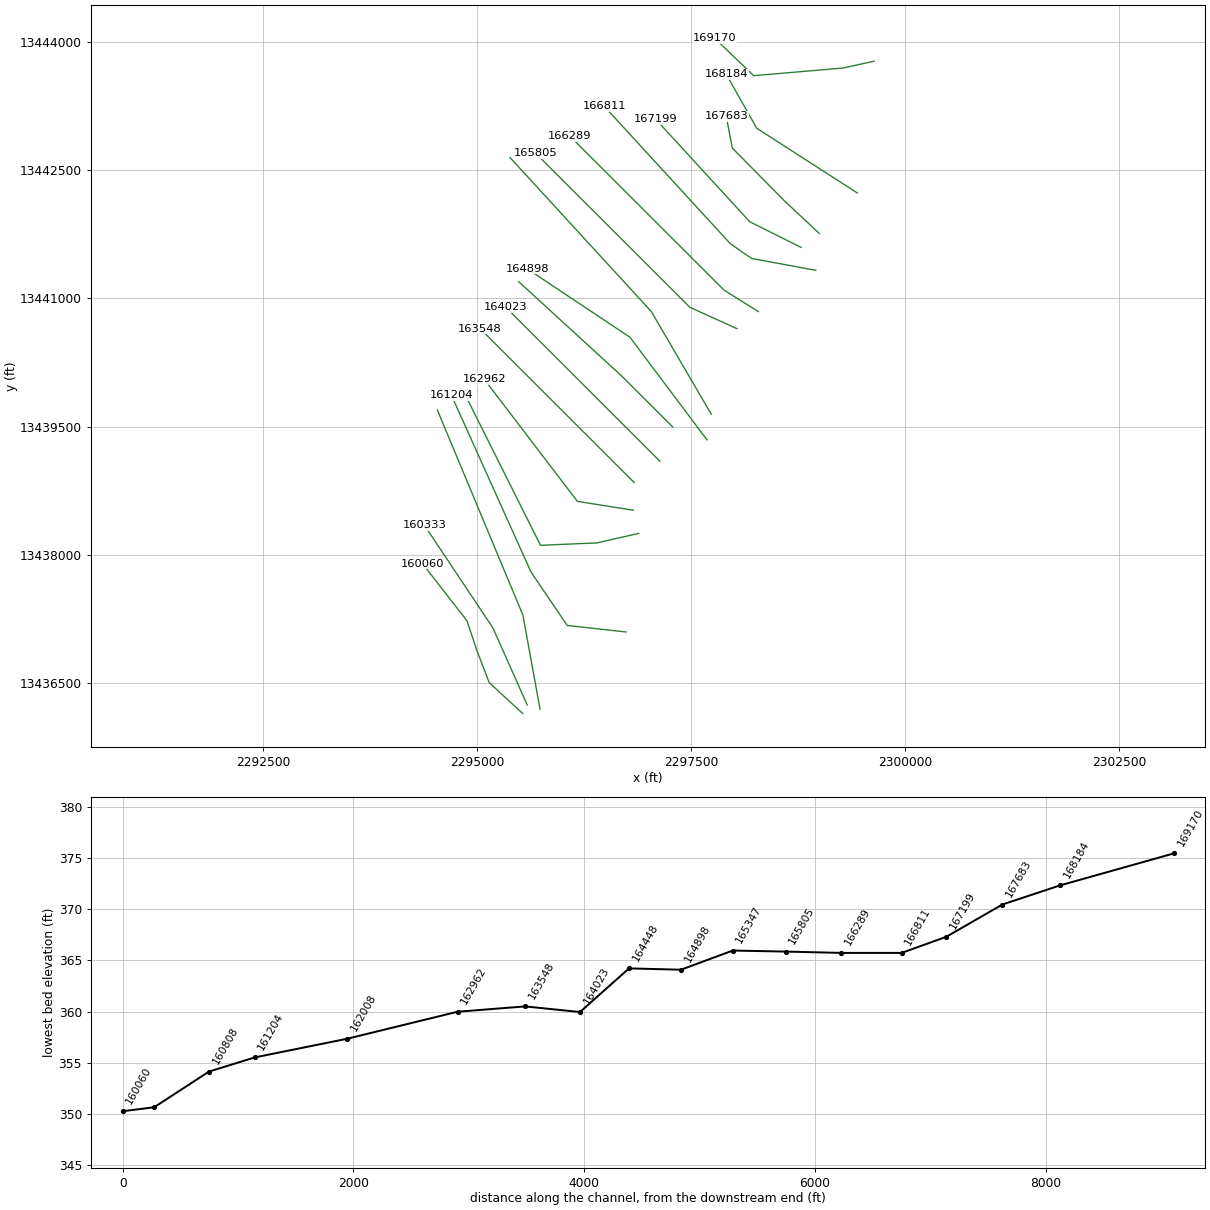
HEC-RAS study SULPHUR CREEK.prj: SULPHUR CREEK Base Level Engineering

--- SULPHUR CREEK.g01 (geometry) --- (continued)

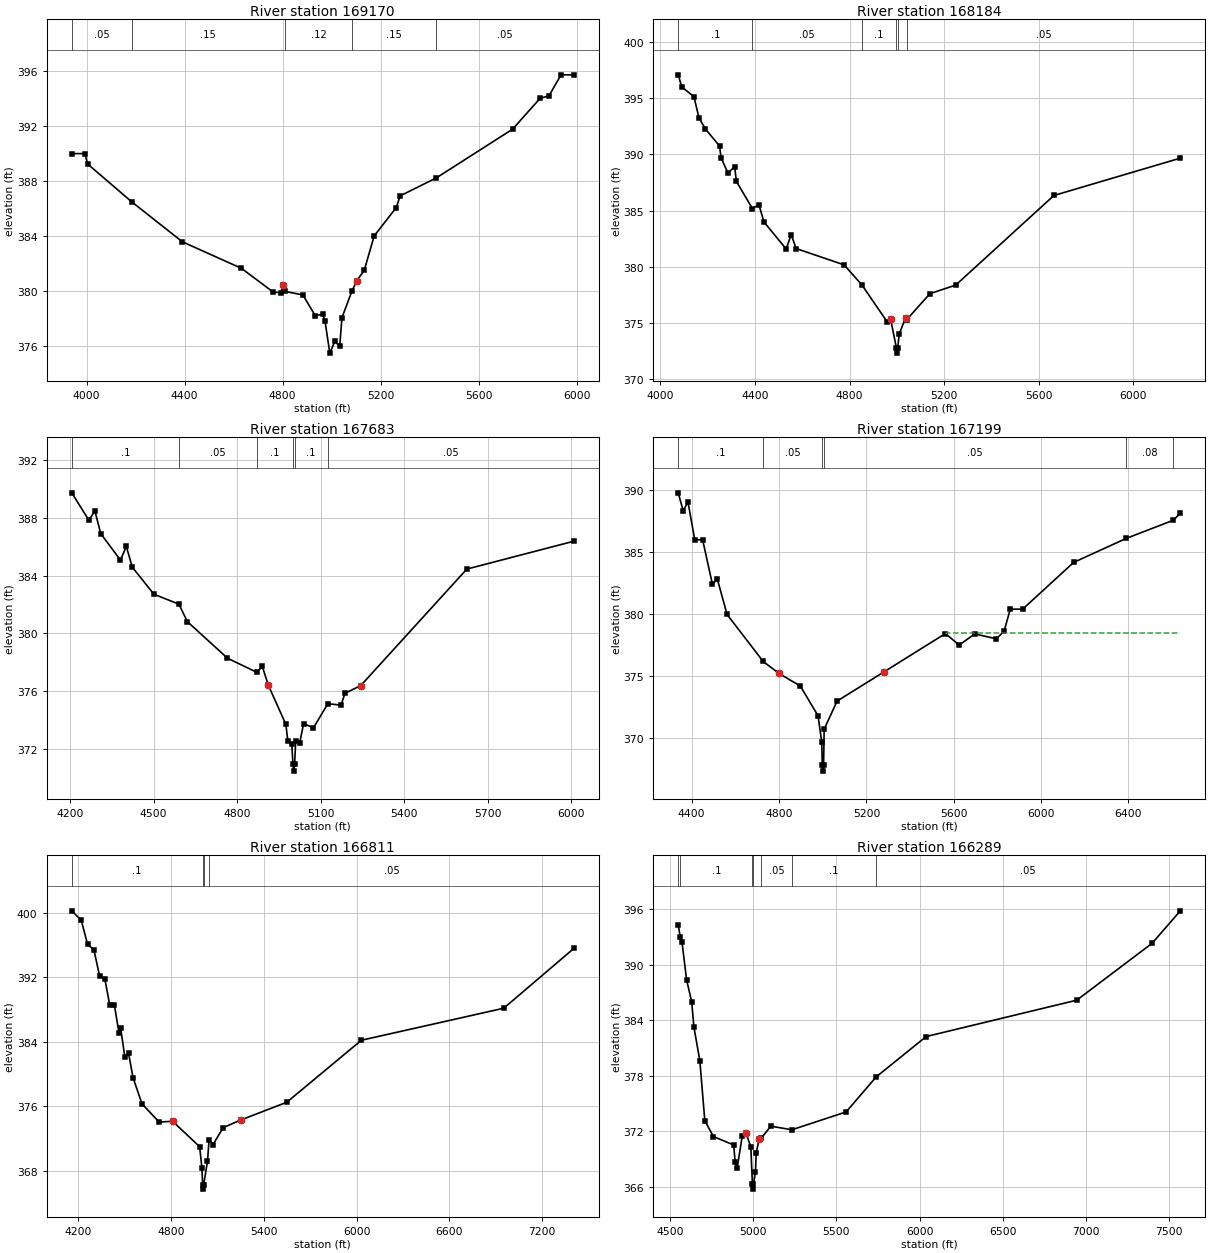
Type RM Length L Ch R = 1 ,169170  ,986,986,986
BEGIN DESCRIPTION:
SULPHUR CREEK 197.0
END DESCRIPTION:
XS GIS Cut Line= 4
      2299640.55     13443774.45      2299275.29     13443694.27
      2298233.06     13443605.19      2297778.75     13444041.69
#Sta/Elev= 30
  3939.1  389.99    3993  389.99  4003.4  389.24  4183.5  386.48  4390.9  383.56
  4631.8  381.63  4762.3  379.89  4792.4  379.86  4802.4  380.45  4809.3  379.95
  4882.7  379.69  4933.2  378.18    4963  378.28    4973  377.79  4992.8  375.45
  5013.2  376.31  5033.2  375.95  5042.1  378.02  5083.4  379.99  5103.5  380.74
  5133.6   381.5  5173.8  383.99  5264.1  386.06    5280  386.91  5427.7  388.22
    5739  391.77  5851.9  394.03  5887.4  394.19  5936.8  395.73  5989.1  395.73
#Mann= 5 ,-1 , 0
  3939.1     .05       0  4183.5     .15       0  4809.3     .12       0
  5083.4     .15       0  5427.7     .05       0
Bank Sta=4802.4,5103.5
XS Rating Curve= 0 ,0
Exp/Cntr=0.3,0.1

Type RM Length L Ch R = 1 ,168184  ,501,501,501
BEGIN DESCRIPTION:
SULPHUR CREEK 196.0
END DESCRIPTION:
XS GIS Cut Line= 3
      2299444.51     13442233.39       2298268.7     13442990.54
      2297912.89      13443622.1
#Sta/Elev= 30
  4075.6  397.08  4090.4     396  4141.9  395.14  4163.1  393.27  4190.7  392.26
  4250.2  390.75  4256.8   389.7  4285.9  388.35  4314.2  388.91  4321.6   387.6
  4389.5  385.18  4416.7  385.53  4438.4  383.99  4532.1  381.59  4553.2  382.87
  4574.4  381.63  4777.1  380.18  4853.3  378.37  4958.6  375.13  4973.8  375.36
  4997.9  372.83  5000.6  372.33  5003.9  372.83  5010.1  374.02  5037.2  375.49
    5041  375.29  5140.2  377.62  5249.1  378.38  5664.4  386.35    6199  389.67
#Mann= 6 ,-1 , 0
  4075.6      .1       0  4389.5     .05       0  4853.3      .1       0
  4997.9     .07       0  5003.9      .1       0    5041     .05       0
Bank Sta=4973.8,5037.2
XS Rating Curve= 0 ,0
Exp/Cntr=0.3,0.1

Type RM Length L Ch R = 1 ,167683  ,484,484,484
BEGIN DESCRIPTION:
SULPHUR CREEK 195.0
END DESCRIPTION:
XS GIS Cut Line= 4
      2298999.17     13441761.23      2298589.38     13442144.29
      2297983.64     13442758.94      2297912.67     13443131.52
#Sta/Elev= 30
  4206.3  389.73  4267.8  387.83  4289.3  388.48  4310.3  386.91  4381.2  385.07
  4402.2  386.02  4423.7  384.58  4501.3  382.71  4591.1  382.02  4621.5  380.81
  4765.5  378.28  4871.2   377.3  4890.5  377.72  4911.6  376.44  4975.3  373.69
  4982.3  372.54  4996.5  372.34  5000.6  370.96  5003.4  370.46  5006.6  370.96
  5010.6  372.54  5024.8  372.41  5038.9  373.75  5074.3  373.46  5126.1  375.13
  5173.3  375.03  5187.5  375.85    5244  376.38  5625.2  384.45  6009.5  386.38
#Mann= 6 ,-1 , 0
  4206.3      .1       0  4591.1     .05       0  4871.2      .1       0
  5000.6     .07       0  5006.6      .1       0  5126.1     .05       0
Bank Sta=4911.6,5244
XS Rating Curve= 0 ,0
Exp/Cntr=0.3,0.1

Type RM Length L Ch R = 1 ,167199  ,388,388,388
BEGIN DESCRIPTION:
SULPHUR CREEK 194.0
END DESCRIPTION:
XS GIS Cut Line= 3
      2298787.75     13441596.84      2298187.72     13441896.85
      2297087.75     13443096.83
#Sta/Elev= 30
  4338.6  389.76    4361  388.32  4383.4  389.01  4414.1  385.99  4450.4  385.96
  4495.2  382.38  4517.5  382.81  4562.2  379.95  4727.5  376.16  4799.8   375.2
  4897.7  374.18  4978.7  371.78  4995.5  369.69  4998.1  367.82  5000.8  367.32
  5004.1  367.82  5006.7   370.7  5065.9  372.97  5278.6   375.3  5561.6  378.41
  5625.2  377.49  5696.1  378.38  5795.3  377.99  5830.5  378.61  5858.9  380.38
  5915.6  380.38    6149  384.15  6390.4  386.09  6605.4  387.55  6637.3  388.12
#Mann= 6 ,-1 , 0
  4338.6      .1       0  4727.5     .05       0  4998.1     .03       0
  5004.1     .05       0  6390.4     .08       0  6605.4     .05       0
#XS Ineff= 2 , 0
                         5563.07          378.42
Permanent Ineff=
       T       T
Bank Sta=4799.8,5278.6
XS Rating Curve= 0 ,0
Exp/Cntr=0.3,0.1

Type RM Length L Ch R = 1 ,166811  ,522,522,522
BEGIN DESCRIPTION:
SULPHUR CREEK 193.0
END DESCRIPTION:
XS GIS Cut Line= 4
      2298958.32     13441329.13       2298208.3     13441468.02
      2297959.35     13441641.44      2296487.74     13443246.84
#Sta/Elev= 30
  4159.8  400.23  4221.4  399.05  4262.1  396.06  4302.8  395.41    4339  392.19
    4374  391.73  4404.5  388.62    4435  388.55  4465.5  385.04  4475.7  385.66
  4502.7  382.12  4526.5  382.61  4555.6  379.56  4613.5  376.31  4724.4  374.05
  4811.3  374.15    4986     371  5000.9  368.31  5005.6  366.24  5008.3  365.74
  5011.6  366.24  5036.7  369.19  5047.2  371.89  5072.4  371.26  5137.9  373.36
  5252.1  374.31  5549.3  376.51  6030.9  384.19  6950.9  388.16  7403.8  395.57
#Mann= 4 ,-1 , 0
  4159.8      .1       0  5005.6     .07       0  5011.6      .1       0
  5047.2     .05       0
Bank Sta=4811.3,5252.1
XS Rating Curve= 0 ,0
Exp/Cntr=0.3,0.1

Type RM Length L Ch R = 1 ,166289  ,484,484,484
BEGIN DESCRIPTION:
SULPHUR CREEK 192.0
END DESCRIPTION:
XS GIS Cut Line= 3
      2298287.68     13440846.88      2297887.72     13441096.85
      2296087.74     13442896.83
#Sta/Elev= 30
  4549.6  394.29  4561.4  392.99  4572.5  392.39  4599.7  388.35  4630.3  385.99
  4643.9  383.23  4679.3  379.63  4709.3  373.13  4761.2  371.42  4882.7  370.51
  4891.5   368.7  4903.9  368.04  4934.6  371.52  4955.8  371.82  4985.9  370.31
  4995.3  366.24    4998  365.74  5001.3  366.24  5013.6  367.55  5018.3  369.65
  5035.4  371.13    5049  371.26  5106.1  372.54  5232.3  372.15  5558.7  374.08
  5739.1  377.86  6039.5  382.22  6944.6  386.15  7397.1  392.29  7566.8   395.8
#Mann= 7 ,-1 , 0
  4549.6     .05       0  4561.4      .1       0  4995.3     .07       0
  5001.3      .1       0    5049     .05       0  5232.3      .1       0
  5739.1     .05       0
Bank Sta=4955.8,5035.4
XS Rating Curve= 0 ,0
Exp/Cntr=0.3,0.1

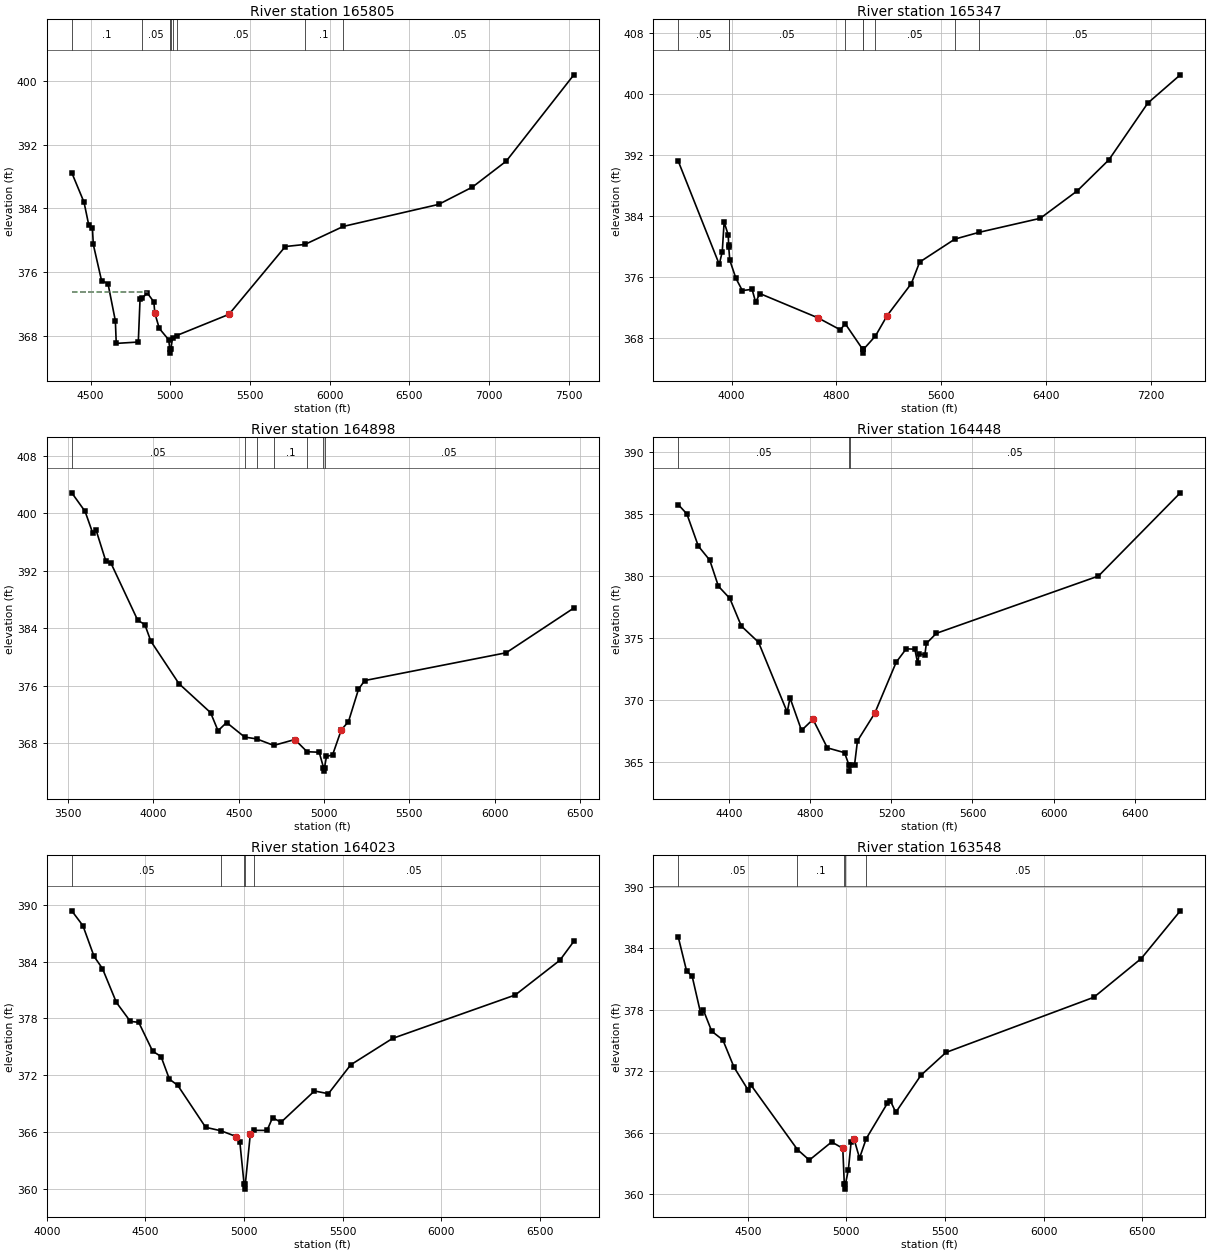
Type RM Length L Ch R = 1 ,165805  ,458,458,458
BEGIN DESCRIPTION:
SULPHUR CREEK 191.0
END DESCRIPTION:
XS GIS Cut Line= 3
      2298037.73     13440646.85      2297487.72     13440896.85
      2295687.75     13442696.82
#Sta/Elev= 30
  4381.4  388.48  4458.3  384.78    4488  381.92    4511  381.53  4516.5  379.49
  4568.1  374.97  4608.8  374.57  4654.9  369.91  4660.4  367.09  4798.8  367.26
  4809.8  372.67  4820.4  372.74  4855.9  373.39  4896.6  372.28  4902.1   370.9
  4930.6  368.96  4989.1  367.55  4996.7  366.37  4999.5  365.87  5002.7  366.37
  5013.8  367.75  5038.9  368.07  5367.4  370.73    5721  379.23  5843.7  379.49
  6084.7  381.75  6682.6  384.51  6894.8  386.68  7106.9  389.93  7531.1  400.75
#Mann= 8 ,-1 , 0
  4381.4      .1       0  4820.4     .05       0  4996.7     .03       0
  5002.7     .05       0  5013.8      .1       0  5038.9     .05       0
  5843.7      .1       0  6084.7     .05       0
#XS Ineff= 2 , 0
         4854.55  373.51
Permanent Ineff=
       T       T
Bank Sta=4902.1,5367.4
XS Rating Curve= 0 ,0
Exp/Cntr=0.3,0.1

Type RM Length L Ch R = 1 ,165347  ,449,449,449
BEGIN DESCRIPTION:
SULPHUR CREEK 190.0
END DESCRIPTION:
XS GIS Cut Line= 3
      2297737.73     13439646.83      2297037.72     13440846.85
      2295387.72     13442646.86
#Sta/Elev= 30
  3593.4  391.17  3906.4  377.62  3929.2  379.27  3943.6  383.17  3975.1  381.46
  3978.1   380.1  3978.6  379.87    3987  378.15  4033.4  375.79  4082.6  374.18
    4157  374.34  4184.3  372.64  4215.7  373.79  4659.8   370.6  4830.1  369.03
  4867.6  369.83  5000.9  366.47  5003.7  365.97  5006.9  366.47  5098.3  368.22
  5187.7   370.9  5372.1   375.1  5435.6  377.92  5703.8  380.93  5888.5  381.82
  6355.6  383.66  6638.6  387.27  6879.7  391.34  7176.9  398.79  7424.5  402.49
#Mann= 9 ,-1 , 0
  3593.4     .05       0  3978.1     .12       0  3978.6     .05       0
  4867.6      .1       0  5000.9     .07       0  5006.9      .1       0
  5098.3     .05       0  5703.8      .1       0  5888.5     .05       0
Bank Sta=4659.8,5187.7
XS Rating Curve= 0 ,0
Exp/Cntr=0.3,0.1

Type RM Length L Ch R = 1 ,164898  ,450,450,450
BEGIN DESCRIPTION:
SULPHUR CREEK 189.0
END DESCRIPTION:
XS GIS Cut Line= 3
      2297687.69     13439346.89      2296787.72     13440546.85
       2295587.7     13441346.87
#Sta/Elev= 30
  3521.6  402.85  3599.7  400.26  3643.4  397.31  3664.3  397.64  3721.6  393.31
  3749.7  393.14    3908  385.11  3949.7  384.51  3985.1  382.19  4149.7  376.28
  4335.1  372.24  4378.8  369.72  4428.8  370.87  4534.8  368.84    4605  368.59
  4705.3  367.68  4828.8   368.5  4900.5   366.8  4971.6  366.73  4996.7   364.6
  4999.4   364.1  5002.7   364.6  5014.3  366.14  5050.1  366.37  5101.2  369.85
  5143.2     371  5201.8  375.49  5237.9  376.71  6067.2  380.58  6463.8  386.81
#Mann= 7 ,-1 , 0
  3521.6     .05       0  4534.8      .1       0    4605     .05       0
  4705.3      .1       0  4900.5     .05       0  4996.7     .03       0
  5002.7     .05       0
Bank Sta=4828.8,5101.2
XS Rating Curve= 0 ,0
Exp/Cntr=0.3,0.1

Type RM Length L Ch R = 1 ,164448  ,425,425,425
BEGIN DESCRIPTION:
SULPHUR CREEK 188.0
END DESCRIPTION:
XS GIS Cut Line= 3
      2297287.71     13439496.87      2296687.72     13440096.85
      2295487.72     13441196.86
#Sta/Elev= 30
  4148.7  385.76  4191.1  385.01  4247.7  382.41  4304.2  381.27  4346.7  379.17
  4403.2  378.18  4459.8  375.95  4544.7  374.64  4686.1     369  4700.2  370.14
  4756.8  367.52  4813.4  368.41  4884.1  366.11  4968.9  365.72  4990.7  364.73
  4993.4  364.23  4996.7  364.73  5018.5  364.76  5032.7  366.67  5117.8   368.9
  5223.8  373.03  5273.2  374.11  5315.7  374.08  5329.9  372.93  5336.7  373.72
    5365  373.59  5372.4  374.54  5421.8  375.36  6221.5  379.99  6625.1  386.71
#Mann= 3 ,-1 , 0
  4148.7     .05       0  4990.7     .03       0  4996.7     .05       0
Bank Sta=4813.4,5117.8
XS Rating Curve= 0 ,0
Exp/Cntr=0.3,0.1

Type RM Length L Ch R = 1 ,164023  ,475,475,475
BEGIN DESCRIPTION:
SULPHUR CREEK 187.0
END DESCRIPTION:
XS GIS Cut Line= 3
      2297137.72     13439096.85      2296537.72     13439696.85
      2295337.71     13440896.86
#Sta/Elev= 30
    4127  389.37  4183.6   387.8  4240.1  384.55  4282.6  383.27  4353.3  379.69
    4424  377.69  4466.4  377.59  4537.1  374.54  4579.6  373.98    4622  371.59
  4664.4  370.93  4805.8   366.5  4884.2  366.13  4961.4  365.52  4979.1  364.96
  5000.8  360.47  5003.6  359.97  5006.8  360.47  5032.1  365.75  5049.5  366.18
    5117  366.17  5145.2  367.52  5187.7  367.03  5357.4  370.34  5428.1  370.05
  5541.2   373.1  5753.3  375.89  6375.6  380.48  6601.9  384.15  6672.6  386.15
#Mann= 5 ,-1 , 0
    4127     .05       0  4884.2      .1       0  5000.8     .07       0
  5006.8      .1       0  5049.5     .05       0
Bank Sta=4961.4,5032.1
XS Rating Curve= 0 ,0
Exp/Cntr=0.3,0.1

Type RM Length L Ch R = 1 ,163548  ,586,586,586
BEGIN DESCRIPTION:
SULPHUR CREEK 186.0
END DESCRIPTION:
XS GIS Cut Line= 3
      2296837.69     13438846.89      2296237.72     13439446.85
      2295037.75     13440646.83
#Sta/Elev= 30
  4147.5  385.11  4189.9  381.79  4218.2  381.27  4260.6  377.72  4274.7  377.99
  4317.2  375.92  4373.7  375.07  4430.3  372.41    4501  370.21  4515.1   370.7
  4751.8  364.38  4812.1  363.35  4925.3  365.12  4981.8   364.5  4989.4  361.02
  4992.2  360.52  4995.4  361.02  5010.1  362.43  5024.3  365.16  5038.4  365.42
  5066.7  363.55  5100.5  365.44  5208.1   368.9  5222.3  369.16  5250.5  368.01
  5377.8  371.62  5505.1  373.85  6254.6  379.23    6495  383.01    6693  387.66
#Mann= 5 ,-1 , 0
  4147.5     .05       0  4751.8      .1       0  4989.4     .07       0
  4995.4      .1       0  5100.5     .05       0
Bank Sta=4981.8,5038.4
XS Rating Curve= 0 ,0
Exp/Cntr=0.3,0.1

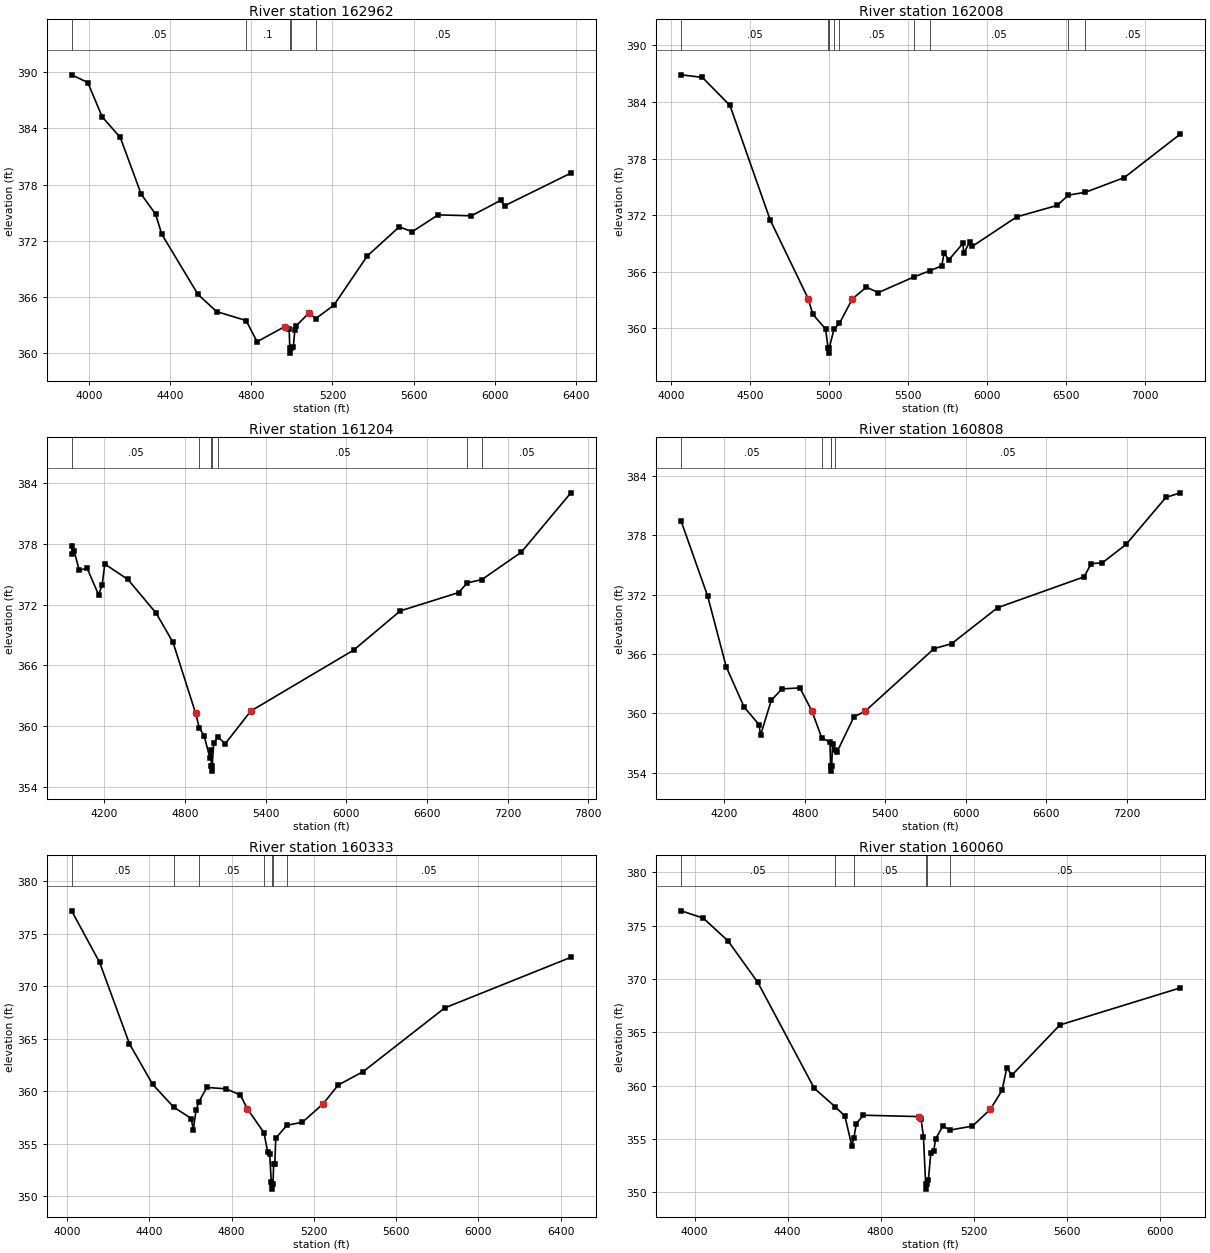
Type RM Length L Ch R = 1 ,162962  ,954,954,954
BEGIN DESCRIPTION:
SULPHUR CREEK 185.0
END DESCRIPTION:
XS GIS Cut Line= 3
      2296826.31     13438523.58      2296173.57     13438627.74
      2295083.27     13440058.33
#Sta/Elev= 30
  3914.9  389.73  3994.5  388.91  4065.4  385.24  4154.6  383.04  4257.8  376.97
  4328.7  374.84    4359   372.7  4537.4  366.27  4629.1  364.44  4774.5  363.48
  4828.6  361.22  4964.5  362.83  4986.6  362.53  4989.9   360.5  4992.6     360
  4995.9   360.5  5007.4   360.7  5014.8   362.5  5021.9  362.93  5086.4  364.34
  5116.4  363.67    5207  365.12  5371.2  370.37  5529.1  373.49  5593.2  372.97
  5720.4  374.77  5884.6  374.67    6028  376.31  6048.8  375.75  6374.6  379.23
#Mann= 5 ,-1 , 0
  3914.9     .05       0  4774.5      .1       0  4989.9     .07       0
  4995.9      .1       0  5116.4     .05       0
Bank Sta=4964.5,5086.4
XS Rating Curve= 0 ,0
Exp/Cntr=0.3,0.1

Type RM Length L Ch R = 1 ,162008  ,804,804,804
BEGIN DESCRIPTION:
SULPHUR CREEK 184.0
END DESCRIPTION:
XS GIS Cut Line= 4
      2296888.81     13438252.73      2296402.74     13438141.63
      2295743.02     13438113.85      2294847.16     13439905.56
#Sta/Elev= 30
  4061.6  386.88  4195.6  386.61  4370.5  383.63  4625.3  371.49  4865.5  363.16
  4895.5  361.48  4975.6  359.94  4992.6  357.87  4995.4  357.37  4998.6  357.87
  5029.4  359.91    5064  360.53  5145.7  363.12    5235  364.37  5309.2  363.78
  5535.4  365.45  5637.5  366.11  5711.7  366.63    5727  367.98  5756.4  367.26
  5845.8     369  5851.4  367.98  5890.5  369.19  5905.9   368.7  6186.8  371.82
  6442.5  373.03  6513.5  374.12  6622.2  374.43  6867.4  375.98  7223.7  380.61
#Mann= 9 ,-1 , 0
  4061.6     .05       0  4992.6     .03       0  4998.6     .05       0
  5029.4      .1       0    5064     .05       0  5535.4      .1       0
  5637.5     .05       0  6513.5     .08       0  6622.2     .05       0
Bank Sta=4865.5,5145.7
XS Rating Curve= 0 ,0
Exp/Cntr=0.3,0.1

Type RM Length L Ch R = 1 ,161204  ,396,396,396
BEGIN DESCRIPTION:
SULPHUR CREEK 183.0
END DESCRIPTION:
XS GIS Cut Line= 4
      2296743.03     13437099.96      2296055.52     13437176.35
      2295631.91     13437801.35      2294702.05     13439869.24
#Sta/Elev= 30
  3956.4  377.85  3961.7     377  3975.2  377.33    4012  375.43  4072.4  375.59
  4156.3     373  4183.1  373.92  4203.2  376.02  4374.3  374.51  4585.6  371.16
  4710.9  368.27  4878.3  361.29  4906.9  359.78  4941.5  359.06  4986.4  356.79
  4992.4  357.61  4996.1  356.04  4998.8  355.54  5002.1  356.04  5013.4   358.3
  5042.3  358.91  5100.2  358.27  5288.9  361.48  6055.1  367.52  6401.2  371.39
  6834.5   373.2  6900.9  374.17  7007.6  374.48  7301.8   377.2  7670.5  383.07
#Mann= 7 ,-1 , 0
  3956.4     .05       0  4906.9      .1       0  4996.1     .07       0
  5002.1      .1       0  5042.3     .05       0  6900.9     .08       0
  7007.6     .05       0
Bank Sta=4878.3,5288.9
XS Rating Curve= 0 ,0
Exp/Cntr=0.3,0.1

Type RM Length L Ch R = 1 ,160808  ,475,475,475
BEGIN DESCRIPTION:
SULPHUR CREEK 182.0
END DESCRIPTION:
XS GIS Cut Line= 3
      2295737.72     13436196.86      2295537.72     13437296.85
      2294537.73     13439696.83
#Sta/Elev= 30
  3879.8   379.4  4076.7  371.85  4215.2   364.7  4347.3  360.66  4459.1  358.86
  4470.6  357.78  4550.6  361.32  4630.7  362.47  4764.1  362.57  4854.3   360.2
  4926.3  357.52  4987.7  357.09  4992.3  354.66    4995  354.16  4998.3  354.66
  5000.5  354.66    5007  356.89  5025.7  356.31  5041.7  356.14  5166.3  359.65
  5248.6   360.2  5763.2  366.54  5893.2  367.03  6235.5  370.67  6880.1  373.79
  6933.2  375.13  7015.5   375.2  7193.2  377.07  7489.5  381.82  7597.8  382.28
#Mann= 5 ,-1 , 0
  3879.8     .05       0  4926.3      .1       0  4992.3     .07       0
  4998.3      .1       0  5025.7     .05       0
#XS Ineff= 1 ,-1
 3920.08  4715.7  362.43
Permanent Ineff=
       T
Bank Sta=4854.3,5248.6
XS Rating Curve= 0 ,0
Exp/Cntr=0.3,0.1

Type RM Length L Ch R = 1 ,160333  ,273,273,273
BEGIN DESCRIPTION:
SULPHUR CREEK 181.0
END DESCRIPTION:
XS GIS Cut Line= 3
      2295587.74     13436246.81      2295187.72     13437146.85
      2294387.69      13438346.9
#Sta/Elev= 30
  4022.7   377.2  4158.9  372.28  4303.8  364.53  4416.7  360.66    4519  358.49
  4604.8  357.41  4613.7   356.3    4628  358.23  4641.4  359.01    4680  360.37
    4773  360.24  4842.8  359.65    4877  358.33    4958  356.05  4975.5  354.23
  4985.7     354  4993.3  351.38  4995.7  351.18  4998.5  350.68  5001.7  351.18
  5004.9  353.12  5010.6  353.12  5015.1  355.54  5069.7  356.77  5144.3  357.05
  5246.5  358.83  5318.6   360.6  5440.3  361.88  5836.9  367.95  6449.9  372.77
#Mann= 7 ,-1 , 0
  4022.7     .05       0    4519      .1       0  4641.4     .05       0
    4958      .1       0  4995.7     .07       0  5001.7      .1       0
  5069.7     .05       0
Bank Sta=4877,5246.5
XS Rating Curve= 0 ,0
Exp/Cntr=0.3,0.1

Type RM Length L Ch R = 1 ,160060  ,563,563,563
BEGIN DESCRIPTION:
SULPHUR CREEK 180.0
END DESCRIPTION:
XS GIS Cut Line= 5
      2295533.94     13436148.39      2295143.92     13436507.46
      2295001.54     13436878.88      2294883.92     13437231.74
      2294363.89     13437900.35
#Sta/Elev= 30
  3942.6  376.38  4037.9  375.69  4143.9  373.56  4271.5  369.69  4514.9  359.74
  4604.2  358.02  4646.3  357.15  4676.3  354.36  4685.1  355.08  4695.6  356.43
  4725.7  357.22  4965.1  357.09  4973.8  356.89  4984.3  355.22  4993.7  350.79
  4996.5  350.29  4999.7  350.79  5005.4  351.15    5016  353.67  5028.3  353.87
    5037  355.02  5068.7  356.23  5096.5  355.82  5195.2   356.2  5272.5  357.78
  5322.2  359.55  5343.1  361.68  5363.9  360.96  5571.1  365.68  6089.5  369.16
#Mann= 6 ,-1 , 0
  3942.6     .05       0  4604.2      .1       0  4685.1     .05       0
  4993.7     .07       0  4999.7     .05       0  5096.5     .05       0
Bank Sta=4965.1,5272.5
XS Rating Curve= 0 ,0
Exp/Cntr=0.3,0.1