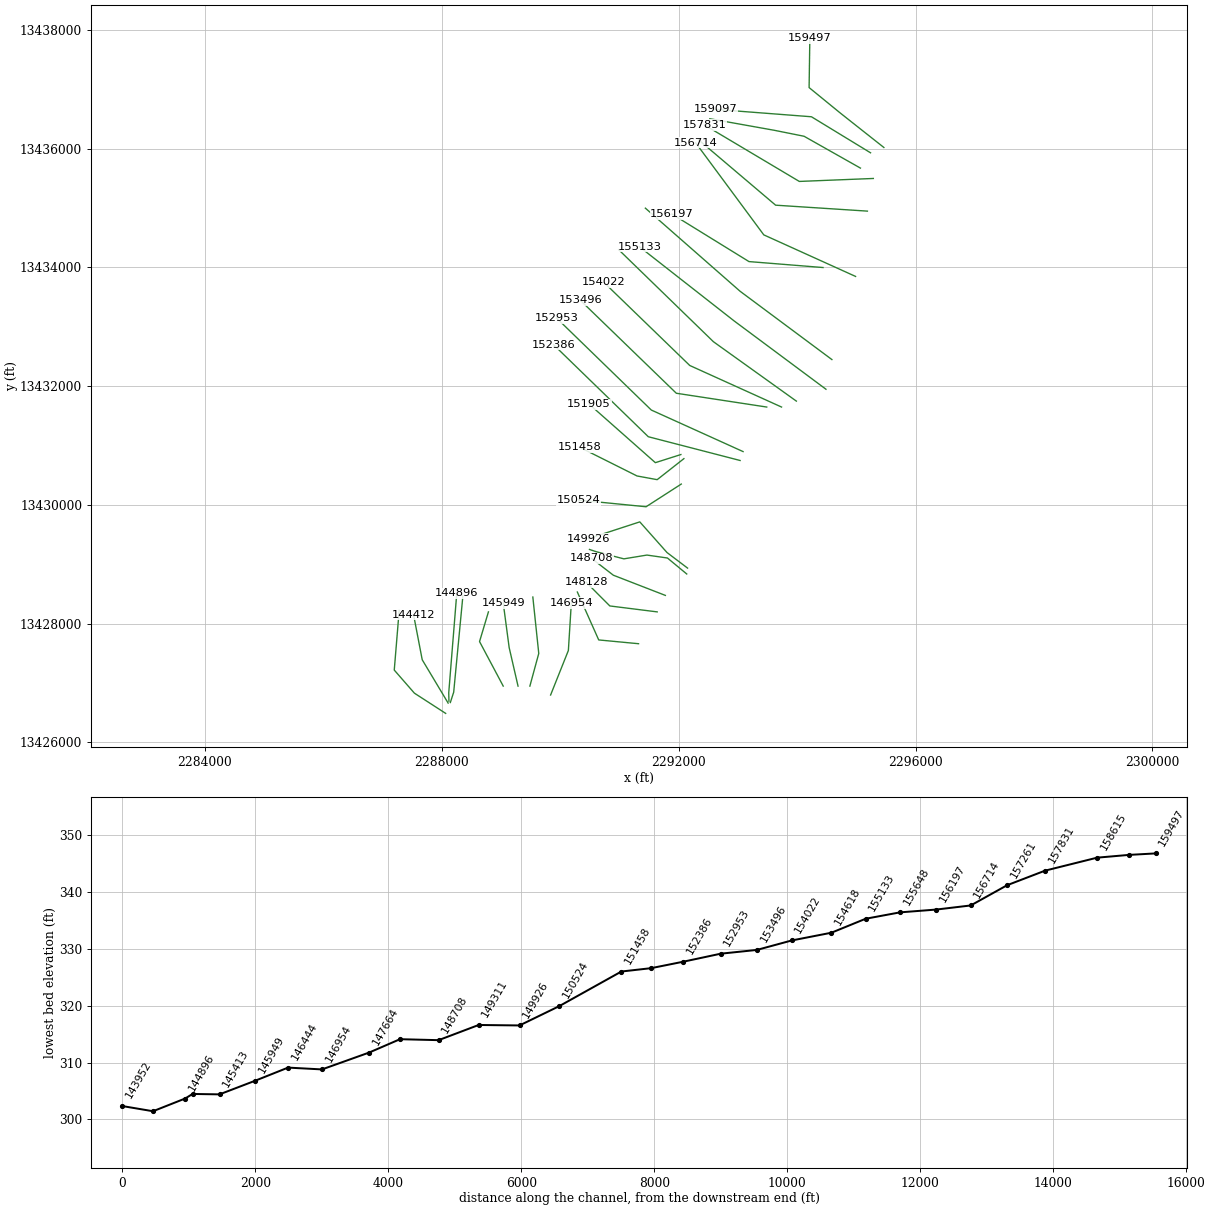
HEC-RAS study SULPHUR CREEK.prj: SULPHUR CREEK Base Level Engineering

--- SULPHUR CREEK.g01 (geometry) --- (continued)

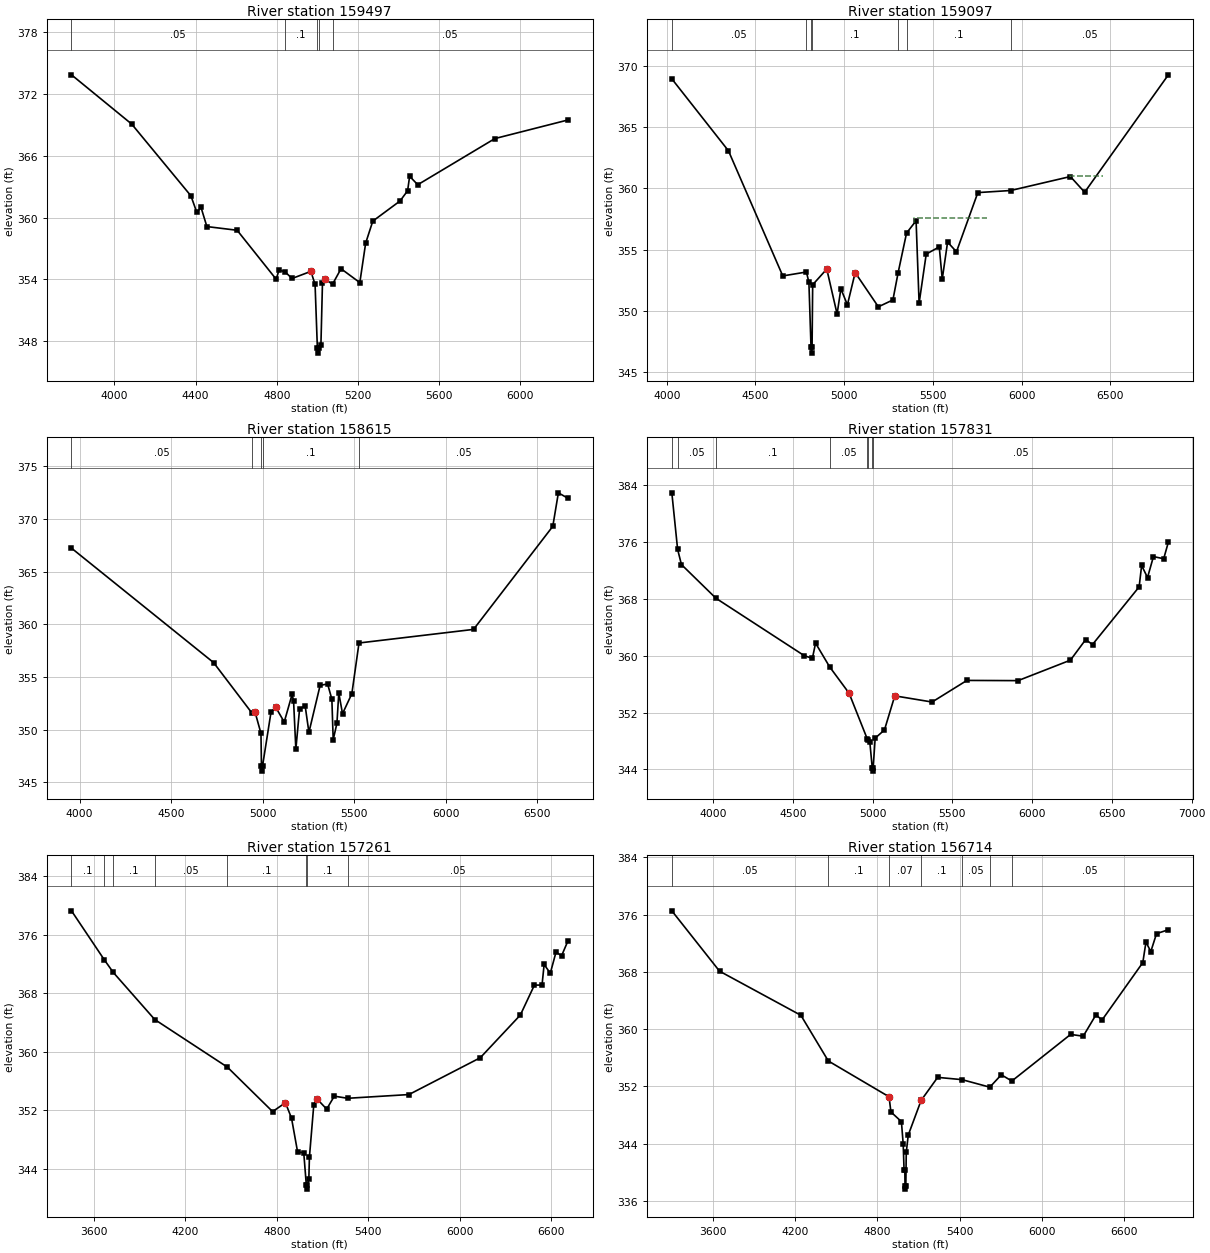
Type RM Length L Ch R = 1 ,159497  ,400,400,400
BEGIN DESCRIPTION:
SULPHUR CREEK 179.0
END DESCRIPTION:
XS GIS Cut Line= 4
      2295465.84      13436018.4      2294735.35     13436594.12
      2294202.97     13437027.46      2294215.35     13437857.02
#Sta/Elev= 30
  3788.9  373.88  4085.5  369.09  4377.3  362.11  4406.2   360.5    4427  360.99
  4455.9  359.12    4605  358.76  4797.2     354  4811.5  354.89  4840.9  354.72
  4875.5  354.07  4968.1  354.76  4988.9  353.51  5000.3  347.31    5003  346.81
  5006.3  347.31  5017.7  347.57  5025.4  353.61  5038.5     354  5074.9  353.51
  5116.8  355.02  5209.4  353.67  5238.2  357.51  5273.3  359.65  5407.6  361.61
  5444.8   362.6  5454.8  364.01  5494.9  363.19  5874.9  367.68  6235.1  369.49
#Mann= 5 ,-1 , 0
  3788.9     .05       0  4840.9      .1       0  5000.3     .07       0
  5006.3      .1       0  5074.9     .05       0
Bank Sta=4968.1,5038.5
XS Rating Curve= 0 ,0
Exp/Cntr=0.3,0.1

Type RM Length L Ch R = 1 ,159097  ,482,482,482
BEGIN DESCRIPTION:
SULPHUR CREEK 178.0
END DESCRIPTION:
XS GIS Cut Line= 3
      2295240.28     13435929.15      2294242.62     13436536.06
      2292617.36     13436660.76
#Sta/Elev= 30
    4029  368.93    4348  363.06  4654.1  352.85  4787.3  353.17  4801.3  352.33
  4813.2  347.05    4816  346.55  4819.2  347.05  4822.6  352.13    4902  353.41
  4960.2  349.74  4981.5   351.8  5018.3  350.49    5062  353.12  5192.7  350.33
  5274.7  350.89  5304.2  353.12  5351.6  356.35  5405.3  357.35  5422.3  350.62
  5462.4  354.63  5535.8  355.22  5552.7  352.59  5582.8  355.61  5632.9  354.82
  5753.3  359.65  5938.3  359.82  6274.8  360.96  6355.1  359.68  6826.8  369.26
#Mann= 7 ,-1 , 0
    4029     .05       0  4787.3      .1       0  4813.2     .07       0
  4819.2      .1       0  5304.2     .05       0  5351.6      .1       0
  5938.3     .05       0
#XS Ineff= 2 ,-1
 5396.04 5807.64  357.54  6274.4  6461.1  360.97
Permanent Ineff=
       T       T
Bank Sta=4902,5062
XS Rating Curve= 0 ,0
Exp/Cntr=0.3,0.1

Type RM Length L Ch R = 1 ,158615  ,784,784,784
BEGIN DESCRIPTION:
SULPHUR CREEK 177.0
END DESCRIPTION:
XS GIS Cut Line= 4
      2295069.79     13435671.46      2294117.92     13436207.67
      2293619.11     13436307.43      2292525.93     13436502.79
#Sta/Elev= 30
    3956  367.22  4732.1  356.36  4941.2  351.58  4958.9  351.64  4990.8  349.64
  4993.5  346.56  4996.3  346.06  4999.5  346.56  5045.8  351.67    5072   352.1
  5117.9  350.72  5160.9  353.35  5168.9  352.72  5181.3  348.13  5201.7  351.97
  5232.3  352.23  5252.7  349.74  5313.9   354.2  5354.7  354.33    5378  352.89
  5385.3  349.05  5405.6  350.59  5415.8  353.48  5436.2  351.51  5487.2  353.41
  5526.2  358.22  6151.8  359.51  6584.6  369.29  6615.1  372.47  6667.7  371.95
#Mann= 5 ,-1 , 0
    3956     .05       0  4941.2      .1       0  4993.5     .07       0
  4999.5      .1       0  5526.2     .05       0
Bank Sta=4958.9,5072
XS Rating Curve= 0 ,0
Exp/Cntr=0.3,0.1

Type RM Length L Ch R = 1 ,157831  ,570,570,570
BEGIN DESCRIPTION:
SULPHUR CREEK 176.0
END DESCRIPTION:
XS GIS Cut Line= 3
      2295287.77     13435496.86      2294037.72     13435446.85
      2292437.74     13436396.84
#Sta/Elev= 30
  3742.1  382.92  3778.2  374.98  3802.2  372.83  4018.5  368.09  4572.8     360
  4622.9  359.64  4642.9  361.77  4730.7  358.45    4853  354.73  4966.5  348.32
  4968.6  348.11  4983.1  347.81    4998  344.27  5000.7  343.77    5004  344.27
  5016.4  348.41  5074.6  349.56  5139.3  354.36  5373.1  353.49  5591.3  356.53
  5911.9   356.5  6240.1  359.38  6335.6  362.27  6378.5  361.58  6670.8  369.69
  6686.4   372.7  6723.4     371  6760.4  373.95  6824.7  373.65  6853.9  375.98
#Mann= 8 ,-1 , 0
  3742.1      .1       0  3778.2     .05       0  4018.5      .1       0
  4730.7     .05       0  4966.5      .1       0  4968.6     .05       0
    4998     .03       0    5004     .05       0
Bank Sta=4853,5139.3
XS Rating Curve= 0 ,0
Exp/Cntr=0.3,0.1

Type RM Length L Ch R = 1 ,157261  ,547,547,547
BEGIN DESCRIPTION:
SULPHUR CREEK 175.0
END DESCRIPTION:
XS GIS Cut Line= 3
      2295187.68     13434946.86      2293637.72     13435046.85
      2292337.73     13436146.84
#Sta/Elev= 30
  3453.9  379.29  3669.4  372.58  3727.9  370.86  3999.7  364.42  4476.4   357.9
  4772.8  351.82  4856.8  353.03  4896.8  350.93  4936.9  346.27    4977  346.21
  4994.1  341.71  4996.8  341.21  5000.1  341.71  5010.4  342.61  5014.2  345.58
  5042.8  352.73  5063.6  353.56  5127.4  352.16  5177.4  353.93  5264.9  353.64
  5666.8  354.15  6134.8  359.19  6397.4  365.03  6489.7  369.13  6539.7  369.13
  6553.4  371.95  6593.9  370.75  6631.4  373.65  6667.7  373.13    6710   375.2
#Mann= 8 ,-1 , 0
  3453.9      .1       0  3669.4     .05       0  3727.9      .1       0
  3999.7     .05       0  4476.4      .1       0  4994.1     .07       0
  5000.1      .1       0  5264.9     .05       0
Bank Sta=4856.8,5063.6
XS Rating Curve= 0 ,0
Exp/Cntr=0.3,0.1

Type RM Length L Ch R = 1 ,156714  ,517,517,517
BEGIN DESCRIPTION:
SULPHUR CREEK 174.0
END DESCRIPTION:
XS GIS Cut Line= 3
      2294987.68     13433846.87      2293437.72     13434546.85
      2292287.73     13436096.84
#Sta/Elev= 30
  3296.4  376.52  3645.3  368.09    4240  361.93  4440.6  355.55  4884.8  350.55
  4898.3  348.43  4975.1  347.08  4988.3  343.92  4994.3  340.39  5000.2  340.39
  5001.4  338.15  5004.1  337.65  5007.4  338.15  5010.6   342.8  5025.2   345.2
  5119.2  350.04  5240.2  353.26  5418.8  352.94  5621.5  351.89  5705.5  353.62
  5782.7  352.75  6212.5  359.26  6304.5  359.01  6398.2  362.01  6441.5  361.25
  6740.3  369.29  6763.3  372.15  6798.8  370.83  6840.5  373.33  6927.1  373.88
#Mann= 7 ,-1 , 0
  3296.4     .05       0  4440.6      .1       0  4884.8     .07       0
  5119.2      .1       0  5418.8     .05       0  5621.5      .1       0
  5782.7     .05       0
Bank Sta=4884.8,5119.2
XS Rating Curve= 0 ,0
Exp/Cntr=0.3,0.1

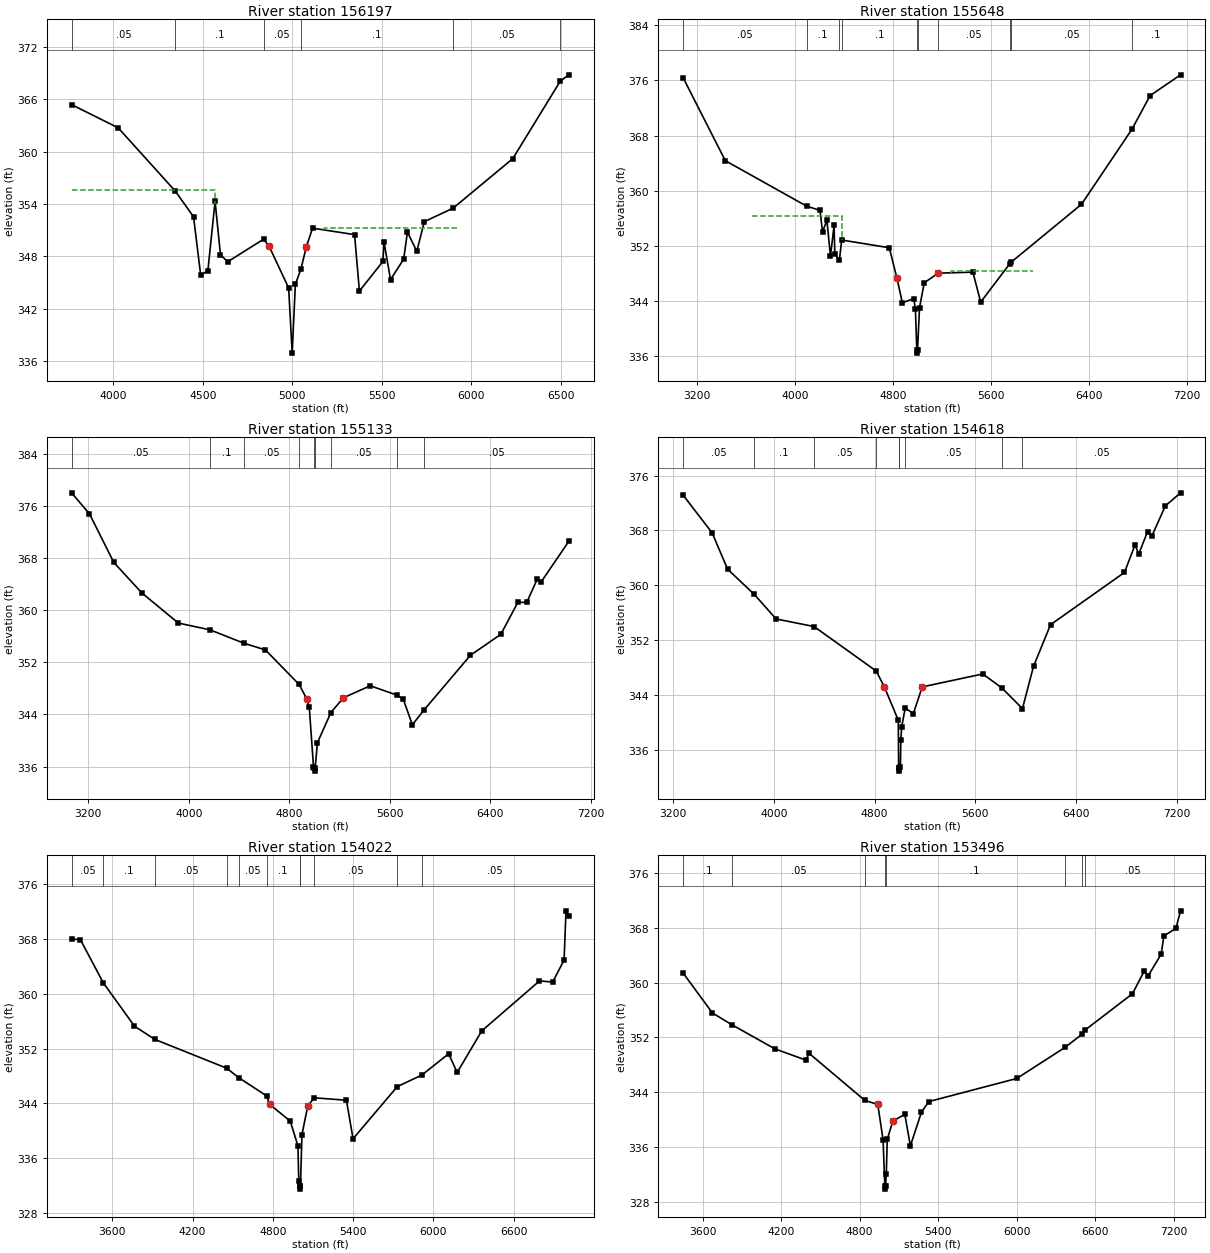
Type RM Length L Ch R = 1 ,156197  ,549,549,549
BEGIN DESCRIPTION:
SULPHUR CREEK 173.0
END DESCRIPTION:
XS GIS Cut Line= 3
      2294437.73     13433996.85      2293187.72     13434096.85
      2291887.75     13434896.84
#Sta/Elev= 30
    3766  365.39  4026.8  362.73    4346  355.49  4448.2  352.54  4488.3  345.83
  4528.4  346.39  4568.6  354.31  4598.7  348.21  4638.8  347.39  4839.4  349.97
  4869.5  349.22  4979.9  344.39  4999.7  336.93  5017.5  344.81    5049  346.58
  5078.7  349.11  5113.9  351.24  5348.4   350.5  5375.6  344.04  5506.9  347.43
  5513.2  349.65  5549.5  345.35  5622.9  347.69  5644.1  350.79  5696.3  348.59
  5738.8  351.99  5899.5  353.53  6233.4  359.21  6498.4  368.07  6546.4   368.8
#Mann= 6 ,-1 , 0
    3766     .05       0    4346      .1       0  4839.4     .05       0
    5049      .1       0  5899.5     .05       0  6498.4      .1       0
#XS Ineff= 2 ,-1
    3766 4569.89355.5865 5178.22 5920.79  351.25
Permanent Ineff=
       T       T
Bank Sta=4869.5,5078.7
XS Rating Curve= 0 ,0
Exp/Cntr=0.3,0.1

Type RM Length L Ch R = 1 ,155648  ,515,515,515
BEGIN DESCRIPTION:
SULPHUR CREEK 172.0
END DESCRIPTION:
XS GIS Cut Line= 3
      2294587.74     13432446.84      2293037.72     13433596.85
      2291437.71     13434996.87
#Sta/Elev= 30
    3091  376.35  3434.3  364.35  4098.9  357.74  4206.3  357.15  4227.1  354.03
  4262.6   355.7  4291.8   350.5    4321  354.95  4327.3  350.84  4364.4  349.88
  4383.3  352.84  4771.7  351.72  4834.3  347.26  4878.1  343.74  4971.2  344.34
  4984.5  342.82  4996.1  336.93  4998.9  336.43  5002.1  336.93  5017.9  343.01
  5056.6  346.64    5171  348.03  5453.4  348.18    5517  343.83  5754.9  349.42
  5764.9  349.62  6338.9  358.02  6750.6  368.91  6898.9   373.8  7147.1  376.81
#Mann= 10 ,-1 , 0
    3091     .05       0  4098.9      .1       0  4364.4     .05       0
  4383.3      .1       0  4996.1     .07       0  5002.1      .1       0
    5171     .05       0  5754.9      .1       0  5764.9     .05       0
  6750.6      .1       0
#XS Ineff= 2 ,-1
 3650.57 4386.36  356.28 5277.23 5942.01  348.38
Permanent Ineff=
       T       T
Bank Sta=4834.3,5171
XS Rating Curve= 0 ,0
Exp/Cntr=0.3,0.1

Type RM Length L Ch R = 1 ,155133  ,515,515,515
BEGIN DESCRIPTION:
SULPHUR CREEK 171.0
END DESCRIPTION:
XS GIS Cut Line= 3
      2294487.73     13431946.85      2292937.72     13433096.85
      2291337.75     13434346.83
#Sta/Elev= 30
  3066.9  377.99  3209.8  374.77  3403.1  367.33  3625.1  362.67  3917.2  358.02
  4170.8  356.97  4438.6  354.93  4610.9   353.9  4878.9  348.61  4939.6  346.41
  4960.4  345.07  4993.8  336.01  5001.2  335.81  5003.9  335.31  5007.2  335.81
    5025  339.67  5132.7   344.3  5232.1  346.56  5445.5   348.4  5657.1  346.98
  5708.7  346.34  5781.1  342.42  5874.6   344.7  6243.2  353.07  6485.6  356.29
  6621.3  361.19  6692.7   361.2  6777.7  364.84  6806.7  364.32  7027.3  370.56
#Mann= 9 ,-1 , 0
  3066.9     .05       0  4170.8      .1       0  4438.6     .05       0
  4878.9      .1       0  5001.2     .07       0  5007.2      .1       0
  5132.7     .05       0  5657.1      .1       0  5874.6     .05       0
#XS Ineff= 1 ,-1
 5468.18 6104.67  348.22
Permanent Ineff=
       T
Bank Sta=4939.6,5232.1
XS Rating Curve= 0 ,0
Exp/Cntr=0.3,0.1

Type RM Length L Ch R = 1 ,154618  ,596,596,596
BEGIN DESCRIPTION:
SULPHUR CREEK 170.0
END DESCRIPTION:
XS GIS Cut Line= 3
      2293987.73     13431746.85      2292587.72     13432746.85
      2290987.75     13434296.83
#Sta/Elev= 30
  3280.7  373.13  3510.5  367.63  3632.2  362.35  3844.5  358.66    4018  355.07
  4319.6  353.96  4813.3  347.46  4878.3  345.11  4987.7  340.29  4990.8  333.35
  4993.5  332.85  4996.8  333.35  5004.7  333.44  5008.2  337.44  5015.2  339.35
    5043  342.07  5107.3  341.25    5178  345.15  5658.8  347.04  5810.3     345
  5973.6  341.98  6061.9  348.17  6196.4  354.23  6783.3  361.86  6868.1  365.91
  6896.4  364.52  6967.1  367.84  7002.6  367.25  7108.6  371.59  7228.8  373.49
#Mann= 9 ,-1 , 0
  3280.7     .05       0  3844.5      .1       0  4319.6     .05       0
  4813.3      .1       0  4990.8     .07       0  4996.8      .1       0
    5043     .05       0  5810.3      .1       0  5973.6     .05       0
#XS Ineff= 1 ,-1
 5659.12 6104.67  346.51
Permanent Ineff=
       T
Bank Sta=4878.3,5178
XS Rating Curve= 0 ,0
Exp/Cntr=0.3,0.1

Type RM Length L Ch R = 1 ,154022  ,526,526,526
BEGIN DESCRIPTION:
SULPHUR CREEK 169.0
END DESCRIPTION:
XS GIS Cut Line= 3
       2293737.7     13431646.86      2292187.72     13432346.85
      2290737.71     13433746.87
#Sta/Elev= 30
  3295.8  367.96  3361.8  367.91  3533.2  361.59  3765.8  355.28  3916.7  353.35
  4454.7  349.14  4545.9  347.75  4753.3   345.1  4777.1  343.85  4930.5  341.41
  4987.7   337.8  4993.8  332.72  5000.6  331.99  5003.3  331.49  5006.6  331.99
  5017.7  339.42  5060.2  343.55  5107.8  344.82  5350.1  344.46  5399.6  338.84
  5730.8  346.46  5913.2  348.13  6113.9  351.24  6177.7  348.51  6361.4  354.58
  6792.8  361.87  6891.8  361.71  6976.7  364.93  6990.9   372.1  7012.1  371.28
#Mann= 11 ,-1 , 0
  3295.8     .05       0  3533.2      .1       0  3916.7     .05       0
  4454.7      .1       0  4545.9     .05       0  4753.3      .1       0
  5000.6     .07       0  5006.6      .1       0  5107.8     .05       0
  5730.8      .1       0  5913.2     .05       0
#XS Ineff= 1 ,-1
 5285.01 5819.66  344.33
Permanent Ineff=
       T
Bank Sta=4777.1,5060.2
XS Rating Curve= 0 ,0
Exp/Cntr=0.3,0.1

Type RM Length L Ch R = 1 ,153496  ,543,543,543
BEGIN DESCRIPTION:
SULPHUR CREEK 168.0
END DESCRIPTION:
XS GIS Cut Line= 3
      2293487.74     13431646.85      2291960.78     13431879.37
       2290337.7     13433446.88
#Sta/Elev= 30
  3452.8  361.37  3675.4  355.57  3823.8  353.85  4153.1  350.32  4393.5  348.65
  4412.4   349.7    4841  342.78  4939.8  342.19  4980.2     337  4993.4  330.32
  4996.1  329.82  4999.4  330.32  5004.8  332.04    5012  337.09  5054.4  339.75
  5146.2  340.76  5188.7  336.14  5273.6  341.07  5330.2  342.62  6002.1  345.99
  6369.8  350.52  6501.8  352.46  6525.1  353.08    6886  358.37  6977.9  361.74
  7006.2  360.99  7105.2  364.14  7126.6  366.82  7218.4  367.93  7253.8  370.49
#Mann= 8 ,-1 , 0
  3452.8      .1       0  3823.8     .05       0    4841      .1       0
  4993.4     .07       0  4999.4      .1       0  6369.8     .05       0
  6501.8      .1       0  6525.1     .05       0
Bank Sta=4939.8,5054.4
XS Rating Curve= 0 ,0
Exp/Cntr=0.3,0.1

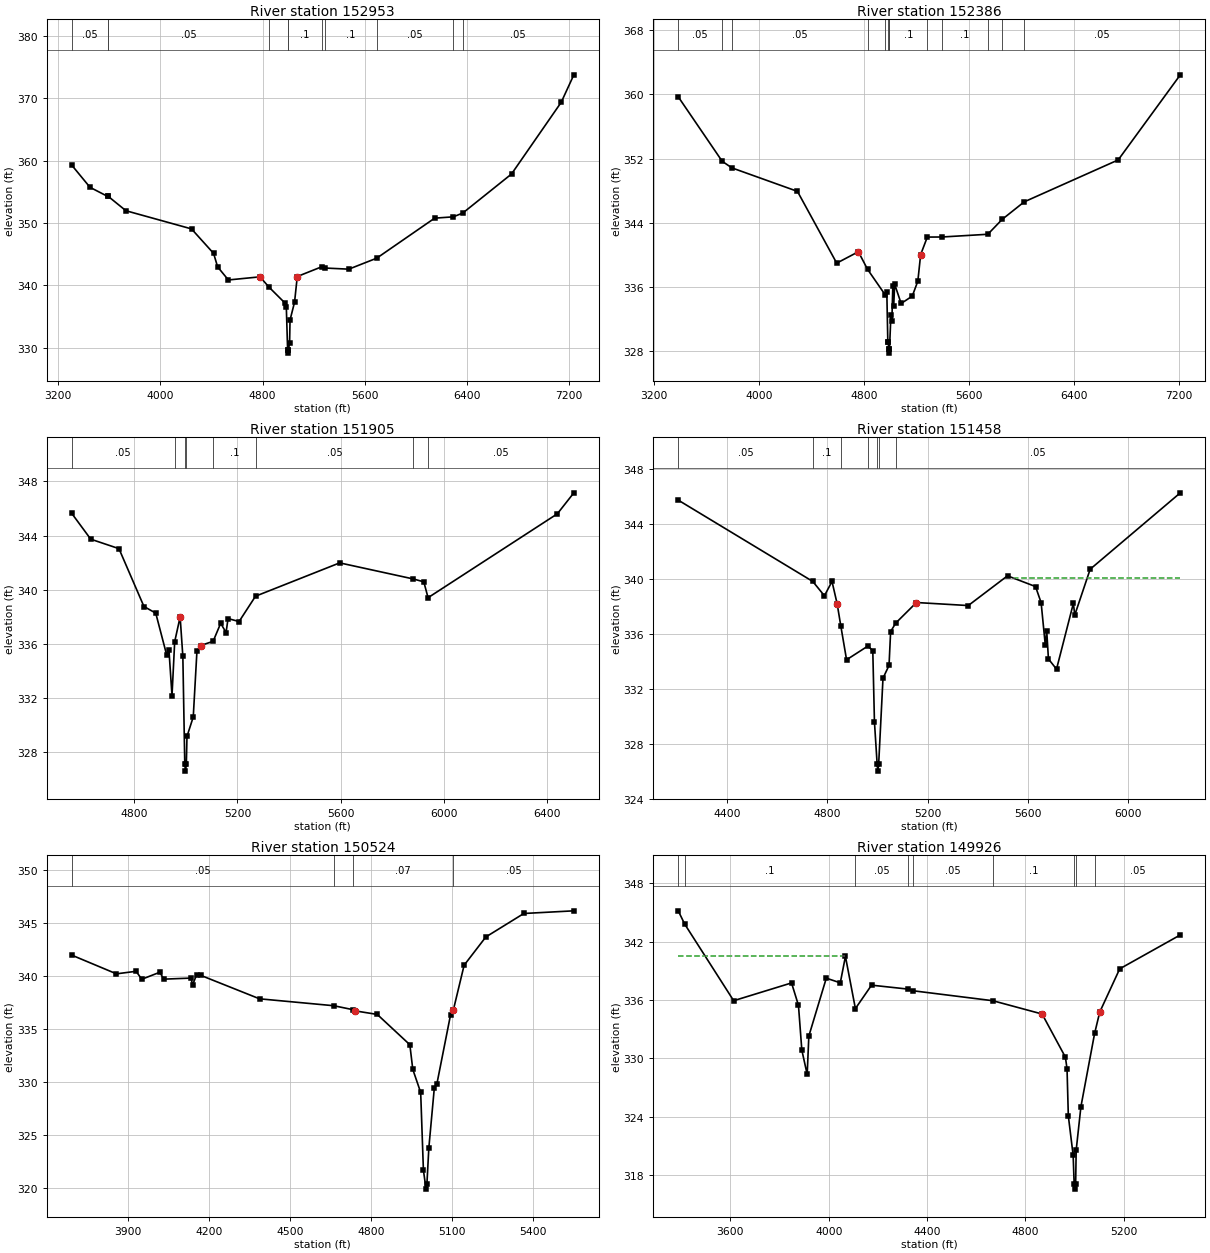
Type RM Length L Ch R = 1 ,152953  ,567,567,567
BEGIN DESCRIPTION:
SULPHUR CREEK 167.0
END DESCRIPTION:
XS GIS Cut Line= 3
      2293087.73     13430896.85      2291537.72     13431596.85
      2289937.73     13433146.85
#Sta/Elev= 30
  3307.3  359.27    3450  355.72  3587.7  354.27  3591.4  354.29  3731.1  351.97
  4244.1  349.06  4416.9  345.14  4448.4  342.98  4532.5  340.88  4780.2  341.38
  4848.6  339.77  4976.1  337.17  4986.1  336.48  4996.2  329.66    4999  329.16
  5002.2  329.66  5011.5  330.76  5015.1  334.46  5050.4  337.32  5071.7  341.43
    5264     343  5290.3  342.79  5474.8  342.61  5693.4  344.37  6146.7  350.78
  6291.8  350.99  6366.1  351.59  6747.9  357.85  7136.8  369.34  7235.7  373.74
#Mann= 11 ,-1 , 0
  3307.3     .05       0  3587.7      .1       0  3591.4     .05       0
  4848.6      .1       0  4996.2     .07       0  5002.2      .1       0
    5264     .05       0  5290.3      .1       0  5693.4     .05       0
  6291.8      .1       0  6366.1     .05       0
Bank Sta=4780.2,5071.7
XS Rating Curve= 0 ,0
Exp/Cntr=0.3,0.1

Type RM Length L Ch R = 1 ,152386  ,481,481,481
BEGIN DESCRIPTION:
SULPHUR CREEK 166.0
END DESCRIPTION:
XS GIS Cut Line= 3
      2293037.75     13430746.85      2291487.72     13431146.85
       2289887.7     13432696.87
#Sta/Elev= 30
  3383.6   359.7  3718.8  351.66  3792.4  350.84  4292.5  347.91    4592  338.96
  4757.2  340.38  4827.5  338.18  4963.3  334.97  4974.1  335.37  4981.8  329.08
  4985.6  329.08  4988.5  328.24  4991.2  327.74  4994.5  328.24  5005.6  332.55
  5012.6  331.75  5019.8  336.07  5026.7  333.66  5033.9  336.33  5083.3  333.93
  5168.2  334.85  5210.7  336.72    5232  340.02  5282.9  342.21    5395  342.22
  5744.3  342.56    5854  344.42  6021.6   346.6  6738.4  351.83  7212.1  362.44
#Mann= 13 ,-1 , 0
  3383.6     .05       0  3718.8      .1       0  3792.4     .05       0
  4827.5      .1       0  4963.3     .12       0  4985.6      .1       0
  4988.5     .07       0  4994.5      .1       0  5282.9     .05       0
    5395      .1       0  5744.3     .05       0    5854      .1       0
  6021.6     .05       0
Bank Sta=4757.2,5232
XS Rating Curve= 0 ,0
Exp/Cntr=0.3,0.1

Type RM Length L Ch R = 1 ,151905  ,447,447,447
BEGIN DESCRIPTION:
SULPHUR CREEK 165.0
END DESCRIPTION:
XS GIS Cut Line= 3
      2292037.68     13430846.84      2291606.61      13430710.1
      2290487.71     13431696.86
#Sta/Elev= 30
  4558.6  345.63    4632  343.73  4741.3  343.03  4838.1  338.76  4883.8  338.27
  4925.7  335.21  4934.9  335.55  4946.7  332.18  4957.1  336.16  4978.2  337.99
  4988.7  335.08  4996.2  327.11  4998.9  326.61  5002.2  327.11  5004.7  329.17
    5029  330.61  5043.2  335.44  5057.4  335.88  5105.9  336.19  5135.2  337.52
  5156.1  336.84  5163.7  337.87  5206.4  337.65  5270.1  339.52    5596  341.98
  5881.8  340.79  5921.7  340.58  5938.2  339.41  6438.7   345.6  6502.7  347.15
#Mann= 8 ,-1 , 0
  4558.6     .05       0  4957.1     .12       0  4996.2     .07       0
  5002.2     .12       0  5105.9      .1       0  5270.1     .05       0
  5881.8      .1       0  5938.2     .05       0
#XS Ineff= 1 ,-1
  5617.4 6232.67  341.36
Permanent Ineff=
       T
Bank Sta=4978.2,5057.4
XS Rating Curve= 0 ,0
Exp/Cntr=0.3,0.1

Type RM Length L Ch R = 1 ,151458  ,934,934,934
BEGIN DESCRIPTION:
SULPHUR CREEK 164.0
END DESCRIPTION:
XS GIS Cut Line= 4
      2292088.66     13430777.92      2291637.26     13430423.75
      2291296.98     13430486.25      2290326.78     13430970.57
#Sta/Elev= 30
    4205  345.71  4742.1   339.8  4788.5  338.76  4818.8   339.8  4839.3  338.18
    4854  336.56  4876.9  334.11  4962.2  335.11  4981.6  334.77  4988.2  329.59
    4999  326.52  5001.7  326.02    5005  326.52  5022.3  332.77  5046.4   333.7
  5052.8  336.16  5073.3  336.78  5155.8  338.27  5362.7  338.05  5519.3  340.21
  5631.2  339.43  5653.5  338.26  5670.3  335.15  5675.9  336.21  5682.7  334.17
    5715  333.43  5782.2  338.21  5787.8  337.36  5849.3  340.69  6209.1  346.24
#Mann= 7 ,-1 , 0
    4205     .05       0  4742.1      .1       0    4854     .12       0
  4962.2      .1       0    4999     .07       0    5005      .1       0
  5073.3     .05       0
#XS Ineff= 2 , 0
                         5542.61          340.08
Permanent Ineff=
       T       T
Bank Sta=4839.3,5155.8
XS Rating Curve= 0 ,0
Exp/Cntr=0.3,0.1

Type RM Length L Ch R = 1 ,150524  ,598,598,598
BEGIN DESCRIPTION:
Mapping XS 6827378b
END DESCRIPTION:
XS GIS Cut Line= 3
      2292044.31     13430349.75      2291449.89     13429967.63
      2290303.51     13430080.85
#Sta/Elev= 30
    3693  341.95  3858.4  340.19  3931.1  340.43  3952.2  339.68  4018.9  340.34
  4033.7  339.69  4133.8  339.79  4140.7  339.17    4155   340.1  4170.2  340.05
  4388.1  337.84  4662.7  337.19  4733.4  336.82  4743.2   336.7  4823.9  336.37
  4944.5  333.52  4955.4   331.2  4984.6  329.03  4994.7  321.72  5004.5  319.93
  5007.7  320.43  5014.8  323.81  5034.9   329.4  5044.9  329.87  5095.2  336.34
  5105.2  336.75  5145.4     341  5225.8  343.66  5366.5  345.87  5551.6  346.12
#Mann= 4 ,-1 , 0
    3693     .05       0  4662.7      .1       0  4733.4     .07       0
  5105.2     .05       0
Bank Sta=4743.2,5105.2
XS Rating Curve= 0 ,0
Exp/Cntr=0.3,0.1

Type RM Length L Ch R = 1 ,149926  ,615,615,615
BEGIN DESCRIPTION:
SULPHUR CREEK 163.0
END DESCRIPTION:
XS GIS Cut Line= 4
      2292150.48     13428934.47       2291803.7     13429196.32
      2291343.75     13429712.88      2290473.41     13429429.84
#Sta/Elev= 30
  3388.1  345.17  3414.2  343.81  3613.5  335.92  3848.8  337.75  3876.9  335.45
  3890.6  330.84  3912.4  328.33  3919.1  332.28  3990.1  338.24    4047  337.76
  4067.9  340.48  4108.4  335.11  4174.1  337.52  4324.1  337.11  4344.1  336.94
    4667  335.92  4867.6  334.55  4962.3  330.11  4968.9  328.91  4974.2  324.06
  4993.8  320.01  4997.9  317.03  5000.6  316.53  5003.9  317.03  5006.1  320.54
  5025.4  325.02  5081.1  332.56  5101.9  334.75  5183.1   339.2  5429.5  342.69
#Mann= 9 ,-1 , 0
  3388.1     .05       0  3414.2      .1       0  4108.4     .05       0
  4324.1      .1       0  4344.1     .05       0    4667      .1       0
  4997.9     .07       0  5003.9      .1       0  5081.1     .05       0
#XS Ineff= 1 ,-1
 3388.97 4067.89  340.51
Permanent Ineff=
       T
Bank Sta=4867.6,5101.9
XS Rating Curve= 0 ,0
Exp/Cntr=0.3,0.1

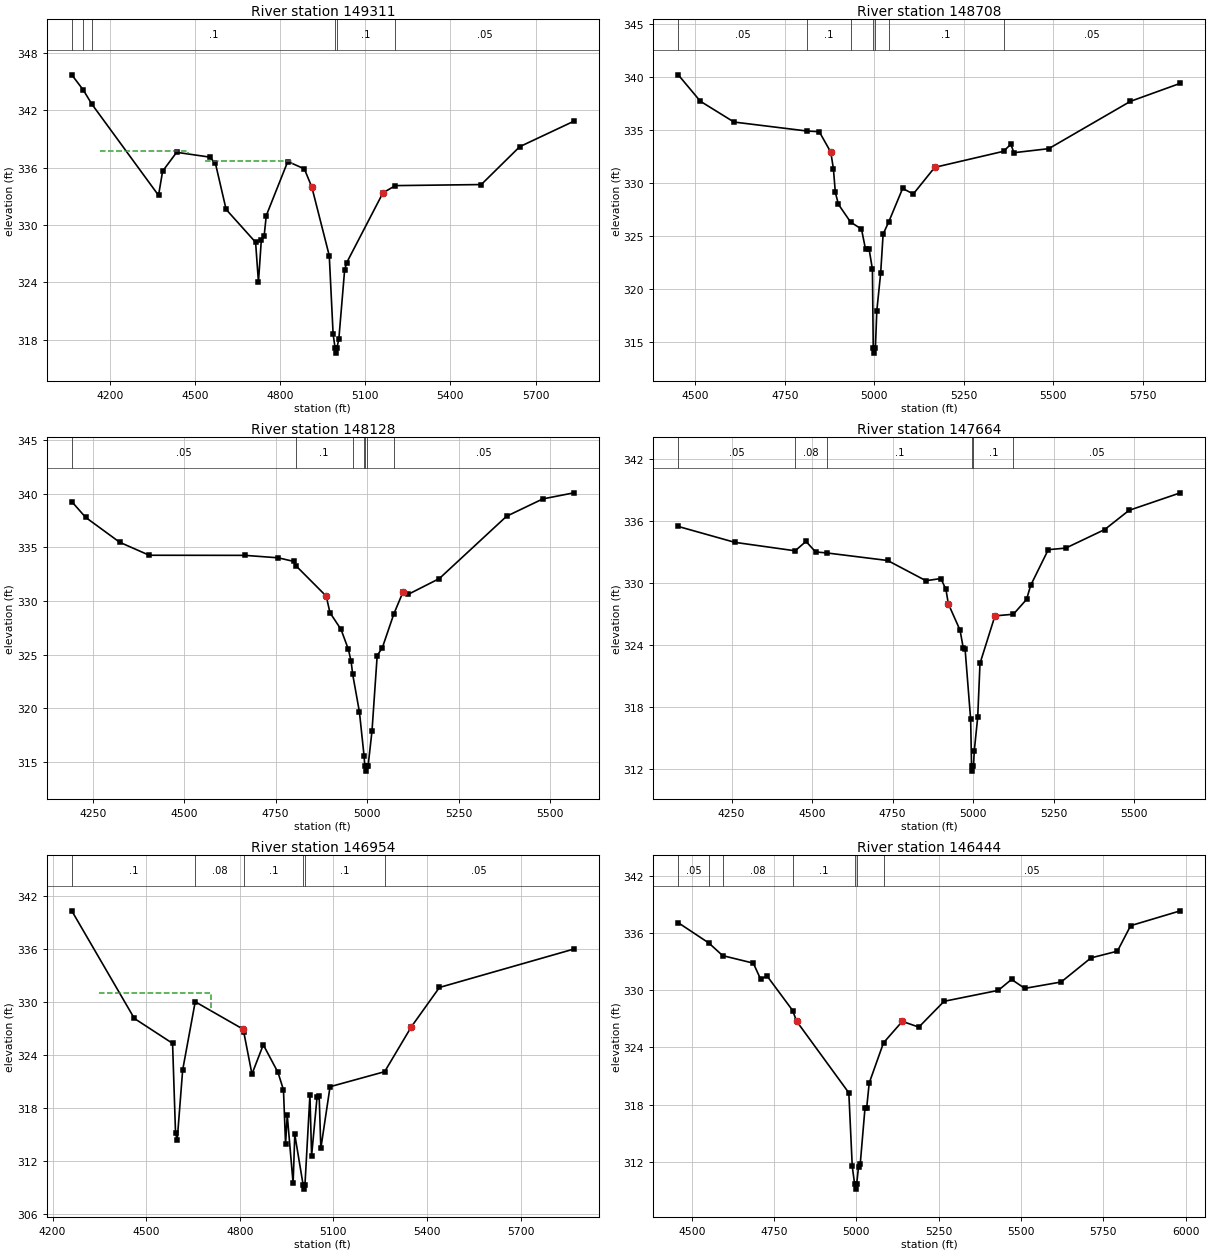
Type RM Length L Ch R = 1 ,149311  ,603,603,603
BEGIN DESCRIPTION:
SULPHUR CREEK 162.0
END DESCRIPTION:
XS GIS Cut Line= 6
      2292136.31     13428835.41      2291810.78     13429104.32
      2291464.04     13429153.86      2291074.85     13429090.17
      2290607.82     13429210.47       2290494.2     13429248.33
#Sta/Elev= 30
  4066.1   345.7  4106.3  344.13    4137  342.63  4371.8   333.1  4386.2  335.63
  4435.6   337.6    4552   337.1  4572.2  336.45  4609.9  331.63  4713.7   328.2
  4723.8  324.04  4733.9  328.43    4744   328.9  4751.4  330.99  4827.1  336.64
  4885.5  335.87  4911.9  333.96  4973.3   326.8  4986.9  318.58    4994  317.11
  4996.7  316.61    5000  317.11  5007.1  318.11  5027.4  325.29  5034.6  326.06
  5162.4  333.36    5206  334.12  5508.8  334.23  5644.4  338.19    5835  340.85
#Mann= 6 ,-1 , 0
  4066.1      .1       0  4106.3     .05       0    4137      .1       0
    4994     .07       0    5000      .1       0    5206     .05       0
#XS Ineff= 2 ,-1
  4166.9 4475.25  337.79 4534.65    4843   336.7
Permanent Ineff=
       T       T
Bank Sta=4911.9,5162.4
XS Rating Curve= 0 ,0
Exp/Cntr=0.3,0.1

Type RM Length L Ch R = 1 ,148708  ,580,580,580
BEGIN DESCRIPTION:
SULPHUR CREEK 161.0
END DESCRIPTION:
XS GIS Cut Line= 3
      2291775.36     13428474.55      2290897.94      13428814.2
      2290531.32     13429096.22
#Sta/Elev= 30
  4452.1  340.17  4513.9  337.68  4607.9  335.72  4812.7  334.87  4846.3  334.81
  4878.5  332.88  4885.8  331.33  4891.2  329.09  4899.9  327.96  4933.9  326.29
  4964.3  325.63  4975.7  323.72  4985.7  323.73  4994.9  321.84  4997.2  314.44
    5000  313.94  5003.2  314.44  5007.2  317.95  5017.9  321.47  5024.8  325.16
  5040.5  326.31  5079.3  329.46  5109.2  328.94  5169.1  331.45  5361.3  332.96
  5381.8  333.63  5390.4  332.83  5487.7  333.21    5716  337.67  5855.5  339.37
#Mann= 7 ,-1 , 0
  4452.1     .05       0  4812.7      .1       0  4933.9     .12       0
  4997.2     .07       0  5003.2     .12       0  5040.5      .1       0
  5361.3     .05       0
Bank Sta=4878.5,5169.1
XS Rating Curve= 0 ,0
Exp/Cntr=0.3,0.1

Type RM Length L Ch R = 1 ,148128  ,464,464,464
BEGIN DESCRIPTION:
SULPHUR CREEK 160.0
END DESCRIPTION:
XS GIS Cut Line= 3
      2291637.76     13428196.85      2290837.72     13428296.85
      2290437.69     13428696.89
#Sta/Elev= 30
  4192.9  339.28  4230.7  337.81    4324  335.48  4404.6  334.27  4666.6  334.26
  4757.3  334.03  4800.1  333.69  4804.9  333.31  4888.3  330.45  4898.4  328.91
  4928.6  327.35  4948.8  325.48  4956.3  324.35  4960.6  323.14    4979  319.63
  4991.7   315.5  4993.7  314.61  4996.4  314.11  4999.7  314.61  5002.7  314.61
  5013.3  317.85  5027.5   324.9  5041.6  325.64  5073.2  328.81  5098.2  330.85
  5112.3  330.62  5197.2  332.09    5381  337.91    5480  339.53  5564.9   340.1
#Mann= 7 ,-1 , 0
  4192.9     .05       0  4804.9      .1       0  4960.6     .12       0
  4991.7      .1       0  4993.7     .07       0  4999.7      .1       0
  5073.2     .05       0
Bank Sta=4888.3,5098.2
XS Rating Curve= 0 ,0
Exp/Cntr=0.3,0.1

Type RM Length L Ch R = 1 ,147664  ,710,710,710
BEGIN DESCRIPTION:
SULPHUR CREEK 159.0
END DESCRIPTION:
XS GIS Cut Line= 3
      2291322.53     13427660.77      2290650.27     13427724.45
      2290289.39     13428531.14
#Sta/Elev= 30
  4084.5  335.48  4260.1  333.94  4447.5  333.12  4481.1  334.03  4511.2  333.01
  4546.5  332.91  4734.7  332.18  4853.6  330.22    4900  330.43  4915.8  329.37
  4923.2  327.98  4959.6  325.42  4969.6  323.68  4975.1  323.64  4992.5  316.77
  4995.3  312.26    4998  311.76  5001.3  312.26  5003.8  313.75  5014.4  316.99
  5021.5   322.2  5067.9  326.81  5125.2  326.97  5166.2  328.41  5178.7  329.76
  5233.5  333.23  5287.6  333.38  5408.7  335.18  5484.2  337.04  5643.5  338.74
#Mann= 6 ,-1 , 0
  4084.5     .05       0  4447.5     .08       0  4546.5      .1       0
  4995.3     .07       0  5001.3      .1       0  5125.2     .05       0
Bank Sta=4923.2,5067.9
XS Rating Curve= 0 ,0
Exp/Cntr=0.3,0.1

Type RM Length L Ch R = 1 ,146954  ,510,510,510
BEGIN DESCRIPTION:
SULPHUR CREEK 158.0
END DESCRIPTION:
XS GIS Cut Line= 3
      2289837.71     13426796.82      2290137.72     13427546.85
      2290187.72     13428346.88
#Sta/Elev= 30
  4261.6  340.31  4462.2  328.12  4584.7   325.3  4594.2  315.13  4599.6  314.37
  4617.1  322.29  4657.3  330.01  4809.6  326.93  4812.6  326.64  4839.2  321.82
  4875.5  325.14  4922.7     322  4940.2  320.03  4946.9  313.88  4952.3  317.17
  4971.1  309.43  4976.5  314.98  5003.1  309.29  5005.9  308.79  5009.1  309.29
    5025  319.42  5030.4  312.58  5047.9  319.22  5054.6  319.37    5060   313.4
  5089.5  320.39  5264.5  322.09    5350  327.17  5440.1  331.63    5871  335.98
#Mann= 6 ,-1 , 0
  4261.6      .1       0  4657.3     .08       0  4812.6      .1       0
  5003.1     .07       0  5009.1      .1       0  5264.5     .05       0
#XS Ineff= 1 ,-1
 4350.21 4709.19  331.04
Permanent Ineff=
       T
Bank Sta=4809.6,5350
XS Rating Curve= 0 ,0
Exp/Cntr=0.3,0.1

Type RM Length L Ch R = 1 ,146444  ,495,495,495
BEGIN DESCRIPTION:
SULPHUR CREEK 157.0
END DESCRIPTION:
XS GIS Cut Line= 3
      2289487.71     13426946.82      2289637.72     13427496.85
      2289537.72     13428446.88
#Sta/Elev= 30
  4458.6  337.11  4551.5  334.98  4593.6  333.65  4686.7  332.86  4709.1  331.16
  4728.1  331.53  4806.3  327.88    4818  326.77  4976.9  319.23  4987.3   311.5
  4994.6  309.61  4997.4  309.11  5000.6  309.61  5006.3  311.45  5011.5  311.73
  5026.1  317.67  5031.2  317.67  5038.8  320.26  5082.3  324.49  5139.3  326.74
  5189.6  326.14  5266.3  328.85  5430.9     330  5471.2  331.15  5511.4  330.21
    5622  330.88  5712.5  333.41  5792.9  334.12  5833.1   336.8    5984  338.36
#Mann= 7 ,-1 , 0
  4458.6     .05       0  4551.5      .1       0  4593.6     .08       0
  4806.3      .1       0  4994.6     .07       0  5000.6      .1       0
  5082.3     .05       0
Bank Sta=4818,5139.3
XS Rating Curve= 0 ,0
Exp/Cntr=0.3,0.1

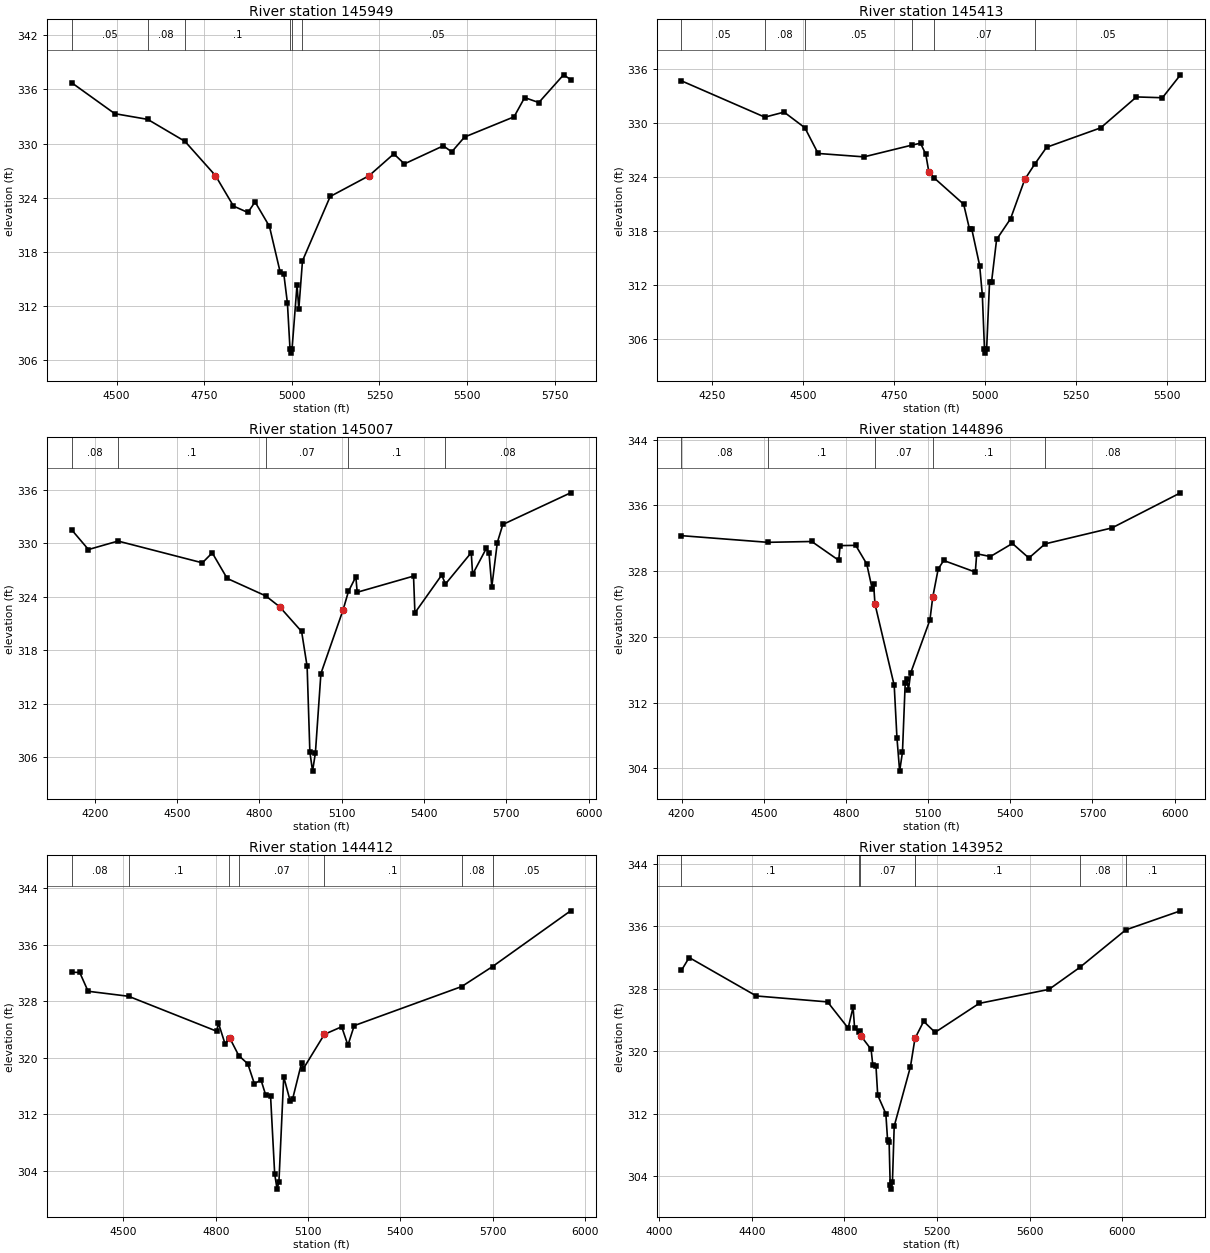
Type RM Length L Ch R = 1 ,145949  ,536,536,536
BEGIN DESCRIPTION:
SULPHUR CREEK 156.0
END DESCRIPTION:
XS GIS Cut Line= 3
      2289287.71     13426946.88      2289137.72     13427596.85
      2289037.72     13428346.86
#Sta/Elev= 30
  4371.7  336.74  4494.8  333.31  4588.7  332.68  4694.9  330.25  4782.2  326.45
  4833.5  323.08  4874.6  322.37  4895.1  323.54  4936.1  320.83  4966.9  315.74
  4977.2  315.54  4987.4  312.34  4994.7   307.3  4997.5   306.8  5000.7   307.3
  5014.8  314.35  5019.9  311.68  5030.4  317.02  5109.4  324.14  5220.4  326.44
    5291  328.86  5321.2  327.75  5432.2  329.75  5456.2  329.08  5492.7  330.72
    5634  332.96  5664.2  335.09  5704.6  334.54  5775.2  337.61  5795.4  337.09
#Mann= 6 ,-1 , 0
  4371.7     .05       0  4588.7     .08       0  4694.9      .1       0
  4994.7     .07       0  5000.7      .1       0  5030.4     .05       0
Bank Sta=4782.2,5220.4
XS Rating Curve= 0 ,0
Exp/Cntr=0.3,0.1

Type RM Length L Ch R = 1 ,145413  ,406,406,406
BEGIN DESCRIPTION:
SULPHUR CREEK 155.0
END DESCRIPTION:
XS GIS Cut Line= 3
       2289037.7     13426946.89      2288637.72     13427696.85
      2288787.73     13428196.88
#Sta/Elev= 30
  4165.1   334.7  4394.3  330.66  4447.3  331.22  4504.4  329.48  4540.8  326.62
  4666.9  326.24  4799.8  327.56  4822.4  327.76  4836.9  326.53  4845.1   324.6
  4858.9  323.93    4941  320.97  4957.3  318.17    4963  318.26    4985  314.14
  4992.4  310.83  4998.2   304.9    5001   304.4  5004.2   304.9  5012.2  312.33
  5017.7  312.33  5031.6  317.05  5069.9  319.35    5109  323.73    5136  325.41
  5169.1  327.31  5317.8  329.47  5416.1  332.91  5487.5  332.82  5537.1  335.37
#Mann= 6 ,-1 , 0
  4165.1     .05       0  4394.3     .08       0  4504.4     .05       0
  4799.8      .1       0  4858.9     .07       0    5136     .05       0
Bank Sta=4845.1,5109
XS Rating Curve= 0 ,0
Exp/Cntr=0.3,0.1

Type RM Length L Ch R = 1 ,145007  ,111,111,111
BEGIN DESCRIPTION:
Mapping XS 095a7359
END DESCRIPTION:
XS GIS Cut Line= 3
      2288144.73      13426670.6      2288201.18     13426844.45
      2288357.23     13428472.81
#Sta/Elev= 30
    4116  331.54  4177.3  329.32  4285.1  330.27  4592.5  327.83  4628.5  328.95
  4682.9  326.08  4823.6  324.12  4873.8  322.91  4954.2  320.13  4974.3  316.21
  4984.3  306.62  4994.1  304.47  5004.4  306.49  5024.5  315.41  5104.9  322.51
    5125  324.63  5151.8  326.26  5156.8  324.53  5362.1  326.34  5367.1  322.22
  5464.8  326.46  5478.4  325.45  5572.4  328.97  5577.4  326.54  5627.2  329.44
  5637.3  328.88  5647.3  325.13  5667.4   330.1  5687.5  332.13  5934.6  335.68
#Mann= 5 ,-1 , 0
    4116     .08       0  4285.1      .1       0  4823.6     .07       0
    5125      .1       0  5478.4     .08       0
Bank Sta=4873.8,5104.9
XS Rating Curve= 0 ,0
Exp/Cntr=0.3,0.1

Type RM Length L Ch R = 1 ,144896  ,484,484,484
BEGIN DESCRIPTION:
SULPHUR CREEK 154.0
END DESCRIPTION:
XS GIS Cut Line= 3
      2288120.87     13426692.36      2288117.69     13426835.47
      2288253.14     13428508.35
#Sta/Elev= 30
  4199.6  332.31  4514.4   331.5  4675.2   331.6  4773.7  329.31  4778.7   331.1
  4835.7  331.13  4875.9  328.87  4895.8  325.84  4900.8  326.48    4906  323.99
  4976.2   314.1  4986.2  307.72    4996  303.67  5006.3  305.96  5016.3  314.36
    5023  314.88    5028  313.53  5036.4  315.62  5106.6  322.06  5116.7   324.8
  5136.7  328.25  5156.8  329.29  5272.3  327.88  5277.3  330.11  5327.3  329.77
  5407.6  331.36  5467.8  329.59  5526.9  331.31  5770.9  333.25  6021.1  337.52
#Mann= 5 ,-1 , 0
  4199.6     .08       0  4514.4      .1       0    4906     .07       0
  5116.7      .1       0  5526.9     .08       0
Bank Sta=4906,5116.7
XS Rating Curve= 0 ,0
Exp/Cntr=0.3,0.1

Type RM Length L Ch R = 1 ,144412  ,460,460,460
BEGIN DESCRIPTION:
SULPHUR CREEK 153.0
END DESCRIPTION:
XS GIS Cut Line= 3
      2288107.32     13426661.15      2287669.81     13427390.33
      2287523.99     13428147.24
#Sta/Elev= 30
  4331.8  332.09  4358.1  332.06  4385.3   329.4    4517  328.69  4803.2  323.75
    4809  324.87  4830.4  321.95  4844.3  322.67  4845.9  322.76  4874.9   320.3
  4904.2  319.14  4925.6  316.32    4947  316.87  4962.5  314.71  4978.1  314.65
  4991.5   303.6  4999.2  301.43  5005.3  302.44  5020.9  317.31  5042.2  313.83
  5049.8  314.17  5079.2  319.32    5085  318.48    5153  323.31  5209.2  324.38
  5229.5  321.77  5249.9  324.54  5599.3  330.07  5699.2  332.89    5953  340.77
#Mann= 7 ,-1 , 0
  4331.8     .08       0    4517      .1       0  4844.3     .12       0
  4874.9     .07       0    5153      .1       0  5599.3     .08       0
  5699.2     .05       0
Bank Sta=4845.9,5153
XS Rating Curve= 0 ,0
Exp/Cntr=0.3,0.1

Type RM Length L Ch R = 1 ,143952  ,593,593,593
BEGIN DESCRIPTION:
SULPHUR CREEK 152.0
END DESCRIPTION:
XS GIS Cut Line= 4
      2288065.68     13426487.53      2287537.87     13426827.83
      2287197.59     13427216.72      2287280.85     13428222.73
#Sta/Elev= 30
  4096.5  330.35  4129.8  331.99  4419.7  327.07  4727.2  326.31  4816.2  322.95
  4837.4  325.64    4844  322.92  4864.3   322.5  4865.9  322.53  4872.5  321.91
  4915.2  320.23  4922.5  318.22  4936.1  318.15  4943.7  314.37  4978.8     312
  4986.4  308.59    4993  308.35  4997.6  302.84  5000.4  302.34  5007.3  303.25
  5014.9   310.4  5085.1  318.02  5104.6  321.63  5142.1  323.82  5191.4  322.41
  5381.9  326.12  5682.9  327.91  5816.2  330.73  6014.6  335.53  6250.7  337.97
#Mann= 7 ,-1 , 0
  4096.5      .1       0  4864.3     .12       0  4865.9     .07       0
  5104.6     .16       0  5104.6      .1       0  5816.2     .08       0
  6014.6      .1       0
Bank Sta=4872.5,5104.6
XS Rating Curve= 0 ,0
Exp/Cntr=0.3,0.1