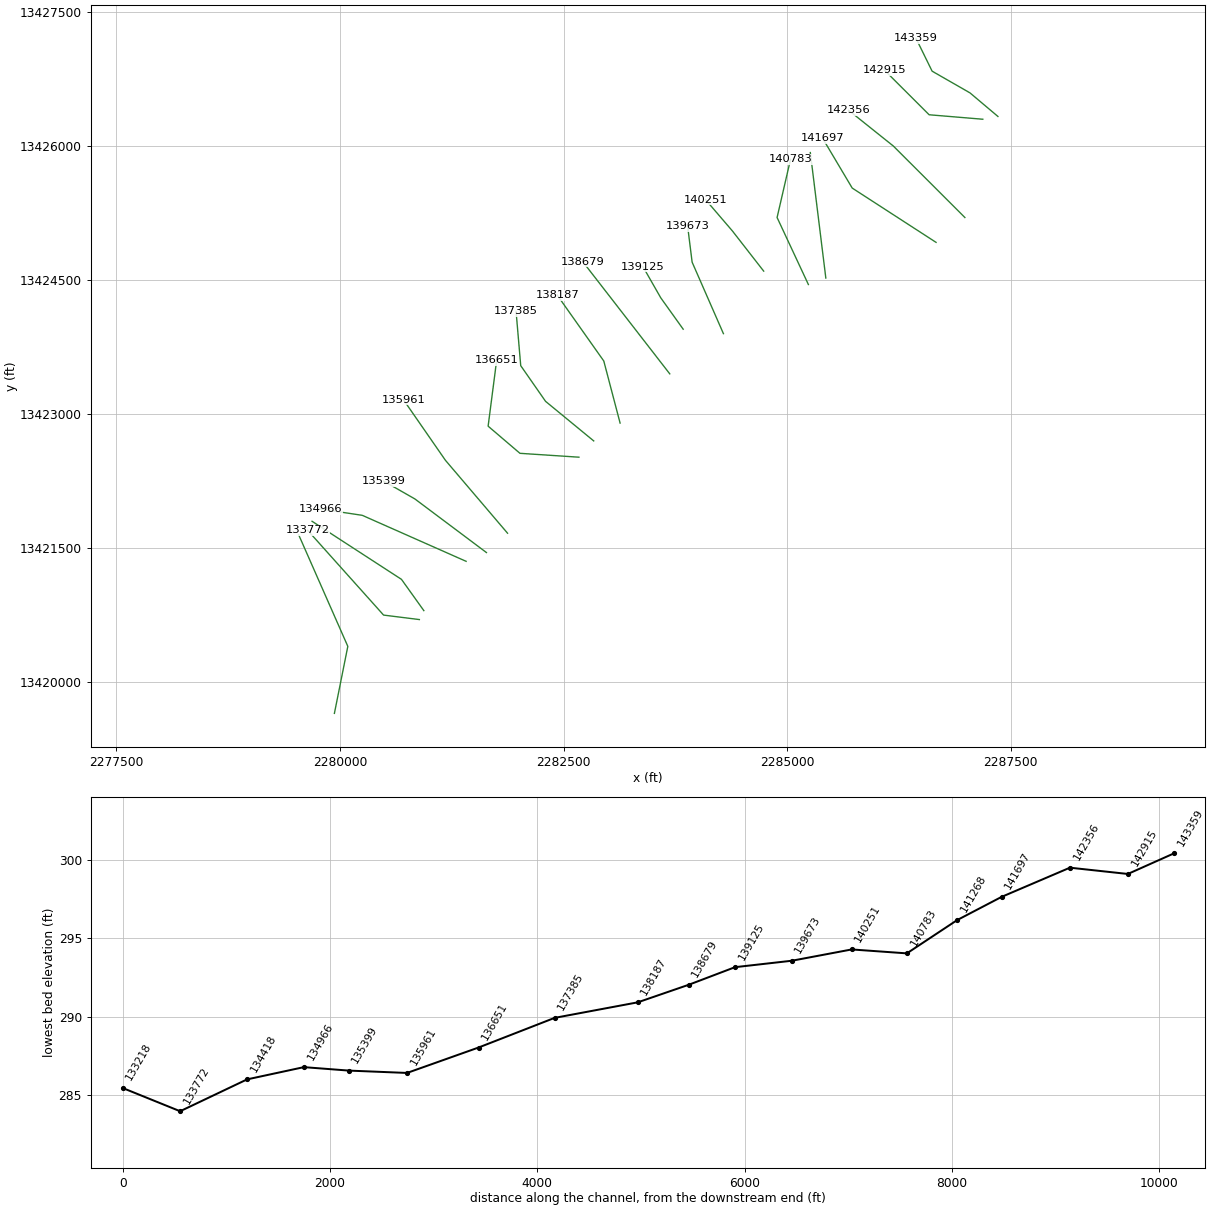
HEC-RAS study SULPHUR CREEK.prj: SULPHUR CREEK Base Level Engineering

--- SULPHUR CREEK.g01 (geometry) --- (continued)

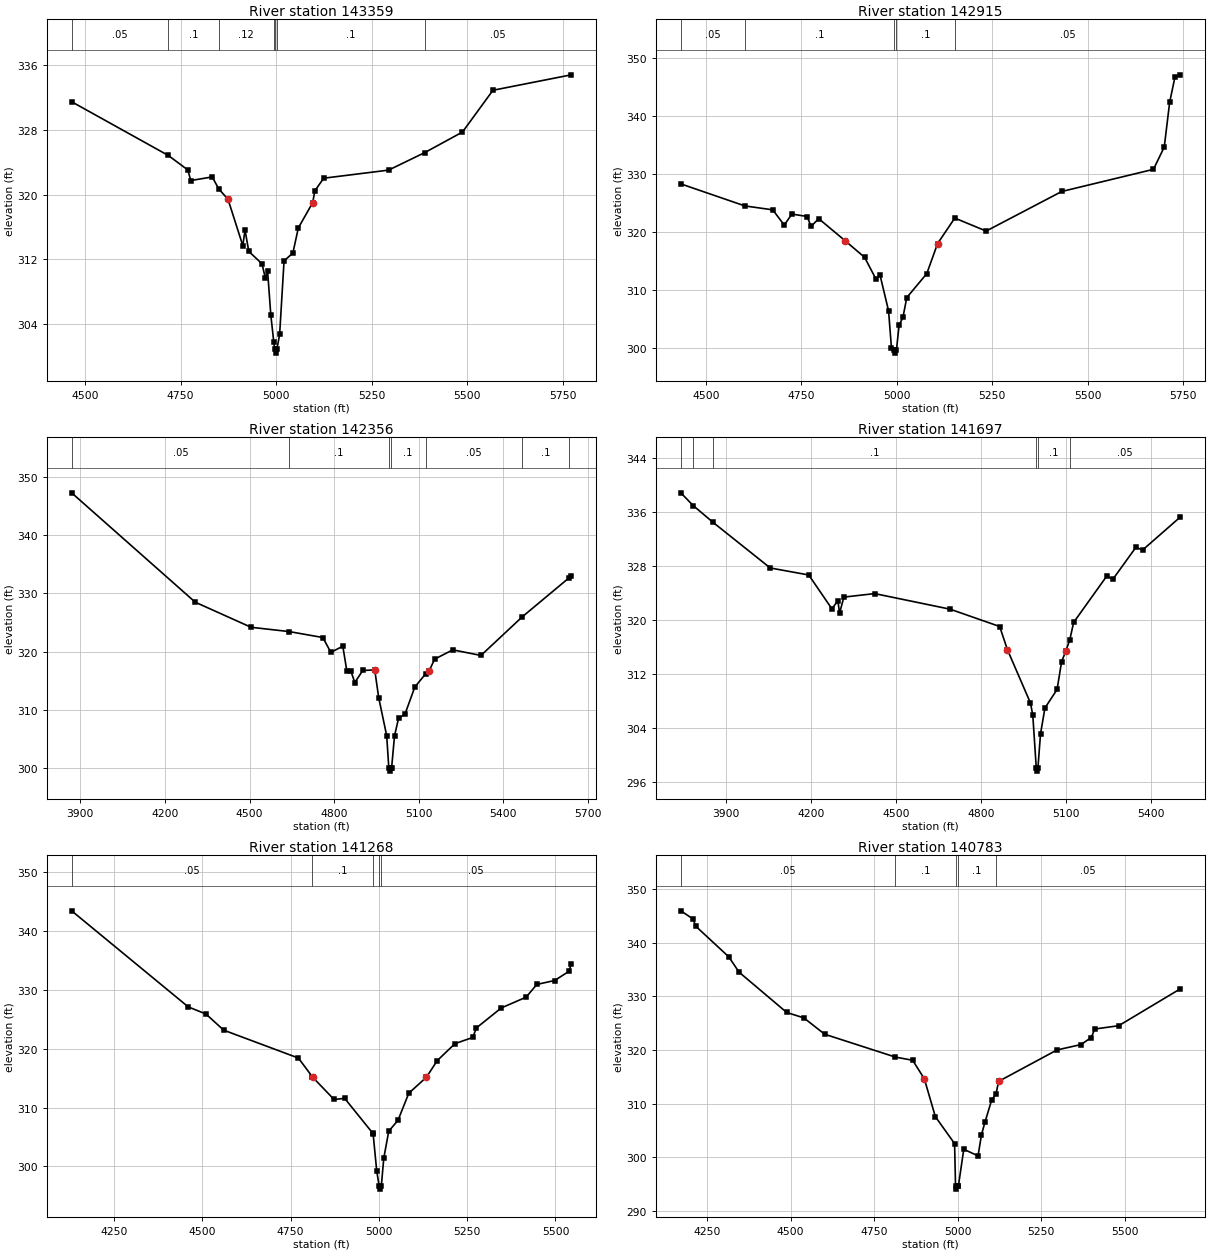
Type RM Length L Ch R = 1 ,143359  ,444,444,444
BEGIN DESCRIPTION:
SULPHUR CREEK 151.0
END DESCRIPTION:
XS GIS Cut Line= 4
      2287357.31     13426327.83      2287044.81     13426591.72
       2286621.2     13426834.77      2286440.89     13427202.33
#Sta/Elev= 30
  4465.1   331.5  4718.1  324.85    4769  323.06  4776.7  321.75  4832.7   322.2
    4850  320.71  4874.1  319.43  4912.8   313.7  4918.6  315.63  4928.4  312.99
    4963  311.45  4971.8  309.67  4977.6  310.57    4986  305.14  4993.8  301.77
  4996.1   300.9  4998.9   300.4  5002.1   300.9  5009.1  302.71  5020.7  311.82
  5043.7  312.78  5058.1   315.9  5095.5  319.01  5101.3  320.49  5124.4  322.04
    5294  323.04  5388.7  325.21  5487.3  327.75  5567.1  332.92  5771.9  334.83
#Mann= 7 ,-1 , 0
  4465.1     .05       0  4718.1      .1       0    4850     .12       0
  4993.8      .1       0  4996.1     .07       0  5002.1      .1       0
  5388.7     .05       0
Bank Sta=4874.1,5095.5
XS Rating Curve= 0 ,0
Exp/Cntr=0.3,0.1

Type RM Length L Ch R = 1 ,142915  ,559,559,559
BEGIN DESCRIPTION:
SULPHUR CREEK 150.0
END DESCRIPTION:
XS GIS Cut Line= 3
      2287187.75     13426296.85      2286587.72     13426346.85
      2286087.73     13426846.84
#Sta/Elev= 30
  4433.9  328.26  4601.9  324.46  4674.8  323.79  4704.9  321.16  4724.9  323.06
  4765.1  322.64  4775.1  320.93  4795.2  322.27  4865.4  318.41  4915.6  315.59
  4945.7  311.79  4955.7   312.6  4978.3  306.37  4985.8  300.02  4992.9  299.59
  4995.6  299.09  4998.9  299.59  5005.9  303.93  5015.9  305.24    5026  308.67
  5078.4  312.79  5106.7  317.97  5151.8  322.37    5234  320.13    5432  326.95
  5672.4  330.77  5700.7  334.61  5714.8  342.31    5729  346.77  5743.1  347.06
#Mann= 5 ,-1 , 0
  4433.9     .05       0  4601.9      .1       0  4992.9     .07       0
  4998.9      .1       0  5151.8     .05       0
Bank Sta=4865.4,5106.7
XS Rating Curve= 0 ,0
Exp/Cntr=0.3,0.1

Type RM Length L Ch R = 1 ,142356  ,659,659,659
BEGIN DESCRIPTION:
SULPHUR CREEK 149.0
END DESCRIPTION:
XS GIS Cut Line= 3
       2286987.7     13425196.87      2286187.72     13425996.85
      2285687.69     13426396.88
#Sta/Elev= 30
  3869.3  347.22  4307.7  328.46  4505.7  324.16  4641.1  323.42  4760.2   322.4
  4788.5  319.85  4830.9  320.92  4845.1  316.69  4859.2  316.68  4873.4  314.69
  4901.7  316.75  4944.1  316.85  4958.2  312.08  4986.5  305.56  4994.1  299.99
  4996.9  299.49  5000.1  299.99  5003.8  299.99  5014.3  305.54  5028.7  308.59
  5051.1  309.23  5086.3  313.92    5125   316.2  5135.9  316.58  5156.7   318.7
  5220.8  320.29  5320.8  319.33  5467.2  325.95  5634.4  332.69    5641  333.03
#Mann= 7 ,-1 , 0
  3869.3     .05       0  4641.1      .1       0  4994.1     .07       0
  5000.1      .1       0    5125     .05       0  5467.2      .1       0
  5634.4     .05       0
Bank Sta=4944.1,5135.9
XS Rating Curve= 0 ,0
Exp/Cntr=0.3,0.1

Type RM Length L Ch R = 1 ,141697  ,429,429,429
BEGIN DESCRIPTION:
SULPHUR CREEK 148.0
END DESCRIPTION:
XS GIS Cut Line= 3
      2286665.27     13424918.69      2285727.77     13425526.33
      2285397.91     13426081.89
#Sta/Elev= 30
  3739.3  338.89    3783     337  3852.8  334.52  4054.9  327.75  4190.8  326.71
  4272.5  321.69  4293.6  322.89  4299.6  321.05  4314.7  323.43  4423.5  323.95
  4689.7  321.64  4864.7  319.07    4892  315.63  4973.4  307.72  4981.6  305.89
  4993.7  298.13  4996.4  297.63  4999.7  298.13  5008.8  303.16  5024.4  306.99
  5067.3  309.74  5082.9   313.8  5098.5   315.5    5112  317.08  5125.7  319.68
  5242.6  326.55  5264.2  326.08  5345.6  330.82  5368.8   330.4  5502.6  335.32
#Mann= 6 ,-1 , 0
  3739.3      .1       0    3783     .05       0  3852.8      .1       0
  4993.7     .07       0  4999.7      .1       0    5112     .05       0
Bank Sta=4892,5098.5
XS Rating Curve= 0 ,0
Exp/Cntr=0.3,0.1

Type RM Length L Ch R = 1 ,141268  ,485,485,485
BEGIN DESCRIPTION:
SULPHUR CREEK 147.0
END DESCRIPTION:
XS GIS Cut Line= 2
      2285432.63      13424519.4      2285259.26     13425923.73
#Sta/Elev= 30
  4129.7  343.44  4460.1  327.11    4510  325.91  4560.4  323.16    4772  318.42
  4811.8  315.21  4812.3  315.17  4872.8  311.39    4903  311.57  4981.9   305.7
  4983.6  305.52  4993.7  299.26  5000.7  296.65  5003.5  296.15  5006.7  296.65
  5013.8  301.44  5027.8  305.99  5054.1  307.86  5084.4  312.43  5134.7  315.18
    5165  317.98  5215.3  320.87  5265.7  321.92  5276.2  323.55  5346.3  326.93
  5416.9  328.77  5447.1  330.93  5497.5   331.6  5537.8  333.14  5544.7  334.38
#Mann= 5 ,-1 , 0
  4129.7     .05       0  4811.8      .1       0  4981.9     .05       0
  5000.7     .03       0  5006.7     .05       0
Bank Sta=4812.3,5134.7
XS Rating Curve= 0 ,0
Exp/Cntr=0.3,0.1

Type RM Length L Ch R = 1 ,140783  ,532,532,532
BEGIN DESCRIPTION:
SULPHUR CREEK 146.0
END DESCRIPTION:
XS GIS Cut Line= 3
      2285237.72     13424446.85      2284887.72     13425196.85
      2285037.71     13425846.82
#Sta/Elev= 30
  4171.5  345.99  4208.5  344.45  4215.6  343.15    4315   337.4  4345.7  334.54
  4488.4  327.01  4539.6     326  4601.9  322.95  4813.6  318.68  4865.1  318.09
    4900  314.63  4932.9  307.57  4990.5  302.53  4993.4  294.53  4996.1  294.03
  4999.4  294.53  5001.7  294.53    5018  301.47  5060.7  300.24    5071  304.19
  5081.3  306.51  5101.8  310.74  5114.1  311.72  5122.3  314.15  5296.8  320.01
  5368.6  321.02  5399.4  322.33  5409.7  323.92  5481.5  324.54  5666.2  331.44
#Mann= 5 ,-1 , 0
  4171.5     .05       0  4813.6      .1       0  4993.4     .07       0
  4999.4      .1       0  5114.1     .05       0
Bank Sta=4900,5122.3
XS Rating Curve= 0 ,0
Exp/Cntr=0.3,0.1

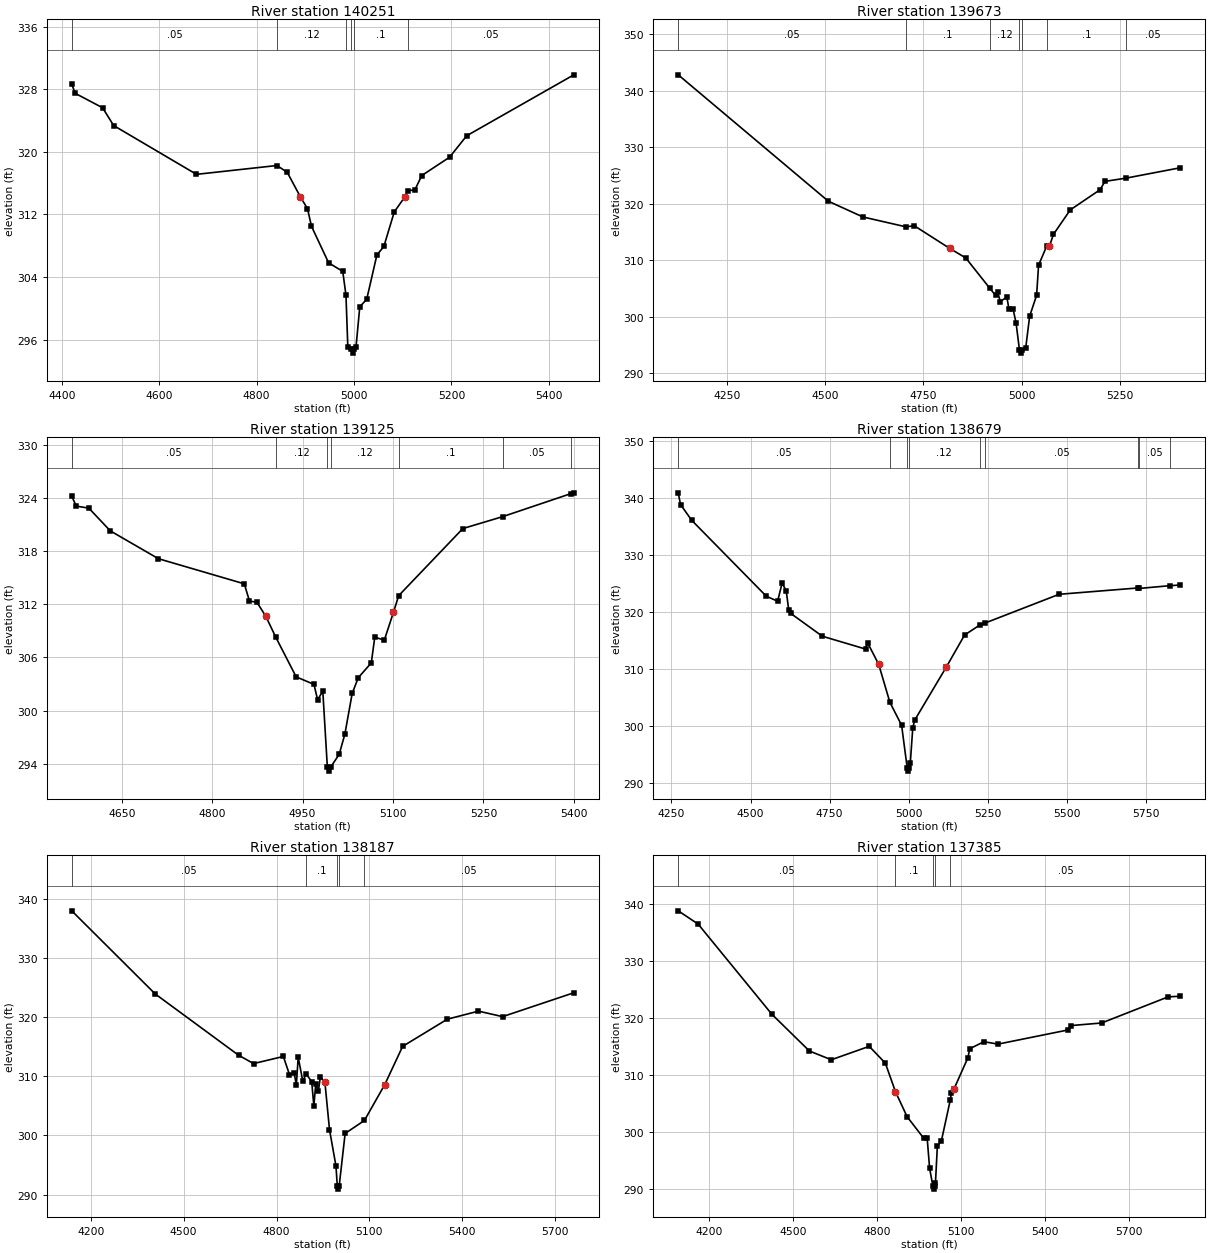
Type RM Length L Ch R = 1 ,140251  ,578,578,578
BEGIN DESCRIPTION:
SULPHUR CREEK 145.0
END DESCRIPTION:
XS GIS Cut Line= 3
      2284737.71     13424596.86      2284387.72     13425046.85
      2284087.69     13425396.89
#Sta/Elev= 30
  4420.4  328.63  4427.6  327.48  4483.7  325.64  4506.4  323.37  4676.5  317.13
  4841.8  318.26  4862.9  317.39    4890  314.24  4904.5  312.74  4912.7  310.49
  4947.9  305.82  4976.9  304.73  4983.5  301.69  4987.3  295.11  4994.6  294.78
  4997.4  294.28  5000.6  294.78  5004.2   295.1  5011.9  300.21  5026.1  301.16
    5047  306.82  5061.3  307.91  5082.7  312.33  5104.1  314.22    5110  315.04
  5124.9  315.13  5139.2  316.98  5196.3  319.32  5231.4  322.06  5451.5  329.85
#Mann= 6 ,-1 , 0
  4420.4     .05       0  4841.8     .12       0  4983.5      .1       0
  4994.6     .07       0  5000.6      .1       0    5110     .05       0
Bank Sta=4890,5104.1
XS Rating Curve= 0 ,0
Exp/Cntr=0.3,0.1

Type RM Length L Ch R = 1 ,139673  ,548,548,548
BEGIN DESCRIPTION:
SULPHUR CREEK 144.0
END DESCRIPTION:
XS GIS Cut Line= 3
      2284287.71     13423896.87      2283937.72     13424696.85
      2283887.72     13425096.85
#Sta/Elev= 30
  4126.7  342.79  4508.3  320.43    4596  317.65    4705  315.91    4727  316.08
  4816.3  312.11  4857.6   310.4  4919.1     305  4933.2  303.78  4938.7  304.38
  4945.3  302.69  4962.1  303.48  4967.5  301.31  4978.1  301.28  4985.5   298.9
  4994.2  294.06  4996.9  293.56  5000.2  294.06    5010  294.48    5020  300.08
  5037.7   303.8  5042.7  309.12  5063.6  312.53  5070.4  312.48  5080.5  314.57
  5123.3   318.9  5198.9  322.46  5211.5  323.94  5264.5  324.51    5403  326.35
#Mann= 7 ,-1 , 0
  4126.7     .05       0    4705      .1       0  4919.1     .12       0
  4994.2     .07       0  5000.2     .12       0  5063.6      .1       0
  5264.5     .05       0
Bank Sta=4816.3,5070.4
XS Rating Curve= 0 ,0
Exp/Cntr=0.3,0.1

Type RM Length L Ch R = 1 ,139125  ,446,446,446
BEGIN DESCRIPTION:
SULPHUR CREEK 143.0
END DESCRIPTION:
XS GIS Cut Line= 3
      2283837.73     13423946.85      2283587.72     13424296.85
      2283387.74     13424646.82
#Sta/Elev= 30
  4566.9  324.24  4574.3  323.12  4595.2  322.89  4630.8  320.32  4710.7  317.17
  4853.2  314.33  4861.8  312.38  4874.1  312.25  4888.9  310.66  4905.4   308.3
  4939.3  303.81  4968.8  302.96  4974.9  301.22  4983.5  302.19    4991  293.65
  4993.7  293.15    4997  293.65  5010.7  295.05  5020.1  297.33  5032.3  301.95
  5042.4  303.72    5064  305.39  5069.7  308.29  5085.6  307.97  5100.7   311.1
  5109.4  312.99  5215.9  320.58  5282.1  321.93  5395.7  324.54  5400.1  324.62
#Mann= 7 ,-1 , 0
  4566.9     .05       0  4905.4     .12       0    4991     .07       0
    4997     .12       0  5109.4      .1       0  5282.1     .05       0
  5395.7      .1       0
Bank Sta=4888.9,5100.7
XS Rating Curve= 0 ,0
Exp/Cntr=0.3,0.1

Type RM Length L Ch R = 1 ,138679  ,492,492,492
BEGIN DESCRIPTION:
SULPHUR CREEK 142.0
END DESCRIPTION:
XS GIS Cut Line= 2
      2283687.71     13423446.86      2282715.62     13424701.68
#Sta/Elev= 30
  4271.4  340.88  4278.6  338.83  4313.9  336.06  4549.7  322.74  4585.6  321.85
    4600  325.08  4612.9  323.62  4620.9  320.25  4627.2  319.71  4726.8  315.71
  4863.5  313.46  4869.8  314.58  4905.1  310.78  4940.5  304.11  4977.6  300.08
  4995.4  292.53  4998.1  292.03  5001.4  292.53  5005.1  293.47  5012.9  299.65
  5019.2     301  5118.9   310.3  5176.7  315.92    5224  317.65  5241.2  318.02
  5475.5  323.07  5724.5  324.18  5729.2   324.1  5825.3  324.58  5858.7   324.7
#Mann= 9 ,-1 , 0
  4271.4     .05       0  4940.5     .12       0  4995.4     .07       0
  5001.4     .12       0    5224      .1       0  5241.2     .05       0
  5724.5      .1       0  5729.2     .05       0  5825.3      .1       0
Bank Sta=4905.1,5118.9
XS Rating Curve= 0 ,0
Exp/Cntr=0.3,0.1

Type RM Length L Ch R = 1 ,138187  ,802,802,802
BEGIN DESCRIPTION:
SULPHUR CREEK 141.0
END DESCRIPTION:
XS GIS Cut Line= 3
       2283132.3     13422896.08      2282949.99     13423590.57
      2282429.14     13424328.44
#Sta/Elev= 30
  4138.9  337.99  4408.1  323.94  4677.3  313.57  4725.9  312.15  4822.1  313.35
  4841.9  310.28  4856.9   310.6    4864  308.54  4870.1  313.21  4884.9  309.16
  4895.7  310.39  4913.6  309.11  4920.6  304.96  4926.7  308.73  4935.4  307.57
  4941.5  309.86  4956.3  308.98  4971.1  300.98    4992  294.82  4996.3  291.41
    4999  290.91  5002.3  291.41  5021.6  300.33  5083.8  302.52  5149.6   308.6
  5207.3  315.06  5351.6  319.66  5452.1  321.02  5530.1  320.09  5760.1  324.13
#Mann= 5 ,-1 , 0
  4138.9     .05       0  4895.7      .1       0  4996.3     .07       0
  5002.3      .1       0  5083.8     .05       0
Bank Sta=4956.3,5149.6
XS Rating Curve= 0 ,0
Exp/Cntr=0.3,0.1

Type RM Length L Ch R = 1 ,137385  ,734,734,734
BEGIN DESCRIPTION:
SULPHUR CREEK 140.0
END DESCRIPTION:
XS GIS Cut Line= 4
      2282837.17     13422696.46      2282298.95     13423139.18
      2282021.17     13423538.49      2281969.09     13424146.13
#Sta/Elev= 30
  4088.6   338.8  4159.6  336.47  4422.9  320.64    4557  314.18  4635.2  312.64
  4770.8     315  4828.4  312.04  4864.5  307.03    4906  302.64  4965.4  298.86
  4977.6  298.94  4986.4  293.58  4998.2  290.42    5001  289.92  5004.2  290.42
  5007.3  290.99  5014.1  297.52  5028.2  298.33  5060.4  305.61    5064  306.83
  5072.8  307.44  5123.4  313.02  5129.5  314.57  5180.1  315.81  5230.8  315.39
  5481.1  317.88  5492.1  318.65  5600.8   319.1  5838.3  323.69  5881.8   323.8
#Mann= 5 ,-1 , 0
  4088.6     .05       0  4864.5      .1       0  4998.2     .07       0
  5004.2      .1       0  5060.4     .05       0
Bank Sta=4864.5,5072.8
XS Rating Curve= 0 ,0
Exp/Cntr=0.3,0.1

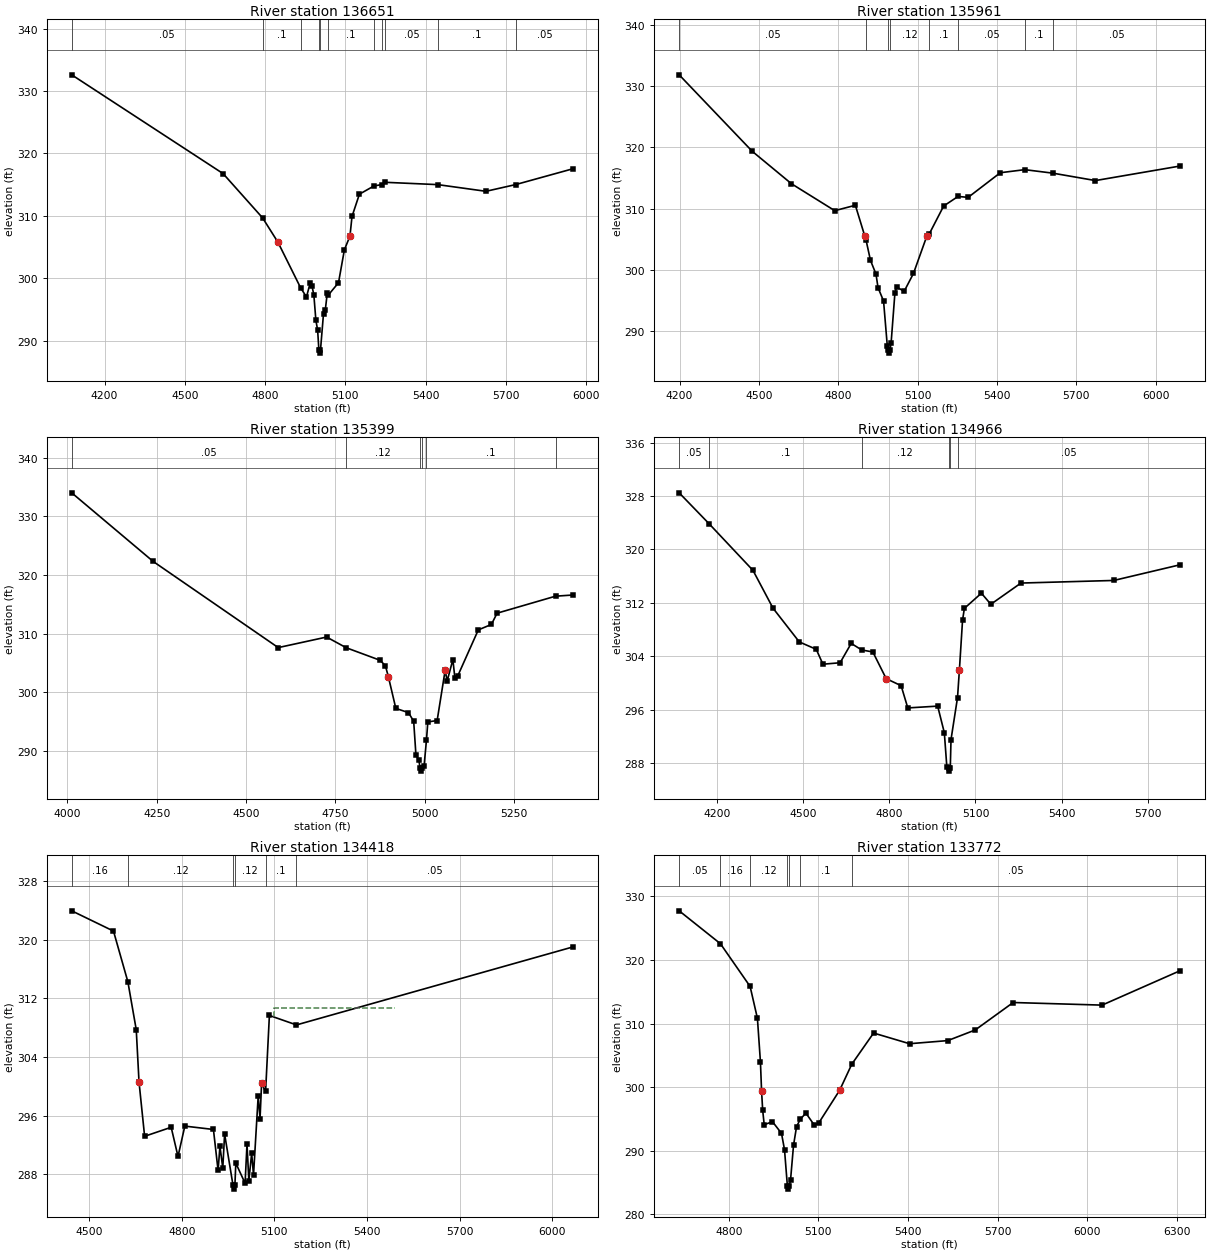
Type RM Length L Ch R = 1 ,136651  ,690,690,690
BEGIN DESCRIPTION:
SULPHUR CREEK 139.0
END DESCRIPTION:
XS GIS Cut Line= 4
      2282672.26     13422514.18      2282012.49     13422557.58
      2281656.59      13422861.4      2281752.07     13423599.22
#Sta/Elev= 30
  4077.5  332.59  4643.3  316.77  4791.1  309.67  4848.3  305.78  4932.8   298.5
  4954.8  297.02  4968.5  299.23  4975.7   298.7  4982.3  297.39    4990  293.27
  4996.5  291.73  5001.2  288.53    5004  288.03  5007.2  288.53  5018.5  294.36
  5025.1  294.93  5032.8  297.72  5036.6  297.34  5074.5   299.3  5096.5  304.57
  5117.3  306.77    5125  309.91  5152.6  313.48  5207.2   314.8  5235.5  315.01
  5249.4  315.38  5445.5  315.01  5625.6  313.94  5736.9  315.02  5950.6  317.55
#Mann= 11 ,-1 , 0
  4077.5     .05       0  4791.1      .1       0  4932.8     .12       0
  5001.2     .07       0  5007.2     .12       0  5036.6      .1       0
  5207.2     .05       0  5235.5      .1       0  5249.4     .05       0
  5445.5      .1       0  5736.9     .05       0
Bank Sta=4848.3,5117.3
XS Rating Curve= 0 ,0
Exp/Cntr=0.3,0.1

Type RM Length L Ch R = 1 ,135961  ,562,562,562
BEGIN DESCRIPTION:
SULPHUR CREEK 138.0
END DESCRIPTION:
XS GIS Cut Line= 3
      2281873.63     13421663.45      2281179.16     13422479.46
      2280710.43     13423156.51
#Sta/Elev= 30
  4198.7  331.81  4475.1  319.33  4623.4  314.04    4787  309.65  4864.9  310.53
  4900.1  305.57  4904.9  304.93  4922.1  301.53  4942.9  299.31  4950.6  297.09
  4971.5  294.92  4985.7  287.56  4989.3  286.91  4992.1  286.41  4995.3  286.91
    5000  288.03  5014.3  296.14  5020.9   297.2  5049.4  296.49  5084.6  299.41
  5135.1   305.5    5144  305.83  5198.8  310.41  5253.2  311.97  5291.4  311.82
    5413  315.84  5505.4  316.34  5611.4  315.77  5772.6  314.56  6093.7  316.94
#Mann= 8 ,-1 , 0
  4198.7     .05       0  4904.9     .12       0  4989.3     .07       0
  4995.3     .12       0    5144      .1       0  5253.2     .05       0
  5505.4      .1       0  5611.4     .05       0
Bank Sta=4900.1,5135.1
XS Rating Curve= 0 ,0
Exp/Cntr=0.3,0.1

Type RM Length L Ch R = 1 ,135399  ,433,433,433
BEGIN DESCRIPTION:
SULPHUR CREEK 137.0
END DESCRIPTION:
XS GIS Cut Line= 3
      2281637.73     13421446.85      2280837.72     13422046.85
      2280487.74     13422246.84
#Sta/Elev= 30
  4012.2  334.03  4240.3  322.32  4590.3  307.63  4725.8  309.43  4780.9   307.6
  4875.8  305.46  4890.3  304.53  4898.7  302.66  4919.5  297.26  4954.9  296.54
  4969.5  295.07  4975.8  289.33  4984.1  288.43  4987.3  287.06  4990.1  286.56
  4993.3  287.06  4998.7   287.5  5005.2  291.79  5009.1  294.95  5035.2  295.19
  5057.6  303.76  5063.3  301.95  5079.2  305.58  5084.9  302.44  5092.8  302.79
  5150.4  310.65  5187.1  311.58    5203   313.5  5366.6   316.4  5415.3   316.6
#Mann= 6 ,-1 , 0
  4012.2     .05       0  4780.9     .12       0  4987.3     .07       0
  4993.3     .12       0  5005.2      .1       0  5366.6     .05       0
Bank Sta=4898.7,5057.6
XS Rating Curve= 0 ,0
Exp/Cntr=0.3,0.1

Type RM Length L Ch R = 1 ,134966  ,548,548,548
BEGIN DESCRIPTION:
SULPHUR CREEK 136.0
END DESCRIPTION:
XS GIS Cut Line= 3
       2281410.4      13421348.7      2280249.42     13421863.47
      2279778.46     13421934.66
#Sta/Elev= 30
  4067.6  328.48  4171.6  323.86  4324.8  316.86  4394.7  311.19  4486.2  306.14
  4545.3  305.03  4568.5   302.8  4628.4  303.02  4667.1  305.92  4703.8  304.93
  4742.4  304.64  4788.9  300.64    4841  299.58  4864.2  296.25  4968.3  296.52
  4991.5  292.54  5000.3   287.4  5006.3  287.28  5009.1  286.78  5012.3  287.28
  5014.8  291.51  5037.5  297.81  5044.1  301.98    5055   309.4  5061.4  311.17
  5120.7  313.44  5153.5  311.78  5258.5  314.96    5582  315.35  5813.9  317.71
#Mann= 6 ,-1 , 0
  4067.6     .05       0  4171.6      .1       0  4703.8     .12       0
  5006.3     .07       0  5012.3     .12       0  5037.5     .05       0
Bank Sta=4788.9,5044.1
XS Rating Curve= 0 ,0
Exp/Cntr=0.3,0.1

Type RM Length L Ch R = 1 ,134418  ,646,646,646
BEGIN DESCRIPTION:
SULPHUR CREEK 135.0
END DESCRIPTION:
XS GIS Cut Line= 3
      2280937.72     13420796.85      2280687.72     13421146.85
      2279687.73     13421796.85
#Sta/Elev= 30
  4443.9  323.93  4579.1  321.17  4625.7  314.26  4652.8  307.73 4661.82  300.59
  4679.9   293.2  4765.9  294.43    4788  290.45  4810.1  294.59  4902.7  294.13
  4917.8  288.54  4923.8  291.84    4933  288.87  4938.9  293.52  4966.2   286.5
    4969     286  4972.2   286.5  4975.2  289.54  5005.2   286.8  5011.4  292.12
  5017.4  287.15  5026.5  290.89  5032.5  287.92  5047.7  298.73  5053.6  295.58
 5058.64   300.4  5071.6  299.31  5083.9  309.67  5171.6  308.38  6066.7  319.01
#Mann= 6 ,-1 , 0
  4443.9     .16       0  4625.7     .12       0  4966.2     .07       0
  4972.2     .12       0  5071.6      .1       0  5171.6     .05       0
#XS Ineff= 1 ,-1
  5097.6 5489.67  310.69
Permanent Ineff=
       T
Bank Sta=4661.82,5058.64
XS Rating Curve= 0 ,0
Exp/Cntr=0.3,0.1

Type RM Length L Ch R = 1 ,133772  ,554,554,554
BEGIN DESCRIPTION:
SULPHUR CREEK 134.0
END DESCRIPTION:
XS GIS Cut Line= 3
      2280887.71     13420696.86      2280487.72     13420746.85
      2279637.69     13421696.89
#Sta/Elev= 30
    4634  327.74  4772.1  322.57  4871.5  315.85    4896  310.83  4906.1  303.96
 4909.89   299.4  4913.6  296.39  4918.7   294.1  4946.4  294.58  4976.6  292.74
  4986.7  290.18  4996.3  284.47  4999.1  283.97  5002.3  284.47  5006.9  285.42
  5016.9  290.87    5027  293.79  5039.8  294.99  5058.4  295.92  5086.8  294.01
    5101  294.35  5171.3  299.52  5211.8  303.61  5284.9  308.52  5405.3  306.84
  5533.2  307.33  5625.1     309  5752.2  313.32  6049.8  312.91  6311.9  318.34
#Mann= 7 ,-1 , 0
    4634     .05       0  4772.1     .16       0  4871.5     .12       0
  4996.3     .07       0  5002.3     .12       0  5039.8      .1       0
  5211.8     .05       0
Bank Sta=4909.89,5171.3
XS Rating Curve= 0 ,0
Exp/Cntr=0.3,0.1

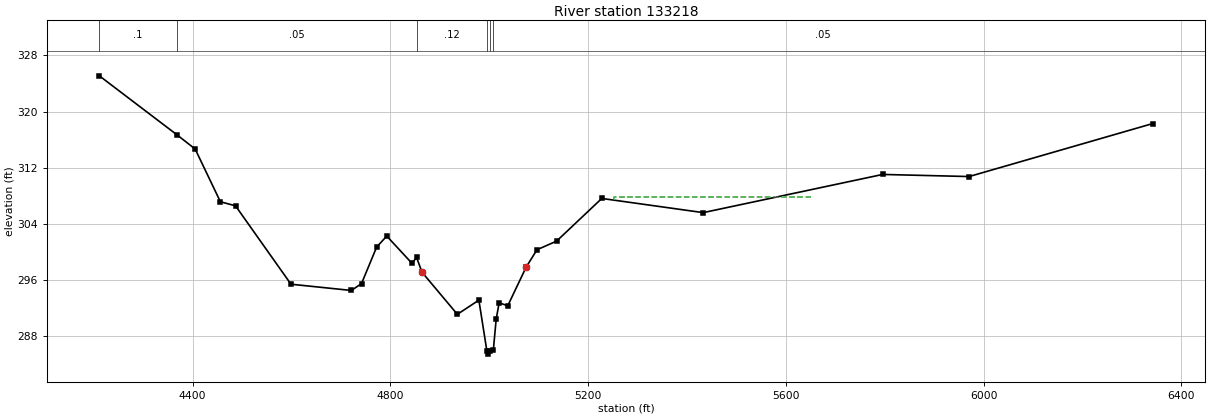
Type RM Length L Ch R = 1 ,133218  ,481,481,481
BEGIN DESCRIPTION:
SULPHUR CREEK 133.0
END DESCRIPTION:
XS GIS Cut Line= 3
      2279937.71     13419646.81      2280087.72     13420396.85
      2279537.74     13421646.81
#Sta/Elev= 30
  4211.5   325.1  4368.6  316.69  4405.3  314.67  4456.3  307.16  4486.9  306.58
  4599.1  295.41  4721.4  294.52  4741.8  295.51  4772.4  300.71  4792.8  302.27
  4843.8  298.39  4853.1  299.22  4864.2  297.11  4935.6  291.12  4979.1  293.14
  4995.2  285.95    4998  285.45  5001.2  285.95  5008.3  285.98  5014.1  290.43
  5020.1  292.76  5037.5  292.34  5074.7  297.84  5096.6  300.32  5136.3  301.55
  5227.7  307.63  5432.8  305.61  5795.8  311.05  5970.6  310.75    6342   318.3
#Mann= 6 ,-1 , 0
  4211.5      .1       0  4368.6     .05       0  4853.1     .12       0
  4995.2     .07       0  5001.2     .12       0  5008.3     .05       0
#XS Ineff= 2 ,-1
 4318.25 4795.62  301.96 5251.77 5654.88  307.88
Permanent Ineff=
       T       T
Bank Sta=4864.2,5074.7
XS Rating Curve= 0 ,0
Exp/Cntr=0.3,0.1