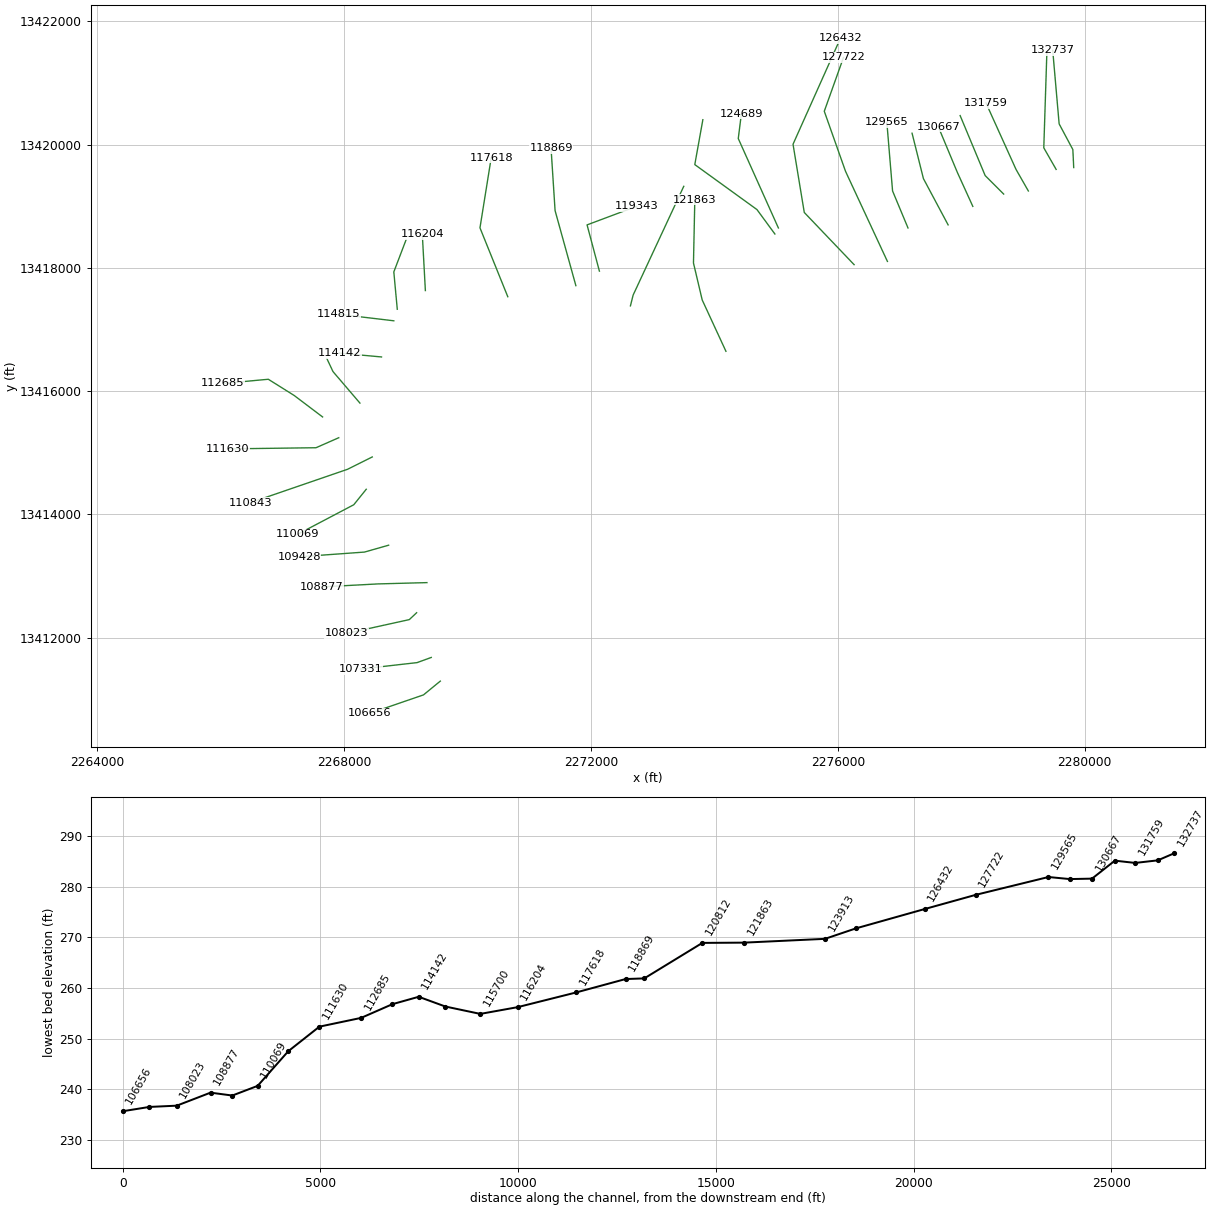
HEC-RAS study SULPHUR CREEK.prj: SULPHUR CREEK Base Level Engineering

--- SULPHUR CREEK.g01 (geometry) --- (continued)

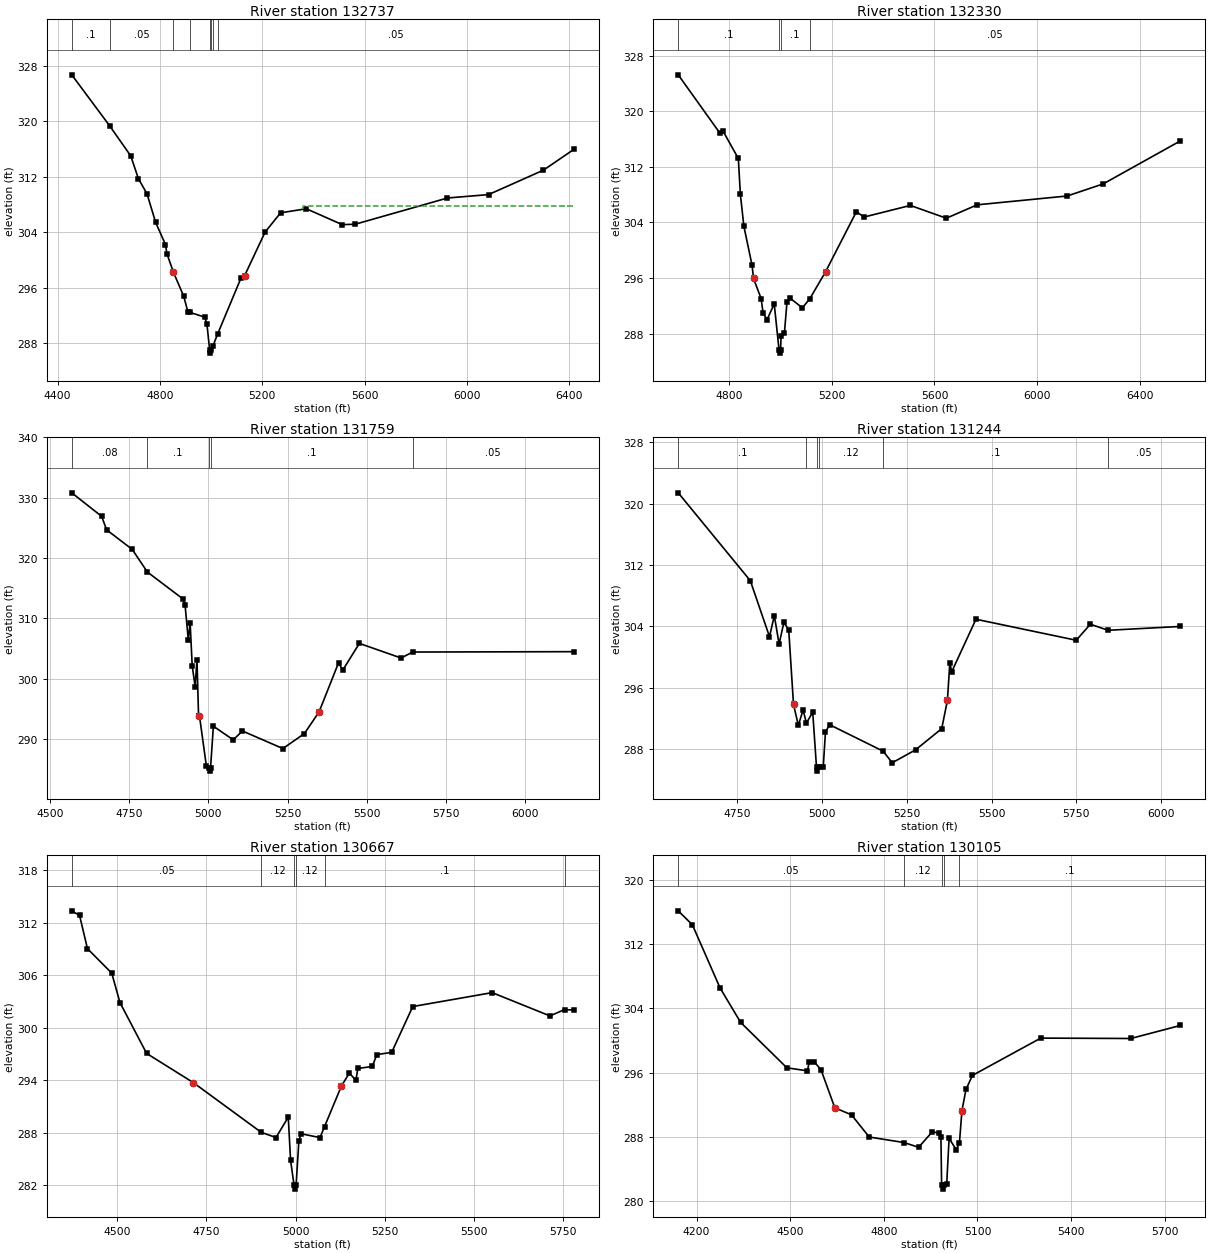
Type RM Length L Ch R = 1 ,132737  ,407,407,407
BEGIN DESCRIPTION:
SULPHUR CREEK 132.0
END DESCRIPTION:
XS GIS Cut Line= 4
      2279822.59     13419626.44       2279808.7     13419918.11
      2279586.48     13420334.77      2279482.31     13421529.22
#Sta/Elev= 30
  4455.2   326.7  4604.2   319.3  4685.9     315  4715.9   311.7  4749.3  309.54
  4783.3   305.4  4821.5  302.22  4827.2   300.9  4852.4  298.25  4893.1  294.74
  4909.4  292.48  4917.8  292.42  4975.3  291.74  4983.8  290.72  4994.2  287.05
    4997  286.55  5000.2  287.05    5007  287.55  5025.3  289.29  5117.6  297.44
  5131.1  297.73  5211.1  304.01  5271.7  306.79  5372.1  307.38  5512.6  305.09
  5562.8  305.14  5924.2  308.93  6084.8  309.42  6299.6  312.95  6418.4  315.94
#Mann= 8 ,-1 , 0
  4455.2      .1       0  4604.2     .05       0  4852.4      .1       0
  4917.8     .12       0  4994.2     .07       0  5000.2     .12       0
    5007      .1       0  5025.3     .05       0
#XS Ineff= 2 , 0
                         5360.17          307.73
Permanent Ineff=
       T       T
Bank Sta=4852.4,5131.1
XS Rating Curve= 0 ,0
Exp/Cntr=0.3,0.1

Type RM Length L Ch R = 1 ,132330  ,571,571,571
BEGIN DESCRIPTION:
SULPHUR CREEK 131.0
END DESCRIPTION:
XS GIS Cut Line= 3
      2279537.71     13419596.88      2279337.72     13419946.85
      2279387.72     13421496.86
#Sta/Elev= 30
  4602.9  325.26  4764.1  316.91  4777.8  317.12  4836.8  313.21  4844.7  308.05
  4858.4  303.44  4890.1  297.85  4895.9  295.93  4925.4  293.04  4933.3  290.94
  4948.4     290  4976.5  292.26  4995.1  285.68  4997.8  285.18  5001.1  285.68
  5003.1  287.59    5016  288.04    5026  292.48    5036  293.16    5086   291.7
  5115.1  293.02  5176.1  296.89  5296.1  305.54  5326.2  304.78  5506.2  306.45
  5646.3  304.61  5766.4  306.54  6116.6  307.81  6256.6  309.55  6556.8  315.74
#Mann= 4 ,-1 , 0
  4602.9      .1       0  4995.1     .07       0  5001.1      .1       0
  5115.1     .05       0
Bank Sta=4895.9,5176.1
XS Rating Curve= 0 ,0
Exp/Cntr=0.3,0.1

Type RM Length L Ch R = 1 ,131759  ,515,515,515
BEGIN DESCRIPTION:
SULPHUR CREEK 130.0
END DESCRIPTION:
XS GIS Cut Line= 3
      2279087.71     13419246.87      2278887.72     13419596.85
      2278401.35     13420673.83
#Sta/Elev= 30
    4569   330.8  4663.3   326.9  4679.1  324.66  4759.7  321.43  4807.7  317.67
    4921  313.17  4926.7  312.16  4936.8  306.43  4942.6  309.29  4949.1  302.15
  4958.4  298.68  4964.2  303.14  4969.2  293.82  4972.1  293.82    4994  285.46
    5001  285.17  5003.8  284.67    5007  285.17    5016  292.11  5078.9  289.85
  5107.5  291.33  5235.4  288.41  5303.4   290.9  5349.7   294.5    5411  302.61
  5424.5  301.42  5476.8  305.84  5608.5  303.42    5645  304.41  6153.8  304.47
#Mann= 5 ,-1 , 0
    4569     .08       0  4807.7      .1       0    5001     .07       0
    5007      .1       0    5645     .05       0
Bank Sta=4972.1,5349.7
XS Rating Curve= 0 ,0
Exp/Cntr=0.3,0.1

Type RM Length L Ch R = 1 ,131244  ,577,577,577
BEGIN DESCRIPTION:
SULPHUR CREEK 129.0
END DESCRIPTION:
XS GIS Cut Line= 3
      2278687.74     13419196.84      2278387.72     13419496.85
      2277982.33     13420469.79
#Sta/Elev= 30
  4577.6  321.42  4789.8  309.96  4846.3  302.66  4860.5  305.39  4874.6   301.7
  4888.7  304.53  4902.9  303.55    4917  293.82  4931.2  291.09  4945.3  293.11
  4954.9  291.39  4973.6   292.8  4984.7  285.62  4987.5  285.12  4990.7  285.62
  5004.6  285.67  5011.1  290.25  5023.6  291.17  5180.9  287.72  5207.7  286.21
  5276.5   287.9  5353.4  290.66  5370.2  294.36  5377.3  299.28  5382.7  298.07
  5454.2  304.93  5749.4  302.19  5791.1  304.28  5843.2  303.49  6055.9  303.99
#Mann= 6 ,-1 , 0
  4577.6      .1       0  4954.9     .12       0  4984.7     .07       0
  4990.7     .12       0  5180.9      .1       0  5843.2     .05       0
Bank Sta=4917,5370.2
XS Rating Curve= 0 ,0
Exp/Cntr=0.3,0.1

Type RM Length L Ch R = 1 ,130667  ,562,562,562
BEGIN DESCRIPTION:
SULPHUR CREEK 128.0
END DESCRIPTION:
XS GIS Cut Line= 3
       2278187.7     13418996.89      2277937.72     13419546.85
      2277628.84     13420288.17
#Sta/Elev= 30
  4372.6  313.38  4394.5  312.85  4416.5  309.06  4484.6  306.26  4507.7  302.89
  4582.4  297.08  4713.1  293.75  4903.7  288.06  4944.9  287.47  4979.4  289.79
  4985.9  284.85  4995.4  282.07  4998.1  281.57  5001.4  282.07  5009.2  287.12
  5015.2   287.9  5068.3  287.46  5081.1  288.72  5128.4  293.36  5150.6  294.83
    5169  294.01  5174.4  295.36    5215  295.59  5227.5  296.95  5269.2   297.2
  5328.3  302.44  5550.9  304.03  5712.8  301.37  5753.7  302.09  5779.8  302.04
#Mann= 6 ,-1 , 0
  4372.6     .05       0  4903.7     .12       0  4995.4     .07       0
  5001.4     .12       0  5081.1      .1       0  5753.7     .05       0
Bank Sta=4713.1,5128.4
XS Rating Curve= 0 ,0
Exp/Cntr=0.3,0.1

Type RM Length L Ch R = 1 ,130105  ,540,540,540
BEGIN DESCRIPTION:
SULPHUR CREEK 127.0
END DESCRIPTION:
XS GIS Cut Line= 3
      2277787.71     13418696.88      2277387.72     13419446.85
      2277203.63     13420183.22
#Sta/Elev= 30
  4141.1  316.14  4186.4   314.4  4275.3  306.52  4341.2  302.24  4489.2  296.59
  4555.1  296.21  4560.8  297.31    4577  297.35    4599  296.31  4642.9  291.61
  4696.4  290.73  4753.1  287.97  4864.7  287.28  4911.4  286.69  4955.3  288.62
  4977.3  288.46  4982.9  288.02  4985.2  281.98    4988  281.48  4991.2  281.98
  5001.4   282.1  5009.1  287.79  5032.3  286.39  5042.3  287.26  5050.3  291.26
  5063.2  293.89  5083.8  295.64  5302.9  300.29  5591.5  300.24  5750.1  301.86
#Mann= 5 ,-1 , 0
  4141.1     .05       0  4864.7     .12       0  4985.2     .07       0
  4991.2     .12       0  5042.3      .1       0
Bank Sta=4642.9,5050.3
XS Rating Curve= 0 ,0
Exp/Cntr=0.3,0.1

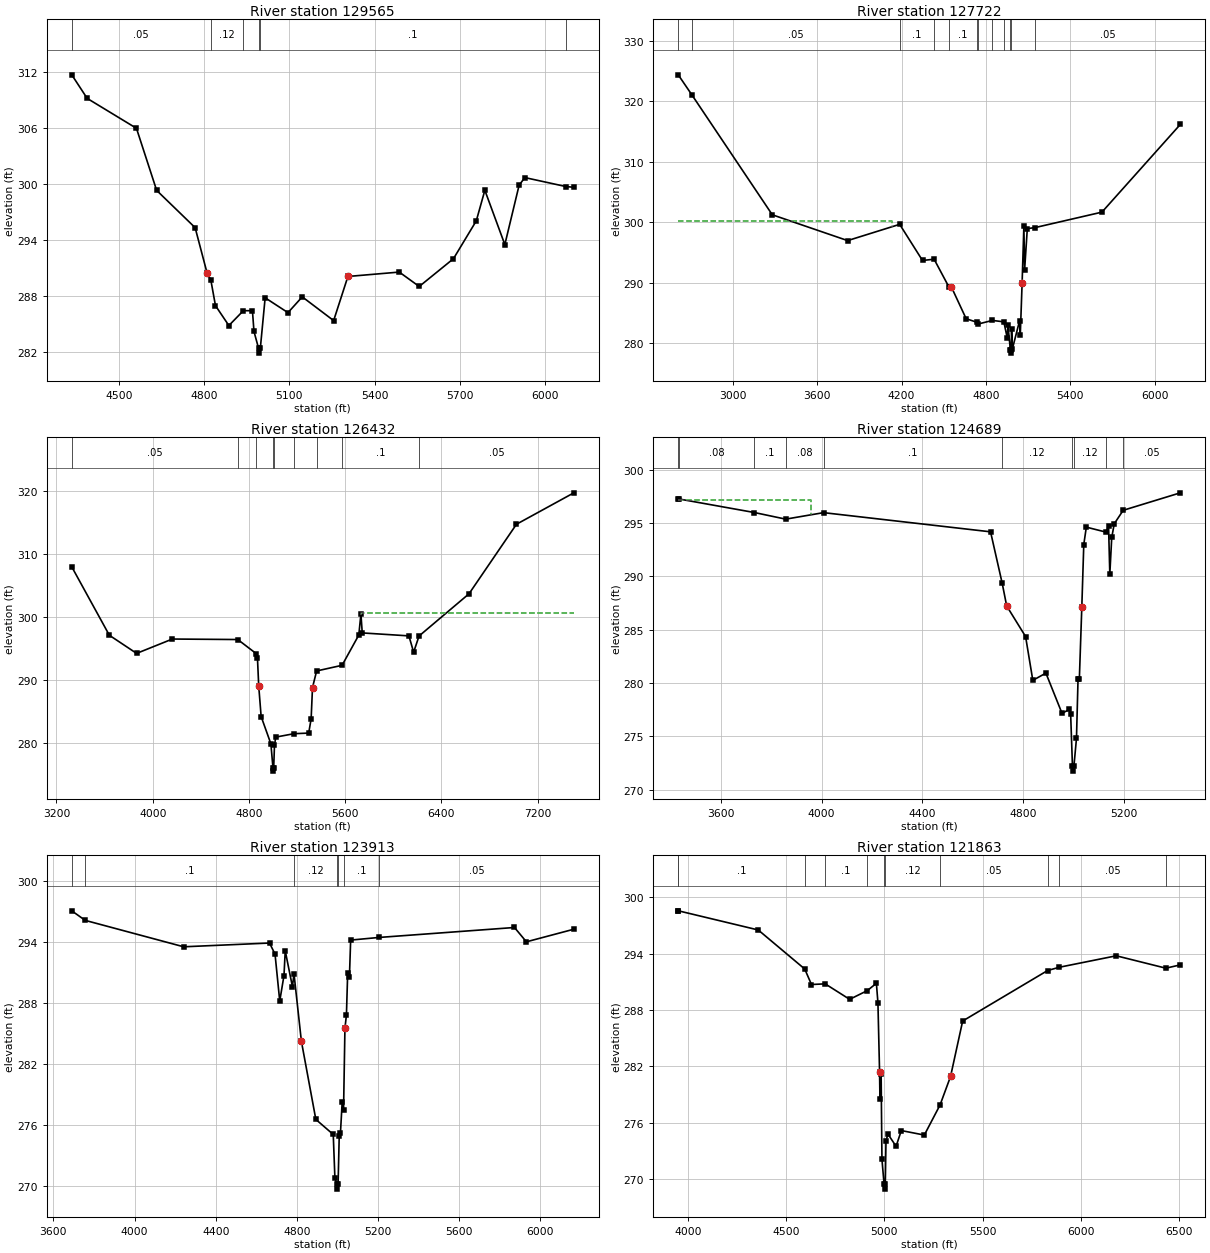
Type RM Length L Ch R = 1 ,129565  ,1843,1843,1843
BEGIN DESCRIPTION:
SULPHUR CREEK 126.0
END DESCRIPTION:
XS GIS Cut Line= 3
      2277137.74     13418646.82      2276887.72     13419246.85
      2276795.06     13420358.76
#Sta/Elev= 30
  4334.9  311.66  4389.1  309.14  4562.4  305.94  4633.4   299.3  4768.8  295.31
  4811.1  290.42  4823.8  289.74  4840.3  286.97  4887.4  284.84  4938.4  286.43
  4970.3  286.43  4975.7  284.21    4992  282.39  4994.7  281.89    4998  282.39
    5015  287.81  5095.3  286.22  5145.5  287.91  5255.9  285.37  5306.1  290.09
  5486.7  290.56  5556.9  289.02  5677.3  291.99  5757.6  296.04  5787.7  299.31
    5858   293.5  5908.1  299.84  5928.2  300.67  6072.6  299.71  6100.7  299.63
#Mann= 6 ,-1 , 0
  4334.9     .05       0  4823.8     .12       0  4938.4      .1       0
    4992     .07       0    4998      .1       0  6072.6     .05       0
Bank Sta=4811.1,5306.1
XS Rating Curve= 0 ,0
Exp/Cntr=0.3,0.1

Type RM Length L Ch R = 1 ,127722  ,1290,1290,1290
BEGIN DESCRIPTION:
SULPHUR CREEK 125.0
END DESCRIPTION:
XS GIS Cut Line= 4
      2276804.18     13418104.42      2276125.75     13419564.81
      2275781.23     13420539.72      2276092.34     13421411.71
#Sta/Elev= 30
  2611.7  324.41    2708  321.12  3280.6  301.25  3816.3  296.98  4186.3  299.67
  4348.6  293.69  4431.2   293.9  4534.7  289.38  4552.9  289.36    4659  284.05
  4733.8  283.48  4741.8  283.16  4845.4  283.77  4927.1  283.54    4951  280.88
  4956.3  282.94  4973.6  278.86  4976.4  278.36  4979.6  278.86  4981.9  282.29
  4987.8  279.07  5038.5  283.68  5043.8  281.32 5056.82   289.9  5069.4  299.34
  5074.7  292.14  5093.8  298.96  5150.3  299.14  5624.5  301.69  6181.8   316.2
#Mann= 12 ,-1 , 0
  2611.7      .1       0    2708     .05       0  4186.3      .1       0
  4431.2     .12       0  4534.7      .1       0  4733.8     .12       0
  4741.8      .1       0  4845.4     .12       0  4927.1      .1       0
  4973.6     .07       0  4979.6      .1       0  5150.3     .05       0
#XS Ineff= 2 , 0
         4135.08  300.28
Permanent Ineff=
       T       T
Bank Sta=4552.9,5056.82
XS Rating Curve= 0 ,0
Exp/Cntr=0.3,0.1

Type RM Length L Ch R = 1 ,126432  ,1743,1743,1743
BEGIN DESCRIPTION:
SULPHUR CREEK 124.0
END DESCRIPTION:
XS GIS Cut Line= 4
      2276264.44     13418051.78      2275457.14     13418898.14
      2275274.85     13420004.91      2276042.49     13421722.34
#Sta/Elev= 30
  3327.5  307.99  3639.8  297.13  3866.3  294.25  4163.5  296.53  4707.3  296.45
  4861.2   294.2  4870.8  293.46    4881  289.12  4901.2  284.23  4982.3  279.89
  4999.6  276.06  5002.3  275.56  5005.6  276.06  5012.1  279.67  5022.8  280.96
  5173.4   281.5  5296.5   281.6  5316.7  283.85  5328.1  288.83  5362.3  291.46
  5573.9  292.36  5712.8  297.16  5730.5  300.51  5741.5   297.5  6129.3  297.03
  6168.6  294.44  6213.5  297.01  6628.7  303.71    7023  314.75    7500  319.74
#Mann= 9 ,-1 , 0
  3327.5     .05       0  4707.3      .1       0  4861.2     .12       0
  4999.6     .07       0  5005.6     .12       0  5173.4      .1       0
  5362.3     .12       0  5573.9      .1       0  6213.5     .05       0
#XS Ineff= 2 , 0
                         5729.84          300.65
Permanent Ineff=
       T       T
Bank Sta=4881,5328.1
XS Rating Curve= 0 ,0
Exp/Cntr=0.3,0.1

Type RM Length L Ch R = 1 ,124689  ,776,776,776
BEGIN DESCRIPTION:
SULPHUR CREEK 123.0
END DESCRIPTION:
XS GIS Cut Line= 3
      2275037.71     13418646.88      2274387.72     13420096.85
      2274437.72     13420496.85
#Sta/Elev= 30
  3431.4  297.27  3434.7  297.27  3733.8     296  3857.8  295.38  4007.9  295.99
  4670.6  294.19  4716.8  289.36  4734.6  287.23  4809.6  284.36  4838.3  280.25
  4890.2  280.93  4954.2  277.15  4982.9  277.52  4988.4  277.08  4995.5  272.23
  4998.2  271.73  5001.5  272.23  5011.5   274.8  5017.7  280.37  5022.9  280.37
 5032.67  287.12  5040.5     293  5050.6  294.63  5127.4  294.17  5138.8  294.72
  5143.8  290.21  5151.4  293.66  5161.5  294.95  5196.9  296.21  5423.5  297.85
#Mann= 10 ,-1 , 0
  3431.4      .1       0  3434.7     .08       0  3733.8      .1       0
  3857.8     .08       0  4007.9      .1       0  4716.8     .12       0
  4995.5     .07       0  5001.5     .12       0  5127.4      .1       0
  5196.9     .05       0
#XS Ineff= 2 , 0
         3958.27   297.2
Permanent Ineff=
       T       T
Bank Sta=4734.6,5032.67
XS Rating Curve= 0 ,0
Exp/Cntr=0.3,0.1

Type RM Length L Ch R = 1 ,123913  ,2050,2050,2050
BEGIN DESCRIPTION:
Mapping XS b80bc35e
END DESCRIPTION:
XS GIS Cut Line= 4
      2274980.74     13418549.28      2274690.13     13418945.45
      2273683.18     13419674.62      2273813.92     13420402.71
#Sta/Elev= 30
  3690.7  297.07    3757  296.13  4242.3  293.53  4665.3   293.9  4692.4  292.81
  4715.6  288.19  4736.5   290.7  4742.7  293.13  4778.2   289.6  4785.8  290.88
  4822.3  284.23  4893.5  276.54  4979.3  275.06  4987.5  270.76  4997.2  270.18
  4999.9  269.68  5003.2  270.18  5008.7  274.88  5014.9  275.24  5023.4  278.28
  5030.1  277.51  5036.9  285.51  5044.3  286.83  5050.4  290.94    5059  290.54
  5065.1  294.19  5205.1  294.45  5872.4  295.43  5931.2  294.02    6165  295.26
#Mann= 7 ,-1 , 0
  3690.7     .08       0    3757      .1       0  4785.8     .12       0
  4997.2     .07       0  5003.2     .12       0  5030.1      .1       0
  5205.1     .05       0
Bank Sta=4822.3,5036.9
XS Rating Curve= 0 ,0
Exp/Cntr=0.3,0.1

Type RM Length L Ch R = 1 ,121863  ,1051,1051,1051
BEGIN DESCRIPTION:
SULPHUR CREEK 122.0
END DESCRIPTION:
XS GIS Cut Line= 4
      2274187.71     13416646.89      2273803.49     13417478.87
       2273661.8     13418078.42      2273683.54     13419103.01
#Sta/Elev= 30
  3950.1  298.58  3951.1  298.58  4357.6  296.54  4594.5  292.38  4628.7  290.73
  4698.6   290.8  4823.2  289.15  4913.1  290.08  4959.4  290.86  4967.2   288.8
 4975.57  281.43  4977.5  278.56 4983.52  281.16  4987.7   272.1  4998.7  269.43
  5001.5  268.93  5004.7  269.43  5008.3   274.1  5018.6  274.78  5059.7  273.49
  5086.3  275.17  5203.5  274.69  5283.7   277.9  5337.1  280.93  5398.8  286.84
  5831.4  292.22  5891.5  292.57  6181.2  293.79  6433.7  292.47  6507.4  292.82
#Mann= 11 ,-1 , 0
  3950.1     .05       0  3951.1      .1       0  4594.5     .08       0
  4698.6      .1       0  4913.1     .12       0  4998.7     .07       0
  5004.7     .12       0  5283.7     .05       0  5831.4      .1       0
  5891.5     .05       0  6433.7      .1       0
Bank Sta=4975.57,5337.1
XS Rating Curve= 0 ,0
Exp/Cntr=0.3,0.1

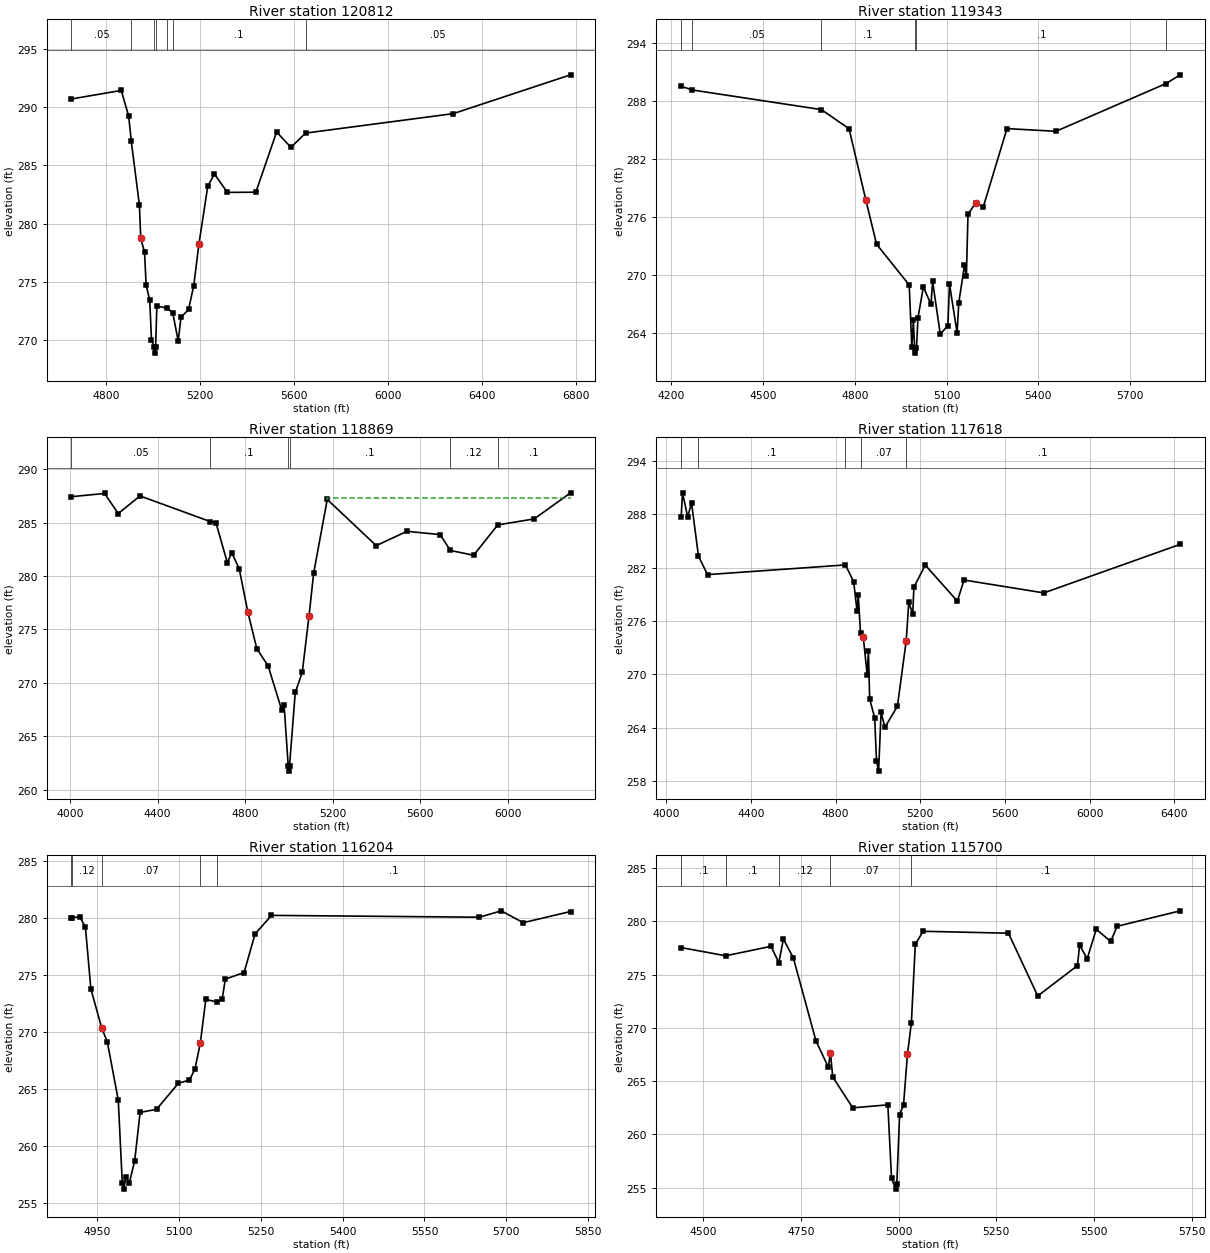
Type RM Length L Ch R = 1 ,120812  ,1469,1469,1469
BEGIN DESCRIPTION:
SULPHUR CREEK 121.0
END DESCRIPTION:
XS GIS Cut Line= 3
      2272640.28     13417383.29       2272683.7       13417557.
      2273504.45     13419322.38
#Sta/Elev= 30
  4651.1  290.69  4863.1  291.42  4894.8  289.21  4905.8  287.05  4940.3  281.61
  4946.1  278.73  4962.3  277.54    4969  274.74  4984.4  273.41  4991.9     270
  5003.4  269.38  5006.2  268.88  5009.4  269.38  5014.8  272.91  5058.5  272.75
  5082.5  272.34  5105.7  269.92  5117.4  271.94  5149.8  272.63  5171.9  274.67
  5193.9  278.24  5231.8  283.22  5260.2  284.25  5315.2  282.67  5436.5  282.69
  5524.8  287.85  5586.1  286.54  5648.2  287.76  6277.5  289.43    6777  292.76
#Mann= 7 ,-1 , 0
  4651.1     .05       0  4905.8      .1       0  5003.4     .07       0
  5009.4      .1       0  5058.5     .12       0  5082.5      .1       0
  5648.2     .05       0
Bank Sta=4946.1,5193.9
XS Rating Curve= 0 ,0
Exp/Cntr=0.3,0.1

Type RM Length L Ch R = 1 ,119343  ,474,474,474
BEGIN DESCRIPTION:
SULPHUR CREEK 120.0
END DESCRIPTION:
XS GIS Cut Line= 3
      2272137.73     13417946.81      2271937.72     13418696.85
      2272737.76     13418996.87
#Sta/Elev= 30
  4232.8  289.51  4269.1  289.13  4690.6   287.1  4781.4  285.12  4836.4  277.71
  4871.3  273.15    4978  268.93  4986.4  262.52  4991.6  265.27  4995.7  262.37
  4998.5  261.87  5001.7  262.37  5006.5  265.51  5024.2  268.73  5049.1  266.92
  5054.4  269.31  5079.4  263.82  5104.3  264.73  5109.6  269.02  5134.5  263.97
  5139.9  267.09  5158.6  270.95  5164.8  269.88  5170.1  276.24  5195.1  277.44
    5220  277.01  5297.4  285.13  5457.6  284.85  5817.4   289.8  5863.5   290.7
#Mann= 6 ,-1 , 0
  4232.8      .1       0  4269.1     .05       0  4690.6      .1       0
  4995.7     .07       0  5001.7      .1       0  5817.4     .05       0
Bank Sta=4836.4,5195.1
XS Rating Curve= 0 ,0
Exp/Cntr=0.3,0.1

Type RM Length L Ch R = 1 ,118869  ,1251,1251,1251
BEGIN DESCRIPTION:
SULPHUR CREEK 119.0
END DESCRIPTION:
XS GIS Cut Line= 3
      2271756.41     13417711.23      2271419.56      13418928.3
      2271354.15     13419942.17
#Sta/Elev= 30
  4006.7  287.42  4157.8  287.72  4220.1  285.84  4319.5  287.49  4640.5  285.09
  4666.2     285  4718.1  281.26  4738.8  282.16  4772.7  280.67  4812.2   276.6
    4853   273.2  4904.9  271.57  4967.1  267.43  4977.5  267.97  4996.3  262.24
  4999.1  261.74  5002.3  262.24  5028.5   269.1  5060.5  270.98  5091.6   276.3
  5112.6  280.27  5174.6  287.16  5398.3  282.84  5538.6  284.18  5690.2  283.87
  5736.8  282.39    5843  281.94  5953.4  284.78  6119.8  285.34  6285.5  287.78
#Mann= 6 ,-1 , 0
  4006.7     .05       0  4640.5      .1       0  4996.3     .07       0
  5002.3      .1       0  5736.8     .12       0  5953.4      .1       0
#XS Ineff= 2 , 0
                         5173.97          287.29
Permanent Ineff=
       T       T
Bank Sta=4812.2,5091.6
XS Rating Curve= 0 ,0
Exp/Cntr=0.3,0.1

Type RM Length L Ch R = 1 ,117618  ,1479,1479,1479
BEGIN DESCRIPTION:
Mapping XS 772b3f79
END DESCRIPTION:
XS GIS Cut Line= 3
      2270653.34     13417531.51       2270202.6     13418648.73
      2270384.89     13419785.89
#Sta/Elev= 30
  4070.8  287.72  4077.2  290.43  4101.4  287.72  4119.7  289.29  4152.6  283.29
  4195.2  281.22  4846.3  282.31  4885.3  280.43  4901.2  277.13  4906.9  278.94
  4917.6  274.67  4930.8  274.15  4949.5  269.86  4954.9  272.63  4960.8  267.23
  4984.5   265.1  4993.1  260.26    5003  259.09  5014.7  265.71  5032.8  264.02
  5091.8  266.39  5133.3  273.73  5145.5  278.09  5164.3   276.8  5169.7  279.81
  5223.4  282.29  5374.9  278.24  5406.5  280.61  5783.4  279.16  6427.2  284.63
#Mann= 5 ,-1 , 0
  4070.8     .08       0  4152.6      .1       0  4846.3     .12       0
  4917.6     .07       0  5133.3      .1       0
Bank Sta=4930.8,5133.3
XS Rating Curve= 0 ,0
Exp/Cntr=0.3,0.1

Type RM Length L Ch R = 1 ,116204  ,943,943,943
BEGIN DESCRIPTION:
Mapping XS 31fbf3b0
END DESCRIPTION:
XS GIS Cut Line= 2
      2269318.07     13417631.42      2269268.37     13418543.36
#Sta/Elev= 30
    4904  280.01  4904.1  280.01  4919.5  280.06  4929.5  279.14  4939.5  273.74
  4959.5  270.29  4969.5  269.12  4989.6     264    4997  256.69  4999.8  256.19
  5003.5  257.28  5009.6  256.69  5019.6  258.67  5029.6  262.92  5059.7  263.19
  5099.7  265.48  5119.8  265.75  5129.8   266.7  5139.8  269.01  5149.8  272.83
  5170.6   272.6  5179.8  272.84  5185.5  274.61  5219.9  275.19  5239.9  278.56
    5270   280.2  5650.5  280.04  5690.6   280.6  5730.7  279.56  5817.3  280.54
#Mann= 5 ,-1 , 0
    4904      .1       0  4904.1     .12       0  4959.5     .07       0
  5139.8     .12       0  5170.6      .1       0
Bank Sta=4959.5,5139.8
XS Rating Curve= 0 ,0
Exp/Cntr=0.3,0.1

Type RM Length L Ch R = 1 ,115700  ,885,885,885
BEGIN DESCRIPTION:
Mapping XS 427dbb17
END DESCRIPTION:
XS GIS Cut Line= 3
      2268862.81     13417328.49      2268806.67     13417933.59
      2269006.28     13418457.56
#Sta/Elev= 30
  4443.7  277.53  4557.7  276.76  4673.7  277.65  4693.6  276.11  4705.3  278.33
  4730.6  276.58  4788.7  268.77  4820.3   266.3  4825.6  267.64  4831.6  265.39
  4882.7  262.49  4972.6  262.77    4982   255.9  4992.4  254.86  4995.6  255.36
  5002.7  261.85  5012.7  262.75  5022.8  267.52  5032.8  270.47  5042.9  277.84
  5062.9  279.06  5281.3  278.88  5356.2  272.99  5457.9  275.84  5463.3  277.77
  5482.7  276.48    5506  279.25  5542.9  278.11  5559.5  279.53  5720.8  280.98
#Mann= 5 ,-1 , 0
  4443.7      .1       0  4557.7      .1       0  4693.6     .12       0
  4825.6     .07       0  5032.8      .1       0
#XS Ineff= 2 , 0
                         5118.81          278.79
Permanent Ineff=
       T       T
Bank Sta=4825.6,5022.8
XS Rating Curve= 0 ,0
Exp/Cntr=0.3,0.1

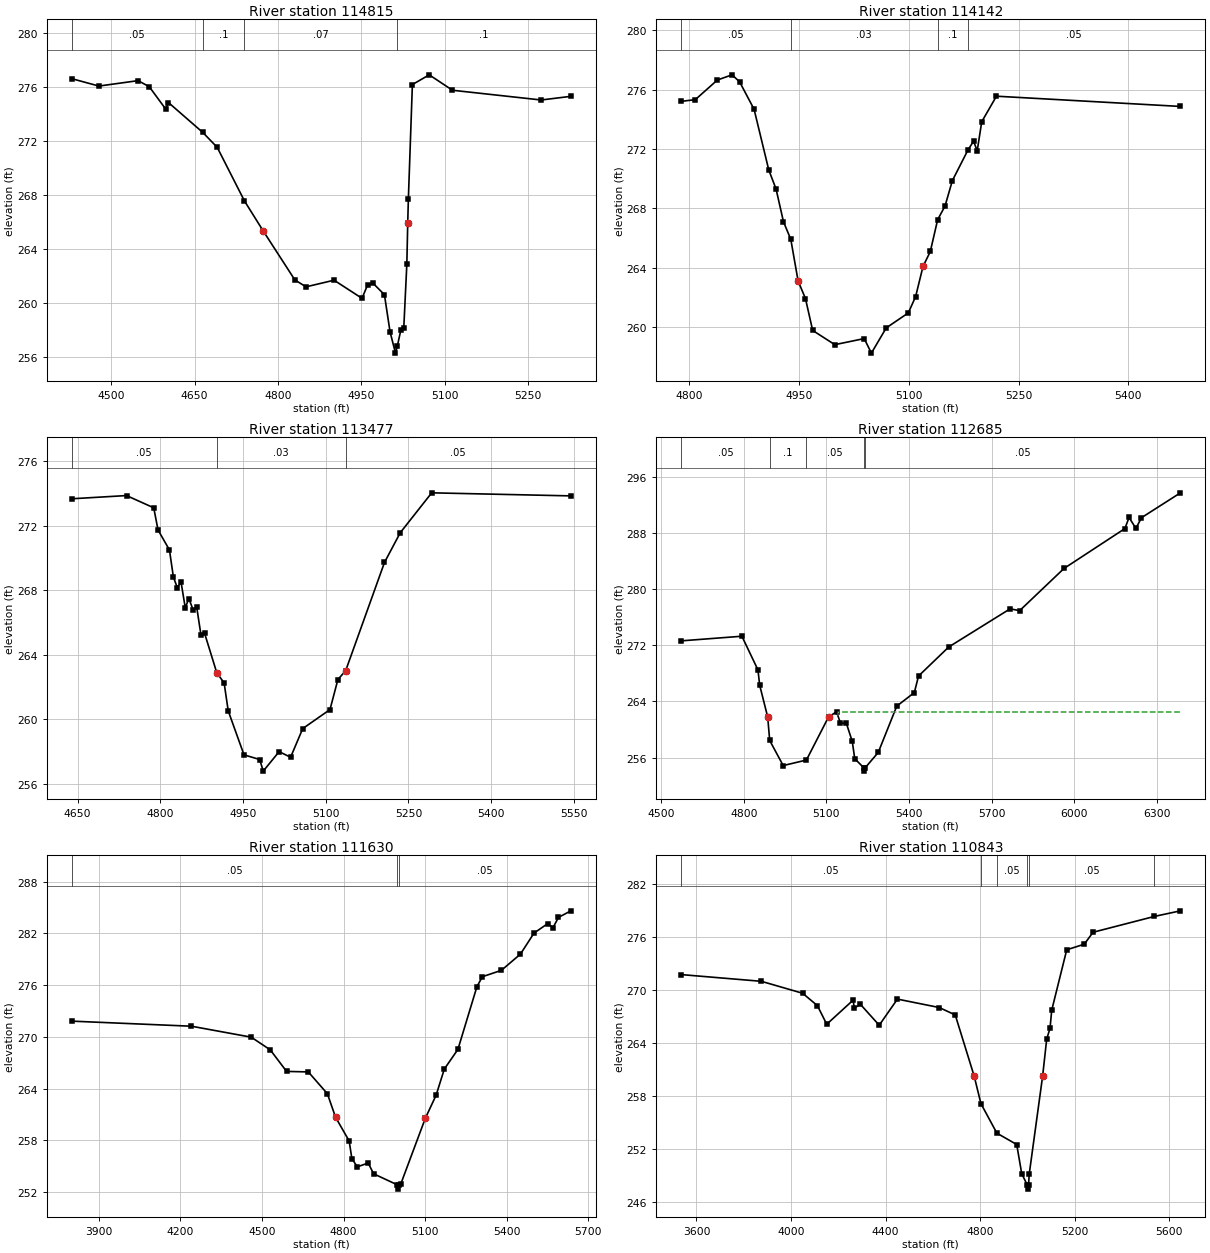
Type RM Length L Ch R = 1 ,114815  ,673,673,673
BEGIN DESCRIPTION:
Mapping XS e6daa8ad
END DESCRIPTION:
XS GIS Cut Line= 2
      2268806.68     13417141.36      2267914.66      13417247.4
#Sta/Elev= 30
  4428.7  276.61    4478  276.06  4548.5  276.46  4568.6  276.01  4598.1  274.36
  4603.1  274.84  4664.9  272.63  4690.8  271.53  4739.8  267.57  4773.4  265.36
  4830.5  261.73  4850.6  261.22    4901  261.71  4951.3  260.37  4961.4  261.37
  4971.5  261.47  4991.6  260.64  5001.7   257.9  5011.5  256.32  5014.7  256.82
  5021.3  258.06  5026.4  258.16  5031.9  262.88 5033.52  265.92 5034.66   267.7
  5041.9  276.17  5072.2  276.89    5114  275.75  5273.6  275.03    5327   275.3
#Mann= 4 ,-1 , 0
  4428.7     .05       0  4664.9      .1       0  4739.8     .07       0
  5014.7      .1       0
Bank Sta=4773.4,5033.52
XS Rating Curve= 0 ,0
Exp/Cntr=0.3,0.1

Type RM Length L Ch R = 1 ,114142  ,665,665,665
BEGIN DESCRIPTION:
SULPHUR CREEK 118.0
END DESCRIPTION:
XS GIS Cut Line= 2
      2268607.09     13416554.97      2267927.15     13416617.35
#Sta/Elev= 30
  4788.5   275.2    4808  275.32  4838.1  276.64  4858.2  276.99  4868.5  276.52
  4888.3  274.67  4908.4  270.58  4918.4  269.29  4928.5  267.09  4938.5  265.91
  4948.5   263.1  4958.6  261.91  4968.4  259.77  4998.7  258.81  5038.9  259.22
  5048.7  258.24    5069  259.94  5099.2  260.95  5109.2  262.05  5119.3  264.08
  5129.3  265.09  5139.3  267.23  5149.4  268.15  5159.4  269.86  5180.6  271.91
  5188.4  272.52  5193.4  271.87  5199.6  273.83  5219.7  275.55  5471.3  274.86
#Mann= 4 ,-1 , 0
  4788.5     .05       0  4938.5     .03       0  5139.3      .1       0
  5180.6     .05       0
Bank Sta=4948.5,5119.3
XS Rating Curve= 0 ,0
Exp/Cntr=0.3,0.1

Type RM Length L Ch R = 1 ,113477  ,792,792,792
BEGIN DESCRIPTION:
SULPHUR CREEK 117.0
END DESCRIPTION:
XS GIS Cut Line= 3
      2268257.74     13415806.38      2267821.05     13416317.93
      2267721.96     13416528.49
#Sta/Elev= 30
  4639.1  273.68  4738.8  273.88  4788.2  273.12  4795.9  271.75  4816.7   270.5
  4823.8  268.82    4831  268.16  4837.6  268.53  4845.3  266.92  4851.9  267.49
  4859.6  266.78  4866.1  266.95  4873.8  265.23  4880.4  265.33  4902.4  262.89
  4915.8  262.25  4923.2  260.52  4951.8  257.79  4980.3   257.5  4986.7  256.78
  5015.5  257.99  5036.3  257.64  5058.3  259.42  5107.7   260.6    5122  262.46
  5136.2  263.02  5206.5  269.73    5235  271.57  5292.1  274.05  5544.4  273.86
#Mann= 3 , 0 , 0
  4639.1     .05       0  4902.4     .03       0  5136.2     .05       0
Bank Sta=4902.4,5136.2
XS Rating Curve= 0 ,0
Exp/Cntr=0.3,0.1

Type RM Length L Ch R = 1 ,112685  ,1055,1055,1055
BEGIN DESCRIPTION:
Mapping XS 7cda2033
END DESCRIPTION:
XS GIS Cut Line= 4
      2267652.65     13415581.81        2267191.     13415931.17
      2266773.05     13416193.17      2266036.97     13416124.55
#Sta/Elev= 30
  4572.9  272.61  4793.5  273.27  4851.7  268.48    4858   266.3  4887.1  261.77
  4894.3  258.44  4943.3  254.86  5027.6  255.65  5107.7  261.77  5136.8  262.52
  5150.8  260.93  5172.7  260.85  5193.9  258.29  5202.9  255.83  5235.3  254.57
  5238.1  254.07  5241.3  254.57  5288.2  256.74  5355.3  263.32    5419  265.25
  5434.3  267.61  5543.9  271.74  5766.5  277.17  5801.1  276.91  5961.8  282.91
  6182.8  288.59  6197.9  290.17  6222.9  288.62    6243  290.14  6384.4  293.68
#Mann= 5 ,-1 , 0
  4572.9     .05       0  4894.3      .1       0  5027.6     .05       0
  5235.3     .07       0  5241.3     .05       0
#XS Ineff= 2 , 0
                         5142.15          262.46
Permanent Ineff=
       T       T
Bank Sta=4887.1,5107.7
XS Rating Curve= 0 ,0
Exp/Cntr=0.3,0.1

Type RM Length L Ch R = 1 ,111630  ,787,787,787
BEGIN DESCRIPTION:
SULPHUR CREEK 116.0
END DESCRIPTION:
XS GIS Cut Line= 3
      2267914.58     13415244.96      2267546.57     13415082.79
      2266112.25     13415064.08
#Sta/Elev= 30
  3799.3  271.82  4240.3  271.23  4460.3  269.96  4530.3  268.49  4590.3  265.99
  4670.3  265.93  4740.4   263.4  4770.4  260.68  4820.4  257.93  4830.4  255.89
  4850.4  254.92  4890.4  255.37  4910.4  254.12  4997.4  252.84  5000.1  252.34
  5003.4  252.84  5010.4  252.94  5100.4  260.54  5140.4  263.24  5170.4  266.26
  5220.4  268.54  5290.4  275.82  5310.4  276.97  5380.4  277.71  5450.4  279.59
  5500.4  282.03  5550.4  283.12  5570.4  282.67  5590.4  283.85  5635.9  284.61
#Mann= 3 ,-1 , 0
  3799.3     .05       0  4997.4     .03       0  5003.4     .05       0
Bank Sta=4770.4,5100.4
XS Rating Curve= 0 ,0
Exp/Cntr=0.3,0.1

Type RM Length L Ch R = 1 ,110843  ,774,774,774
BEGIN DESCRIPTION:
SULPHUR CREEK 115.0
END DESCRIPTION:
XS GIS Cut Line= 3
      2268457.35     13414933.08       2268058.1     13414733.45
       2266482.9     13414191.78
#Sta/Elev= 30
    3535  271.72  3874.4  270.96  4049.1  269.61  4111.6  268.21    4151  266.11
  4262.5  268.83  4267.8  267.95  4293.8  268.35    4373     266    4450  268.95
  4626.8     268  4694.6  267.16  4774.9  260.23  4803.1  257.15  4870.7  253.81
  4954.6  252.53  4975.8  249.23  4998.7  247.99  5001.4  247.49  5004.7  247.99
  5007.5  249.19  5064.1  260.24  5081.5  264.45  5095.4  265.64  5102.7   267.7
  5166.1  274.52  5240.2  275.15  5277.5   276.5  5537.3  278.29  5647.1  278.92
#Mann= 6 ,-1 , 0
    3535     .05       0  4803.1      .1       0  4870.7     .05       0
  4998.7     .03       0  5004.7     .05       0  5537.3      .1       0
Bank Sta=4774.9,5064.1
XS Rating Curve= 0 ,0
Exp/Cntr=0.3,0.1

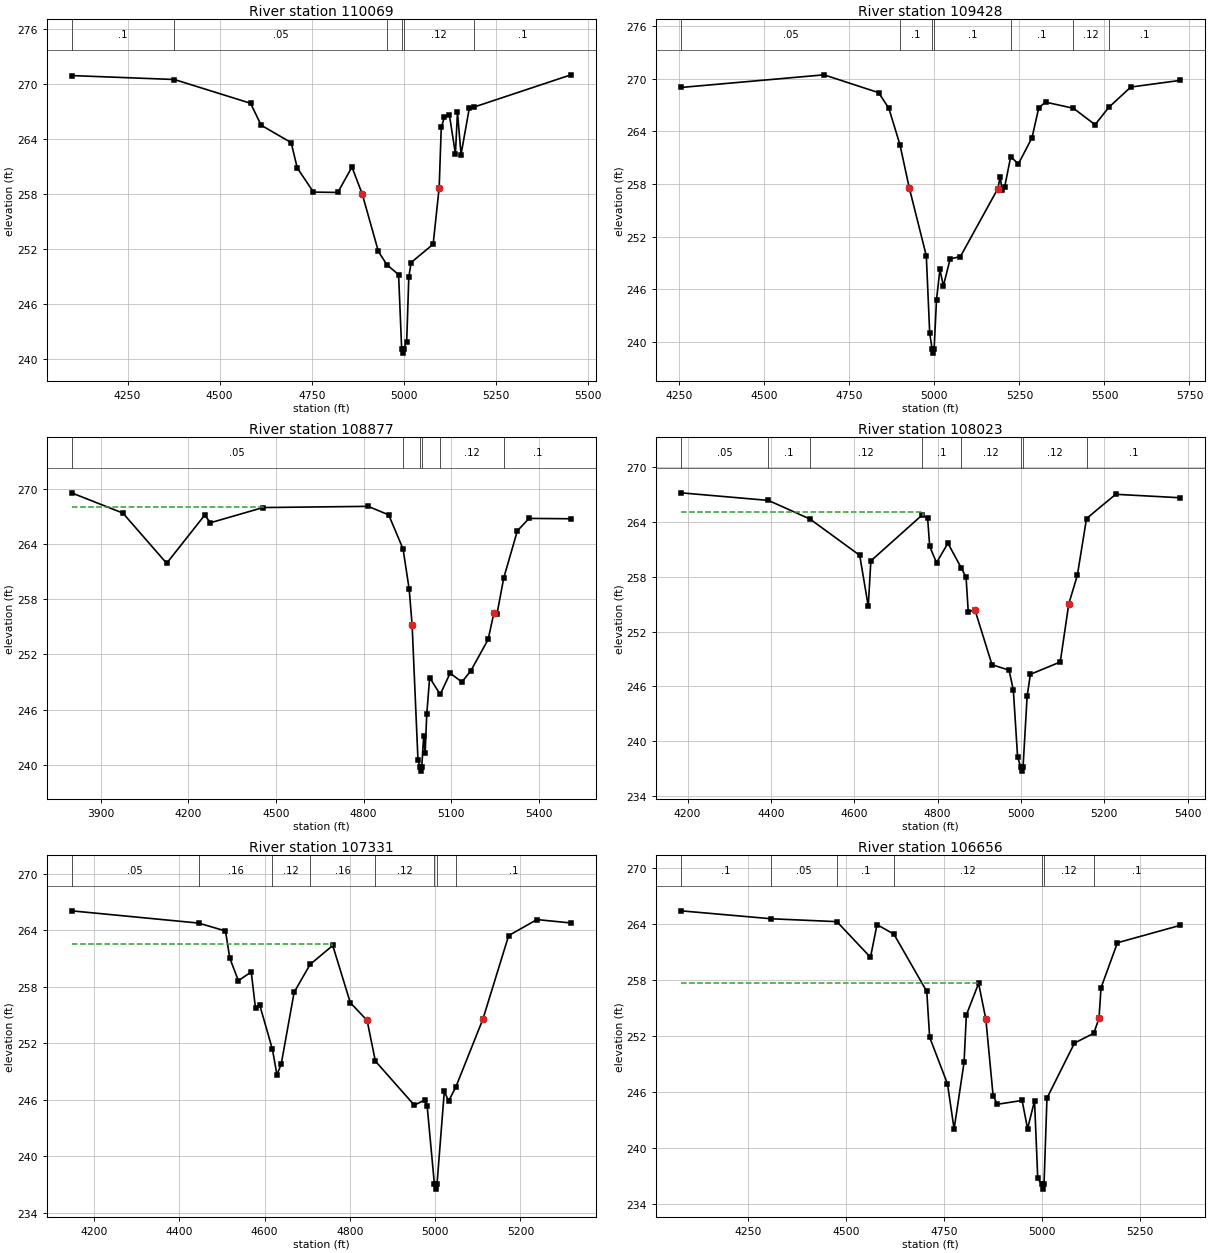
Type RM Length L Ch R = 1 ,110069  ,641,641,641
BEGIN DESCRIPTION:
SULPHUR CREEK 114.0
END DESCRIPTION:
XS GIS Cut Line= 3
      2268359.97       13414409.      2268157.65     13414157.83
      2267243.78     13413676.48
#Sta/Elev= 30
  4097.9   270.9  4376.9  270.47  4583.8  267.88  4612.5  265.49    4694  263.59
  4710.4  260.84  4754.4   258.2  4820.5  258.16  4858.9  260.93  4886.6  258.02
  4930.7  251.73  4953.4   250.3  4985.5   249.2  4993.8  241.15  4996.5  240.65
  4999.8  241.15  5007.5  241.91  5013.2  248.92  5019.4  250.52  5079.3  252.52
  5095.6  258.68  5101.3  265.24  5109.8  266.36  5123.3  266.63  5139.7  262.37
  5145.3   266.9    5155  262.29  5177.6   267.4  5190.4  267.47  5453.3  270.98
#Mann= 6 ,-1 , 0
  4097.9      .1       0  4376.9     .05       0  4953.4     .12       0
  4993.8     .07       0  4999.8     .12       0  5190.4      .1       0
Bank Sta=4886.6,5095.6
XS Rating Curve= 0 ,0
Exp/Cntr=0.3,0.1

Type RM Length L Ch R = 1 ,109428  ,551,551,551
BEGIN DESCRIPTION:
SULPHUR CREEK 113.0
END DESCRIPTION:
XS GIS Cut Line= 3
      2268722.72     13413502.07      2268332.05     13413390.45
      2267272.22     13413313.75
#Sta/Elev= 30
  4254.6  268.99  4675.3  270.43  4835.7   268.4  4865.8  266.63  4898.5  262.48
  4925.9  257.57  4976.1  249.82  4986.1  240.99  4993.1  239.24  4995.9  238.74
  4999.1  239.24  5006.1  244.83  5016.2  248.27  5026.2  246.38  5046.2  249.47
  5076.3  249.73  5186.6  257.48  5193.6  258.85  5198.6  257.28  5206.7  257.68
  5224.3  261.11  5246.8  260.28  5286.9  263.26  5306.9  266.69    5327  267.32
  5408.9  266.62  5472.5  264.75  5512.6  266.72  5577.6  269.04  5723.5   269.8
#Mann= 7 ,-1 , 0
  4254.6     .05       0  4898.5      .1       0  4993.1     .07       0
  4999.1      .1       0  5224.3      .1       0  5408.9     .12       0
  5512.6      .1       0
Bank Sta=4925.9,5186.6
XS Rating Curve= 0 ,0
Exp/Cntr=0.3,0.1

Type RM Length L Ch R = 1 ,108877  ,854,854,854
BEGIN DESCRIPTION:
SULPHUR CREEK 112.0
END DESCRIPTION:
XS GIS Cut Line= 3
      2269343.55     13412895.14      2268555.29     13412874.21
      2267634.42     13412825.38
#Sta/Elev= 30
  3799.8  269.56  3975.7  267.36  4125.7   261.9  4255.8  267.13  4275.8  266.31
  4455.9  267.96  4816.2  268.09  4886.3  267.16  4935.4  263.45  4956.4  259.07
  4966.4  255.19  4986.5  240.48  4993.5  239.81  4996.2  239.31  4999.5  239.81
    5006  243.11    5011  241.29  5016.5  245.49  5026.5  249.48  5062.6  247.64
  5096.6  249.96  5136.7     249  5166.7  250.17  5226.8  253.62  5246.8  256.55
  5256.8  256.34  5280.1  260.29  5326.9  265.43    5367  266.78  5510.5  266.74
#Mann= 6 ,-1 , 0
  3799.8     .05       0  4935.4      .1       0  4993.5     .07       0
  4999.5      .1       0  5062.6     .12       0  5280.1      .1       0
#XS Ineff= 2 , 0
         4454.55  267.98
Permanent Ineff=
       T       T
Bank Sta=4966.4,5246.8
XS Rating Curve= 0 ,0
Exp/Cntr=0.3,0.1

Type RM Length L Ch R = 1 ,108023  ,692,692,692
BEGIN DESCRIPTION:
SULPHUR CREEK 111.0
END DESCRIPTION:
XS GIS Cut Line= 3
      2269176.19     13412406.83      2269057.57     13412295.19
        2268046.     13412071.95
#Sta/Elev= 30
  4184.1  267.16    4394  266.33  4493.9  264.29  4613.1  260.33  4633.6  254.76
  4639.8  259.72  4761.8  264.69    4776  264.45  4781.1   261.3  4797.4  259.52
  4824.8  261.65  4856.9  258.95  4868.4  257.91  4873.6  254.15  4889.6  254.37
  4930.6  248.37  4971.5  247.78  4981.8   245.6    4992  238.32  4999.2  237.24
    5002  236.74  5005.2  237.24  5014.9  244.92  5022.7  247.32  5094.4  248.67
  5114.9  255.02  5135.4  258.14  5157.5  264.35  5227.5     267  5382.9  266.62
#Mann= 8 ,-1 , 0
  4184.1     .05       0    4394      .1       0  4493.9     .12       0
  4761.8      .1       0  4856.9     .12       0  4999.2     .07       0
  5005.2     .12       0  5157.5      .1       0
#XS Ineff= 2 , 0
         4765.23  265.01
Permanent Ineff=
       T       T
Bank Sta=4889.6,5114.9
XS Rating Curve= 0 ,0
Exp/Cntr=0.3,0.1

Type RM Length L Ch R = 1 ,107331  ,675,675,675
BEGIN DESCRIPTION:
SULPHUR CREEK 110.0
END DESCRIPTION:
XS GIS Cut Line= 3
       2269413.4      13411681.3      2269183.15     13411597.57
      2268262.47     13411492.95
#Sta/Elev= 30
  4146.9  266.04  4444.9  264.74  4508.1   263.9  4518.1  261.03  4538.3  258.62
  4568.5  259.55  4578.5  255.68  4588.6     256  4618.2  251.33  4628.8  248.62
  4638.9  249.79  4669.1  257.39  4706.6  260.35  4759.7  262.36  4800.9  256.28
  4840.2  254.41  4859.7  250.08  4950.9  245.41    4975  245.93  4981.1  245.32
  4998.2  236.99    5001  236.49  5004.2  236.99  5021.4  246.89  5031.4  245.84
  5048.3  247.32  5111.9  254.54  5172.3  263.41  5238.7  265.11  5318.5  264.75
#Mann= 8 ,-1 , 0
  4146.9     .05       0  4444.9     .16       0  4618.2     .12       0
  4706.6     .16       0  4859.7     .12       0  4998.2     .07       0
  5004.2     .12       0  5048.3      .1       0
#XS Ineff= 2 , 0
         4758.86  262.55
Permanent Ineff=
       T       T
Bank Sta=4840.2,5111.9
XS Rating Curve= 0 ,0
Exp/Cntr=0.3,0.1

Type RM Length L Ch R = 1 ,106656  ,571,571,571
BEGIN DESCRIPTION:
SULPHUR CREEK 109.0
END DESCRIPTION:
XS GIS Cut Line= 3
      2269559.86      13411297.6      2269287.79     13411074.36
      2268415.78     13410774.38
#Sta/Elev= 30
  4078.2  265.46  4308.1  264.61  4475.9   264.3  4561.6  260.48  4578.3  263.98
  4621.4  262.96  4705.2  256.82  4712.5  251.92    4758  246.92  4774.9  242.08
  4800.3  249.22  4806.2   254.3  4837.4  257.69 4855.91  253.84  4874.4  245.66
  4884.9  244.73  4948.4  245.14  4962.3  242.11  4980.1   245.1  4988.3  236.79
  4998.3  236.14    5001  235.64  5004.3  236.14  5011.8  245.39    5082  251.29
  5131.2  252.34  5144.5  253.93  5149.7  257.21  5191.6  262.04  5352.3  263.91
#Mann= 7 ,-1 , 0
  4078.2      .1       0  4308.1     .05       0  4475.9      .1       0
  4621.4     .12       0  4998.3     .07       0  5004.3     .12       0
  5131.2      .1       0
#XS Ineff= 2 , 0
         4838.41  257.69
Permanent Ineff=
       T       T
Bank Sta=4855.91,5144.5
XS Rating Curve= 0 ,0
Exp/Cntr=0.3,0.1