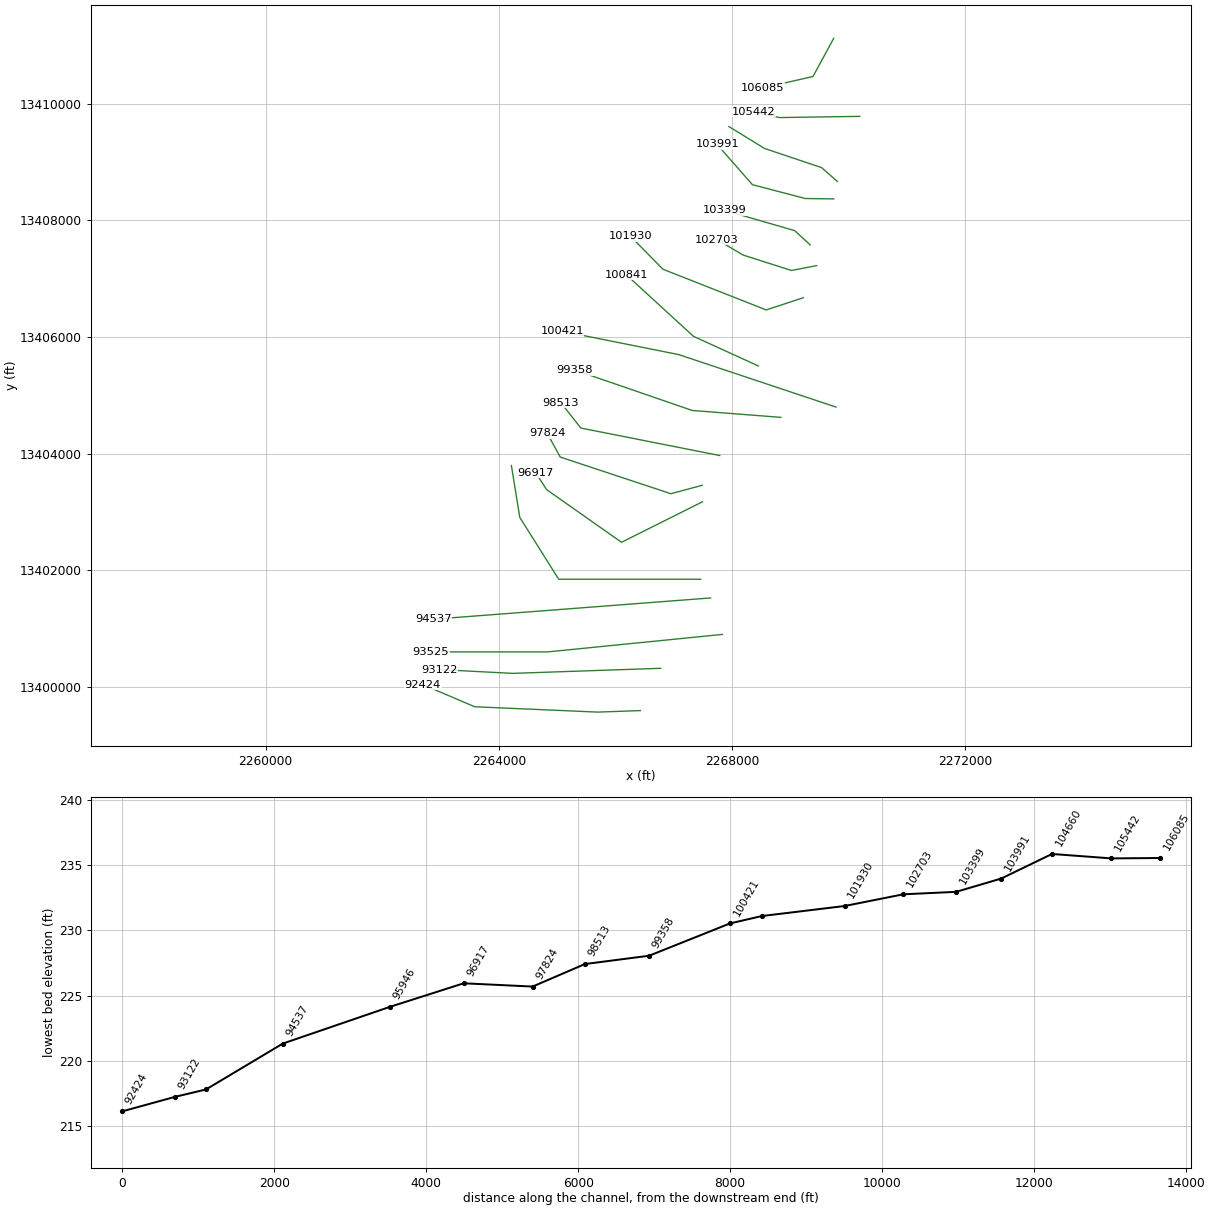
HEC-RAS study SULPHUR CREEK.prj: SULPHUR CREEK Base Level Engineering

--- SULPHUR CREEK.g01 (geometry) --- (continued)

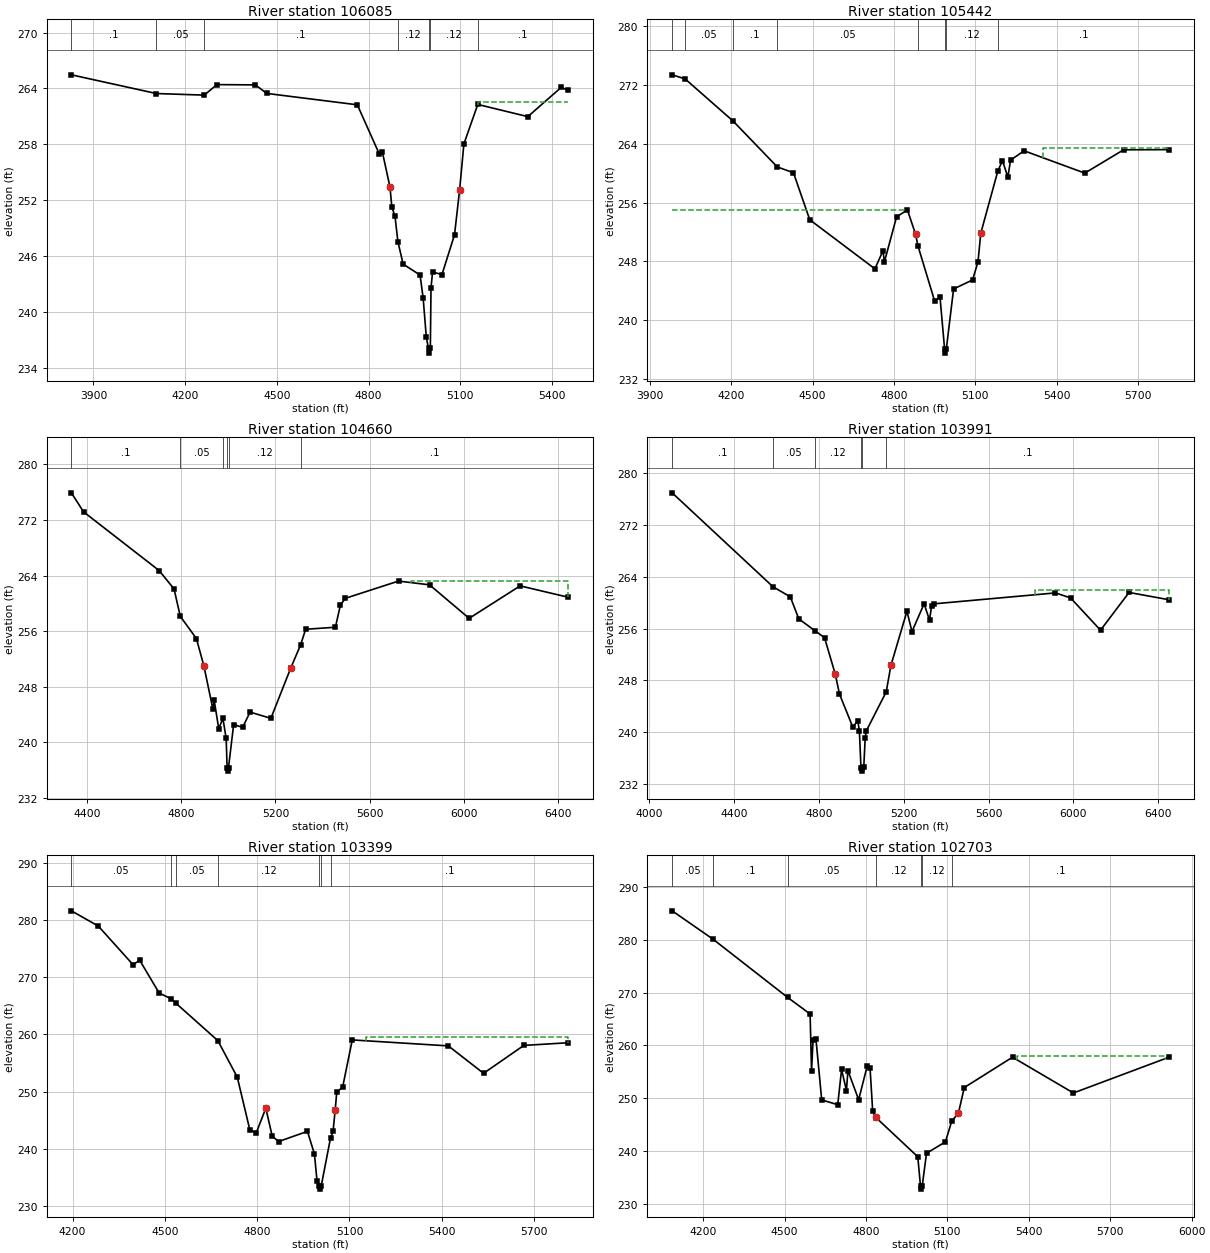
Type RM Length L Ch R = 1 ,106085  ,643,643,643
BEGIN DESCRIPTION:
SULPHUR CREEK 108.0
END DESCRIPTION:
XS GIS Cut Line= 3
      2269748.24     13411123.22      2269392.43     13410467.43
      2268534.38      13410272.1
#Sta/Elev= 30
  3827.8  265.46    4106  263.45  4262.5  263.28  4303.9  264.41  4429.4  264.38
  4467.5  263.46  4763.3  262.24  4835.1  256.96  4845.4  257.15  4870.2  253.39
  4876.2  251.25  4886.4   250.3  4896.1  247.54  4913.2  245.13  4968.5  243.96
  4978.7  241.49    4989  237.28  4996.2  236.07    4999  235.57  5002.2  236.07
  5004.4  242.59  5009.5  244.29  5040.2     244  5081.3  248.28 5097.84  253.05
    5112  258.04  5157.4  262.28  5321.1  260.97    5430   264.1  5453.9   263.8
#Mann= 7 ,-1 , 0
  3827.8      .1       0    4106     .05       0  4262.5      .1       0
  4896.1     .12       0  4996.2     .07       0  5002.2     .12       0
  5157.4      .1       0
#XS Ineff= 2 , 0
                            5157          262.59
Permanent Ineff=
       T       T
Bank Sta=4870.2,5097.84
XS Rating Curve= 0 ,0
Exp/Cntr=0.3,0.1

Type RM Length L Ch R = 1 ,105442  ,782,782,782
BEGIN DESCRIPTION:
SULPHUR CREEK 107.0
END DESCRIPTION:
XS GIS Cut Line= 3
      2270194.69     13409783.76      2268820.38     13409762.83
      2268373.91      13409860.5
#Sta/Elev= 30
  3982.5  273.37  4030.1  272.82  4206.9  267.09  4369.9  260.85  4429.5  260.06
  4489.5  253.67  4729.6     247  4759.5  249.47  4764.5  247.92  4809.6  254.08
  4849.6     255  4879.6  251.68    4888  250.15  4949.6  242.64  4969.6  243.13
  4986.6  236.04  4989.3  235.54  4992.6  236.04  5019.6  244.26  5089.6  245.49
  5109.6  247.96  5119.6  251.81  5182.4  260.26  5199.6  261.72  5219.6  259.47
  5229.6  261.78  5279.6  263.04    5503  260.01  5646.3  263.18    5814   263.2
#Mann= 8 ,-1 , 0
  3982.5      .1       0  4030.1     .05       0  4206.9      .1       0
  4369.9     .05       0    4888     .12       0  4986.6     .07       0
  4992.6     .12       0  5182.4      .1       0
#XS Ineff= 2 , 0
         4849.43  255.03 5349.36          263.49
Permanent Ineff=
       T       T
Bank Sta=4879.6,5119.6
XS Rating Curve= 0 ,0
Exp/Cntr=0.3,0.1

Type RM Length L Ch R = 1 ,104660  ,669,669,669
BEGIN DESCRIPTION:
SULPHUR CREEK 106.0
END DESCRIPTION:
XS GIS Cut Line= 4
      2269811.02     13408667.55      2269538.93     13408904.76
      2268562.26     13409232.64      2267948.34     13409609.37
#Sta/Elev= 30
    4333   275.9  4384.5  273.17  4705.8  264.72  4769.1  262.08  4795.6  258.14
    4864  254.95  4895.7  251.03  4934.4  244.76  4939.7  246.06    4959  241.98
  4976.7  243.46  4990.6  240.58  4994.5  236.38  4997.2  235.88  5000.5  236.38
  5022.3  242.58  5060.5  242.17  5092.1  244.37  5180.5  243.47  5264.9  250.71
  5306.4     254  5328.2  256.28  5454.7  256.57  5475.8  259.76  5496.7  260.73
  5722.7  263.21  5854.6  262.67  6022.8  257.85  6239.4  262.52  6444.5  260.88
#Mann= 6 ,-1 , 0
    4333      .1       0  4795.6     .05       0  4976.7     .12       0
  4994.5     .07       0  5000.5     .12       0  5306.4      .1       0
#XS Ineff= 2 , 0
                         5775.11          263.18
Permanent Ineff=
       T       T
Bank Sta=4895.7,5264.9
XS Rating Curve= 0 ,0
Exp/Cntr=0.3,0.1

Type RM Length L Ch R = 1 ,103991  ,592,592,592
BEGIN DESCRIPTION:
SULPHUR CREEK 105.0
END DESCRIPTION:
XS GIS Cut Line= 4
      2269748.24     13408367.59      2269259.88     13408374.57
      2268352.98     13408611.76      2267746.28     13409302.14
#Sta/Elev= 30
  4107.4  276.98  4583.4  262.46  4664.7  260.92  4705.1   257.5  4781.8  255.66
  4826.4   254.6  4877.1  248.95  4896.9  245.89  4959.8  240.79    4983   241.8
  4990.8  240.19  4998.2  234.49  5000.9  233.99  5004.2  234.49  5011.5   234.7
  5018.2  239.15  5023.4  240.21  5117.4  246.24  5139.5  250.32  5215.2  258.69
  5238.9  255.54  5296.1  259.84  5321.6  257.32  5331.4  259.47  5342.3  259.83
  5915.9  261.52    5987  260.75  6128.4  255.76  6263.1  261.59  6452.3  260.46
#Mann= 6 ,-1 , 0
  4107.4      .1       0  4583.4     .05       0  4781.8     .12       0
  4998.2     .07       0  5004.2     .12       0  5117.4      .1       0
#XS Ineff= 2 , 0
                         5821.08          261.93
Permanent Ineff=
       T       T
Bank Sta=4877.1,5139.5
XS Rating Curve= 0 ,0
Exp/Cntr=0.3,0.1

Type RM Length L Ch R = 1 ,103399  ,696,696,696
BEGIN DESCRIPTION:
SULPHUR CREEK 104.0
END DESCRIPTION:
XS GIS Cut Line= 3
      2269343.61     13407579.27       2269078.5     13407823.45
      2267872.87      13408171.9
#Sta/Elev= 30
  4196.1  281.58  4283.7  278.91  4396.5  272.17  4418.1  272.95  4481.6   267.2
  4519.1  266.26    4535  265.48  4671.9  258.92  4735.2  252.54  4775.9  243.36
  4796.8  242.77    4828  247.11  4848.8  242.23  4869.6  241.28  4963.3  243.06
  4986.1   239.1  4994.5  234.37  5001.9  233.47  5004.7  232.97  5007.9  233.47
  5038.3  241.89  5046.6  243.08  5053.4  246.74  5058.6  249.91  5077.8   250.8
    5109  259.03  5421.3  257.99  5535.8   253.2  5666.6  258.07  5811.5  258.54
#Mann= 7 ,-1 , 0
  4196.1     .05       0  4519.1     .16       0    4535     .05       0
  4671.9     .12       0  5001.9     .07       0  5007.9     .12       0
  5038.3      .1       0
#XS Ineff= 2 , 0
                         5154.17          259.53
Permanent Ineff=
       T       T
Bank Sta=4828,5053.4
XS Rating Curve= 0 ,0
Exp/Cntr=0.3,0.1

Type RM Length L Ch R = 1 ,102703  ,773,773,773
BEGIN DESCRIPTION:
SULPHUR CREEK 103.0
END DESCRIPTION:
XS GIS Cut Line= 4
      2269455.21      13407223.5      2269022.69     13407139.79
      2268192.53     13407404.88      2267746.01       13407670.
#Sta/Elev= 30
  4085.8  285.49  4236.3  280.12  4511.3  269.09  4594.1  265.95  4599.4  255.08
    4605  261.11  4615.5  261.29  4636.8  249.68  4695.9  248.77    4710  255.44
  4728.1  251.45  4733.3  255.23    4773  249.72  4804.5   256.1    4815  255.68
  4824.6  247.63    4836  246.41  4838.3  246.26  4990.8  238.91    5001  233.28
  5003.7  232.78    5007  233.28    5023  239.57  5092.6  241.73  5116.2  245.69
  5140.4  247.14  5162.2  252.02  5339.9  257.77  5564.3  250.99  5917.1  257.78
#Mann= 7 ,-1 , 0
  4085.8     .05       0  4236.3      .1       0  4511.3     .05       0
  4838.3     .12       0    5001     .07       0    5007     .12       0
  5116.2      .1       0
#XS Ineff= 1 ,-1
 5357.85 5900.99  258.04
Permanent Ineff=
       T
Bank Sta=4836,5140.4
XS Rating Curve= 0 ,0
Exp/Cntr=0.3,0.1

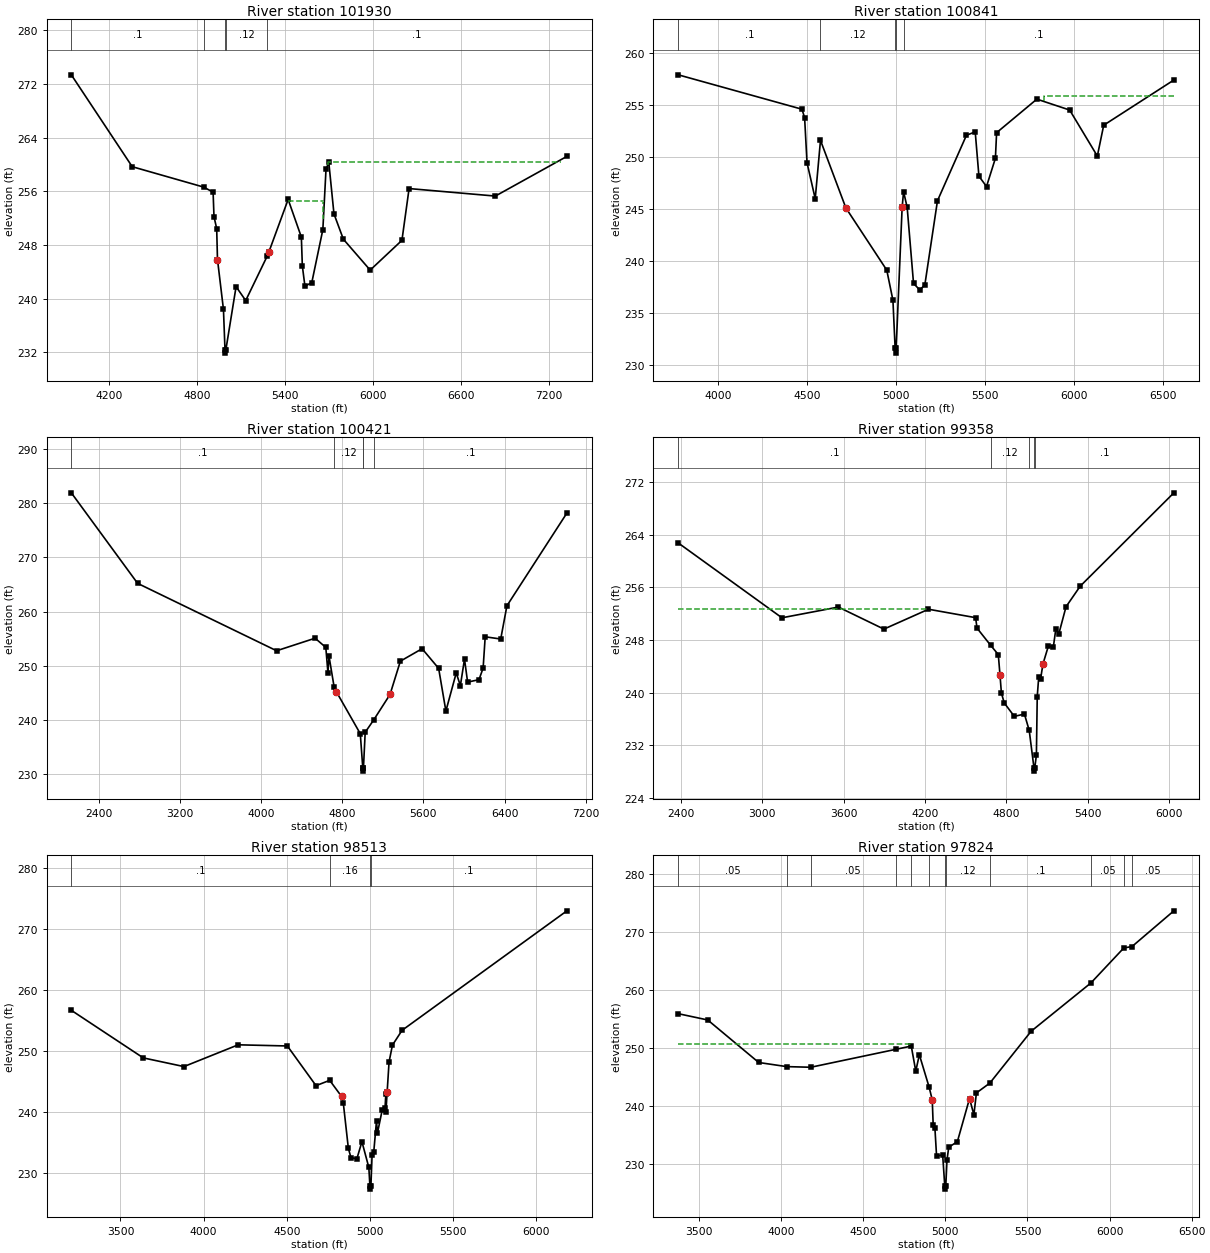
Type RM Length L Ch R = 1 ,101930  ,1089,1089,1089
BEGIN DESCRIPTION:
SULPHUR CREEK 102.0
END DESCRIPTION:
XS GIS Cut Line= 4
      2269224.96     13406672.37      2268590.17     13406463.09
      2266818.22     13407160.71      2266253.58     13407732.33
#Sta/Elev= 30
    3944  273.38  4358.9  259.68  4845.5  256.64  4909.9  255.88  4915.9  252.23
  4934.3  250.45  4939.7  245.84  4980.4   238.4  4990.9  232.38  4993.6  231.88
  4996.9  232.38  5066.4  241.79    5132  239.72  5277.8  246.32  5289.1  246.92
  5421.1   254.8  5511.1  249.18  5517.8  244.89  5535.5  241.85  5582.3  242.41
  5657.5   250.3    5679  259.28    5698  260.34  5733.2  252.65  5797.2  248.87
  5979.9  244.26  6196.3   248.7    6245  256.42  6832.6   255.3  7320.2  261.22
#Mann= 5 ,-1 , 0
    3944      .1       0  4845.5     .12       0  4990.9     .07       0
  4996.9     .12       0  5277.8      .1       0
#XS Ineff= 2 ,-1
 5417.96 5661.24  254.61 5689.53 7279.35  260.37
Permanent Ineff=
       T       T
Bank Sta=4939.7,5289.1
XS Rating Curve= 0 ,0
Exp/Cntr=0.3,0.1

Type RM Length L Ch R = 1 ,100841  ,420,420,420
BEGIN DESCRIPTION:
SULPHUR CREEK 101.0
END DESCRIPTION:
XS GIS Cut Line= 3
       2268453.7      13405502.8      2267341.87     13406010.04
      2266189.04     13407065.51
#Sta/Elev= 30
  3777.9   257.9  4472.9  254.59  4487.9  253.78  4501.4  249.44  4547.5  245.97
  4577.1  251.59  4719.7  245.09  4949.6   239.1  4984.2   236.2  4996.5  231.61
  4999.3  231.11  5002.5  231.61  5035.9  245.14  5044.1  246.65  5064.3  245.13
    5100  237.82  5135.2  237.19  5163.5  237.68  5234.5  245.78  5397.3  252.08
  5446.6  252.41  5467.5  248.14  5510.1  247.15  5560.1  249.87  5566.8  252.33
  5793.1  255.56  5977.5  254.51  6132.9  250.08  6168.7  253.05    6563   257.4
#Mann= 5 ,-1 , 0
  3777.9      .1       0  4577.1     .12       0  4996.5     .07       0
  5002.5     .12       0  5044.1      .1       0
#XS Ineff= 2 , 0
                         5832.67          255.83
Permanent Ineff=
       T       T
Bank Sta=4719.7,5035.9
XS Rating Curve= 0 ,0
Exp/Cntr=0.3,0.1

Type RM Length L Ch R = 1 ,100421  ,1063,1063,1063
BEGIN DESCRIPTION:
SULPHUR CREEK 100.0
END DESCRIPTION:
XS GIS Cut Line= 3
      2269787.71     13404796.86      2267087.72     13405696.85
      2265087.77     13406096.85
#Sta/Elev= 30
  2128.9  281.94  2782.4  265.22  4152.7  252.77  4532.2  255.09  4637.6  253.39
  4658.7  248.72  4669.3  251.75    4720  246.04    4743  245.16  4977.5  237.45
  5002.5  231.04  5005.3  230.54  5008.5  231.04  5025.9  237.72  5109.7  239.99
  5270.7   244.7  5372.7  250.85  5586.8  253.15    5750  249.52  5821.4  241.64
  5923.4  248.68  5964.1  246.32  6004.9  251.23  6035.5  246.98  6147.7  247.43
  6188.5  249.58  6208.9  255.35  6361.9  254.94  6423.1  261.08  7014.5  278.21
#Mann= 5 ,-1 , 0
  2128.9      .1       0    4720     .12       0  5002.5     .07       0
  5008.5     .12       0  5109.7      .1       0
#XS Ineff= 2 , 0
            4529  255.05
Permanent Ineff=
       T       T
Bank Sta=4743,5270.7
XS Rating Curve= 0 ,0
Exp/Cntr=0.3,0.1

Type RM Length L Ch R = 1 ,99358   ,845,845,845
BEGIN DESCRIPTION:
SULPHUR CREEK 99.0
END DESCRIPTION:
XS GIS Cut Line= 3
      2268840.24     13404620.45      2267320.71     13404738.35
      2265304.57     13405432.22
#Sta/Elev= 30
  2379.9  262.73  3144.7  251.36  3561.2  252.99    3897  249.64  4225.9  252.66
  4573.4  251.38    4584  249.79  4684.4  247.18  4740.9  245.77  4753.2  242.71
  4763.8  239.93  4784.9  238.42    4859  236.38  4933.6  236.73    4969  234.25
    5004  228.56  5006.8  228.06    5010  228.56    5022   230.5  5028.2  239.38
  5038.8  242.29  5053.2  242.11  5070.5  244.35  5110.4  247.07  5146.9  246.89
  5165.7  249.73  5186.8  248.87  5240.6  253.04  5345.4  256.17  6036.2  270.35
#Mann= 5 ,-1 , 0
  2379.9      .1       0  4684.4     .12       0    4969      .1       0
    5004     .07       0    5010      .1       0
#XS Ineff= 2 , 0
         4214.99  252.71
Permanent Ineff=
       T       T
Bank Sta=4753.2,5070.5
XS Rating Curve= 0 ,0
Exp/Cntr=0.3,0.1

Type RM Length L Ch R = 1 ,98513   ,689,689,689
BEGIN DESCRIPTION:
SULPHUR CREEK 97.0
END DESCRIPTION:
XS GIS Cut Line= 3
      2267792.29      13403965.5      2265408.23     13404437.07
      2265067.63     13404869.36
#Sta/Elev= 30
  3204.4  256.66  3637.2  248.88  3881.8  247.46    4208  251.02  4503.7  250.83
    4676  244.34  4758.3  245.21  4829.8  242.57  4840.1  241.51  4870.6  234.08
  4886.1  232.58  4921.6  232.37  4952.2  235.18  4993.7  230.96  5000.2  227.92
  5002.9  227.42  5006.2  227.92  5013.3  233.08  5023.5  233.56  5039.9  238.63
    5045  236.52  5074.5  240.41  5091.1  240.71 5096.02  242.98  5096.2  239.96
 5103.98  243.35  5115.3  248.22  5135.7  250.97  5193.6  253.39    6185  272.93
#Mann= 4 ,-1 , 0
  3204.4      .1       0  4758.3     .16       0  5000.2     .07       0
  5006.2      .1       0
Bank Sta=4829.8,5103.98
XS Rating Curve= 0 ,0
Exp/Cntr=0.3,0.1

Type RM Length L Ch R = 1 ,97824   ,907,907,907
BEGIN DESCRIPTION:
SULPHUR CREEK 96.0
END DESCRIPTION:
XS GIS Cut Line= 4
        2267491.     13403454.63      2266953.93     13403310.54
      2265054.55      13403939.3      2264832.31     13404344.55
#Sta/Elev= 30
  3372.7  255.89  3552.1  254.81  3862.7  247.49  4033.3  246.78  4179.9  246.67
  4697.1  249.75    4792  250.32  4819.4     246  4841.2  248.83  4901.2  243.21
  4919.8  241.05  4925.5  236.77    4936  236.21  4946.2  231.36  4983.2   231.6
  4996.2  226.19    4999  225.69  5002.2  226.19  5009.7  230.73  5020.3   232.9
  5072.9  233.87    5147  241.29  5173.5  238.48  5188.8  242.25  5270.8  243.95
  5522.3  252.87  5886.6  261.19  6086.8  267.21  6136.7  267.45  6391.7   273.6
#Mann= 12 ,-1 , 0
  3372.7     .05       0  4033.3      .1       0  4179.9     .05       0
  4697.1      .1       0    4792     .16       0  4901.2     .12       0
  4996.2     .07       0  5002.2     .12       0  5270.8      .1       0
  5886.6     .05       0  6086.8      .1       0  6136.7     .05       0
#XS Ineff= 2 , 0
         4787.13  250.65
Permanent Ineff=
       T       T
Bank Sta=4919.8,5147
XS Rating Curve= 0 ,0
Exp/Cntr=0.3,0.1

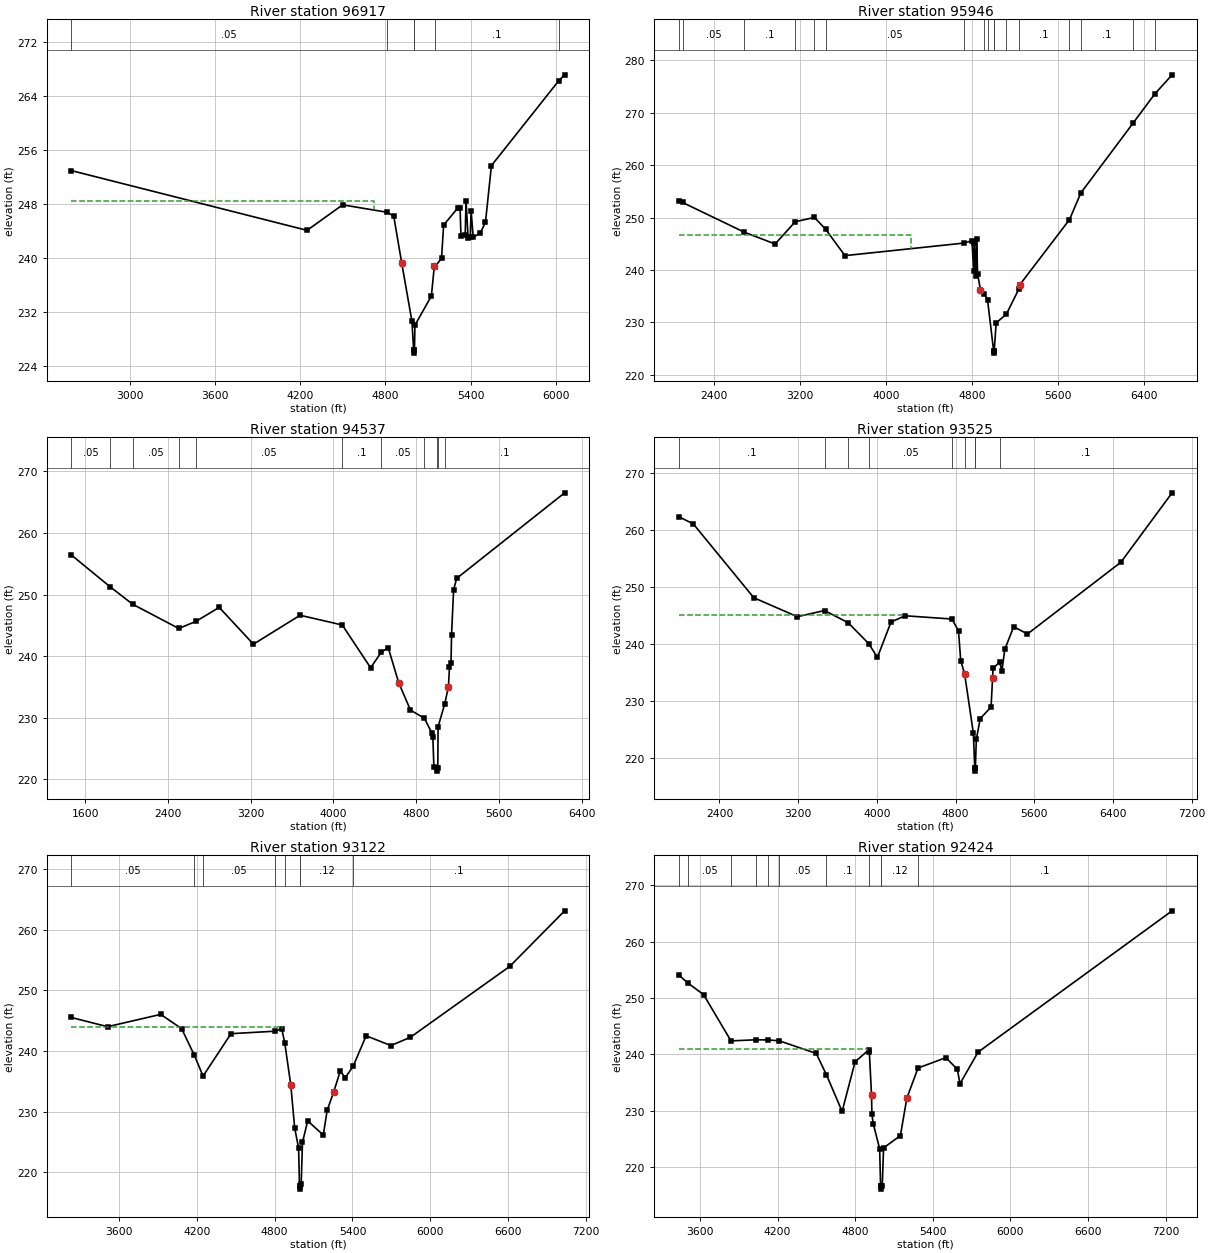
Type RM Length L Ch R = 1 ,96917   ,971,971,971
BEGIN DESCRIPTION:
Mapping XS 174b8818
END DESCRIPTION:
XS GIS Cut Line= 4
      2267495.37     13403171.76      2266106.52     13402477.34
       2264821.8     13403380.12      2264631.76     13403673.82
#Sta/Elev= 30
  2588.8  252.93  4248.9  244.09    4499  247.86    4813  246.76  4858.8  246.19
  4915.5  239.19  4986.9  230.65  4998.7  226.44  5001.5  225.94  5004.7  226.44
  5007.9  230.06  5123.7  234.38  5144.6   238.8  5146.1  238.68  5195.2  239.94
    5210  244.87    5311  247.42  5325.7  247.42    5332  243.26  5361.6  243.37
  5367.7  248.43  5382.5  242.91  5397.3  243.18  5403.4  246.96  5418.2  243.05
  5468.8  243.71  5504.5   245.3  5546.3  253.66  6020.8  266.22  6061.6  267.08
#Mann= 6 ,-1 , 0
  2588.8     .05       0    4813     .12       0  4998.7     .07       0
  5004.7     .12       0  5146.1      .1       0  6020.8     .05       0
#XS Ineff= 2 , 0
         4720.45  248.41
Permanent Ineff=
       T       T
Bank Sta=4915.5,5144.6
XS Rating Curve= 0 ,0
Exp/Cntr=0.3,0.1

Type RM Length L Ch R = 1 ,95946   ,1409,1409,1409
BEGIN DESCRIPTION:
SULPHUR CREEK 95.0
END DESCRIPTION:
XS GIS Cut Line= 4
      2267464.81     13401843.43      2265028.35     13401843.43
      2264360.29     13402904.46      2264216.48     13403793.51
#Sta/Elev= 30
  2068.2  253.17  2104.2  252.87  2677.5  247.21  2965.3  244.95    3153  249.19
  3331.3  250.02  3434.8  247.78  3615.3  242.73  4720.6  245.12  4797.5  245.57
  4812.8  239.71  4818.7  245.19    4834  238.79  4839.9  245.99  4849.3  239.29
  4876.4  236.18  4910.3  235.47  4941.8  234.34  4998.2  224.63  5000.9  224.13
  5004.2  224.63  5022.4   229.9  5117.8  231.58  5231.4  236.28  5241.3  237.15
  5704.1  249.59  5810.2  254.69  6293.7  267.94  6497.7  273.56  6659.1  277.22
#Mann= 17 ,-1 , 0
  2068.2      .1       0  2104.2     .05       0  2677.5      .1       0
    3153     .05       0  3331.3      .1       0  3434.8     .05       0
  4720.6      .1       0  4910.3     .12       0  4941.8      .1       0
  4998.2     .07       0  5004.2      .1       0  5117.8     .12       0
  5231.4      .1       0  5704.1     .05       0  5810.2      .1       0
  6293.7     .05       0  6497.7      .1       0
#XS Ineff= 2 , 0
         4227.27  246.66
Permanent Ineff=
       T       T
Bank Sta=4876.4,5241.3
XS Rating Curve= 0 ,0
Exp/Cntr=0.3,0.1

Type RM Length L Ch R = 1 ,94537   ,1012,1012,1012
BEGIN DESCRIPTION:
Mapping XS 15559947
END DESCRIPTION:
XS GIS Cut Line= 2
      2267634.33     13401522.48      2262877.38     13401157.89
#Sta/Elev= 30
  1464.2  256.44  1843.7  251.21  2059.5  248.41    2504  244.49  2669.9  245.63
    2895  247.91    3226  241.93  3677.3  246.63    4085  245.05  4359.3   238.1
  4463.7  240.66  4529.8  241.35  4630.1   235.7  4744.6  231.22  4879.5   229.9
    4951   227.5    4961  226.81  4971.1  221.95  5002.9  221.81  5005.6  221.31
  5008.9  221.81  5011.2  228.51  5075.2  232.19  5111.5  235.01  5121.5  238.15
  5136.5  238.86  5141.6  243.43  5161.6  250.79  5191.7  252.63  6235.1  266.52
#Mann= 11 ,-1 , 0
  1464.2     .05       0  1843.7      .1       0  2059.5     .05       0
    2504      .1       0  2669.9     .05       0    4085      .1       0
  4463.7     .05       0  4879.5     .12       0  5002.9     .07       0
  5008.9     .12       0  5075.2      .1       0
#XS Ineff= 2 , 0
         3676.14   246.6
Permanent Ineff=
       T       T
Bank Sta=4630.1,5111.5
XS Rating Curve= 0 ,0
Exp/Cntr=0.3,0.1

Type RM Length L Ch R = 1 ,93525   ,403,403,403
BEGIN DESCRIPTION:
SULPHUR CREEK 94.0
END DESCRIPTION:
XS GIS Cut Line= 3
      2267837.71     13400896.85      2264837.72     13400596.85
      2262837.77     13400596.85
#Sta/Elev= 30
  1985.6  262.38  2133.8  261.12  2749.4  248.17  3191.6  244.85  3468.2  245.93
    3709  243.78    3917  240.13  4005.6  237.72  4143.8  243.92    4287  245.01
  4763.7  244.44  4829.7  242.35  4852.3  237.14    4892  234.82  4980.4  224.46
    4995  218.28  4997.8  217.78    5001  218.28  5010.5  223.33  5050.5  226.99
  5160.5  229.01 5176.14  234.11  5180.5  235.78  5247.3   236.9  5270.5  235.36
  5300.5  239.13  5390.5  243.09  5530.5  241.82  6480.5   254.4  7000.5  266.56
#Mann= 9 ,-1 , 0
  1985.6      .1       0  3468.2     .05       0    3709      .1       0
    3917     .05       0  4763.7      .1       0    4892     .12       0
    4995     .07       0    5001     .12       0  5247.3      .1       0
#XS Ineff= 2 , 0
          4289.2  245.07
Permanent Ineff=
       T       T
Bank Sta=4892,5176.14
XS Rating Curve= 0 ,0
Exp/Cntr=0.3,0.1

Type RM Length L Ch R = 1 ,93122   ,698,698,698
BEGIN DESCRIPTION:
SULPHUR CREEK 93.0
END DESCRIPTION:
XS GIS Cut Line= 3
      2266777.61     13400315.52      2264238.53     13400228.72
      2262981.28     13400293.75
#Sta/Elev= 30
    3234  245.53  3514.1  244.01    3923  246.04  4084.4  243.68    4182  239.31
  4249.2  235.86  4464.6  242.86  4806.2  243.27  4854.8  243.71  4878.4  241.35
  4924.9  234.38  4954.9  227.28  4984.9  224.01  4991.9  217.72  4994.7  217.22
  4997.9  217.72  5004.9  218.04  5014.9  224.94    5055  228.47    5175  226.15
    5205  230.21  5255.1  233.24  5305.1  236.65  5345.1  235.62  5404.9  237.48
  5505.2  242.51  5695.3   240.9  5845.5  242.26  6610.6  253.95  7033.5  263.12
#Mann= 8 ,-1 , 0
    3234     .05       0    4182      .1       0  4249.2     .05       0
  4806.2      .1       0  4878.4     .12       0  4991.9     .07       0
  4997.9     .12       0  5404.9      .1       0
#XS Ineff= 2 , 0
         4855.11  244.02
Permanent Ineff=
       T       T
Bank Sta=4924.9,5255.1
XS Rating Curve= 0 ,0
Exp/Cntr=0.3,0.1

Type RM Length L Ch R = 1 ,92424   ,1044,1044,1044
BEGIN DESCRIPTION:
SULPHUR CREEK 92.0
END DESCRIPTION:
XS GIS Cut Line= 4
      2266429.91     13399590.37      2265696.41     13399564.17
      2263587.44     13399655.87       2262696.7     13400035.74
#Sta/Elev= 30
  3435.8  254.08  3505.2  252.67  3628.1  250.59  3840.1  242.38  4035.7  242.58
  4129.1  242.54    4212   242.4  4498.8  240.16  4578.1  236.35    4699  229.88
  4799.1  238.67  4903.7  240.77  4909.2  240.45 4926.14  232.83  4929.2  229.38
  4939.2  227.73  4989.2  223.22  4996.2   216.6    4999   216.1  5002.2   216.6
  5009.3  216.72  5019.3  223.41  5149.4  225.59  5199.4  232.25  5285.7  237.57
  5501.2  239.41  5589.8  237.33  5609.8  234.79    5750   240.4  7249.1  265.44
#Mann= 11 ,-1 , 0
  3435.8      .1       0  3505.2     .05       0  3840.1      .1       0
  4035.7     .05       0  4129.1      .1       0    4212     .05       0
  4578.1      .1       0  4903.7     .12       0  4996.2     .07       0
  5002.2     .12       0  5285.7      .1       0
#XS Ineff= 2 , 0
         4892.05  240.94
Permanent Ineff=
       T       T
Bank Sta=4926.14,5199.4
XS Rating Curve= 0 ,0
Exp/Cntr=0.3,0.1