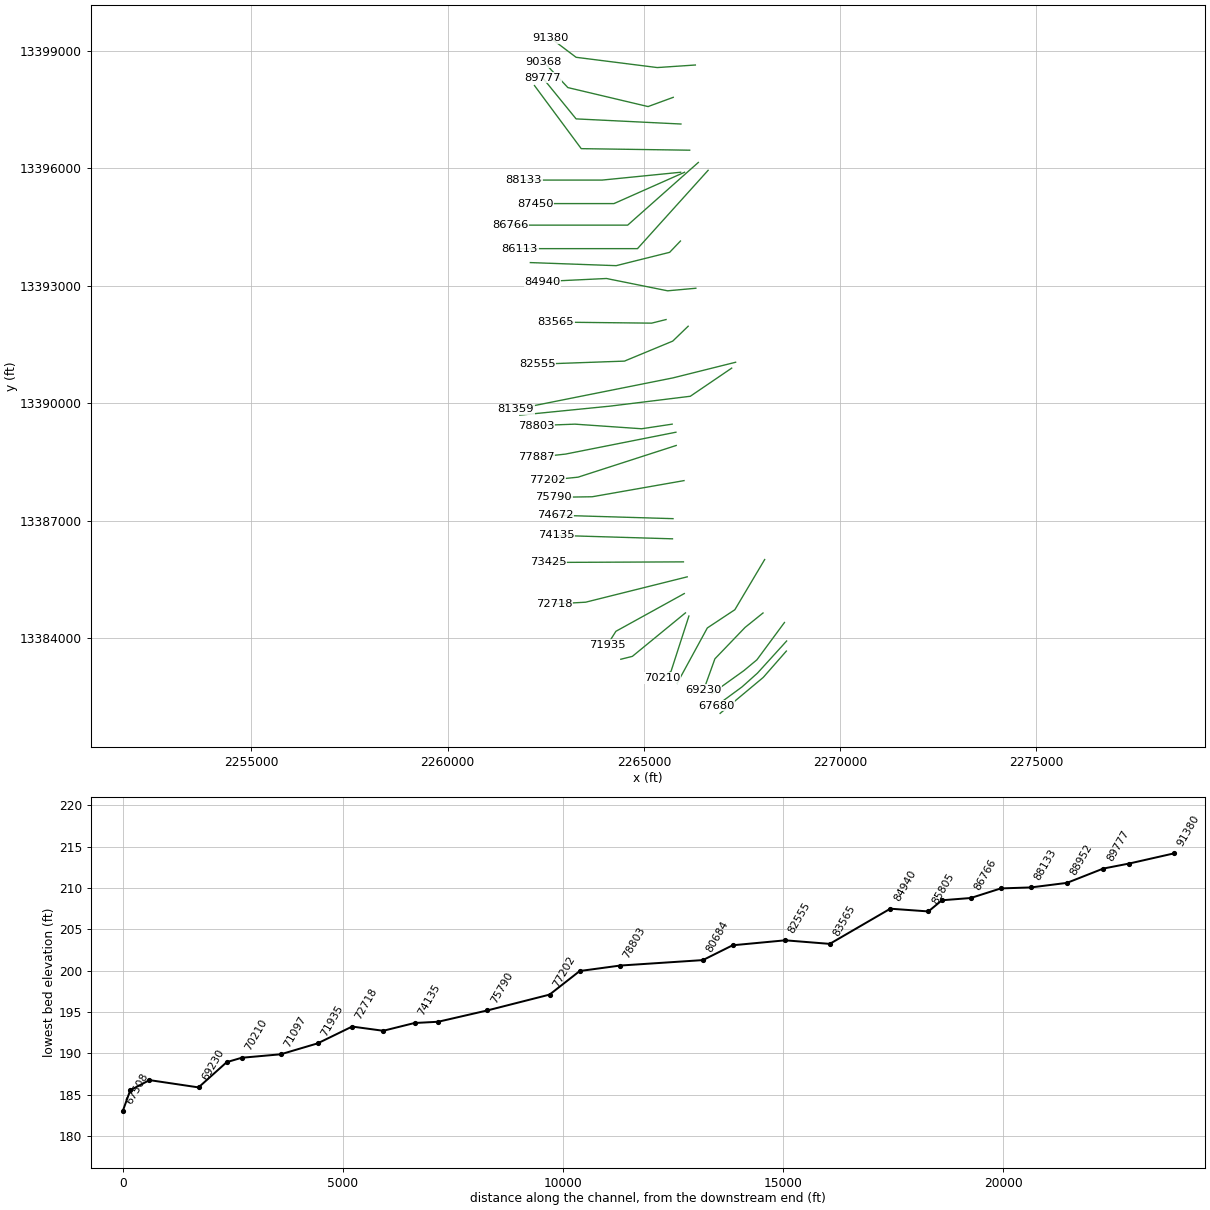
HEC-RAS study SULPHUR CREEK.prj: SULPHUR CREEK Base Level Engineering

--- SULPHUR CREEK.g01 (geometry) --- (continued)

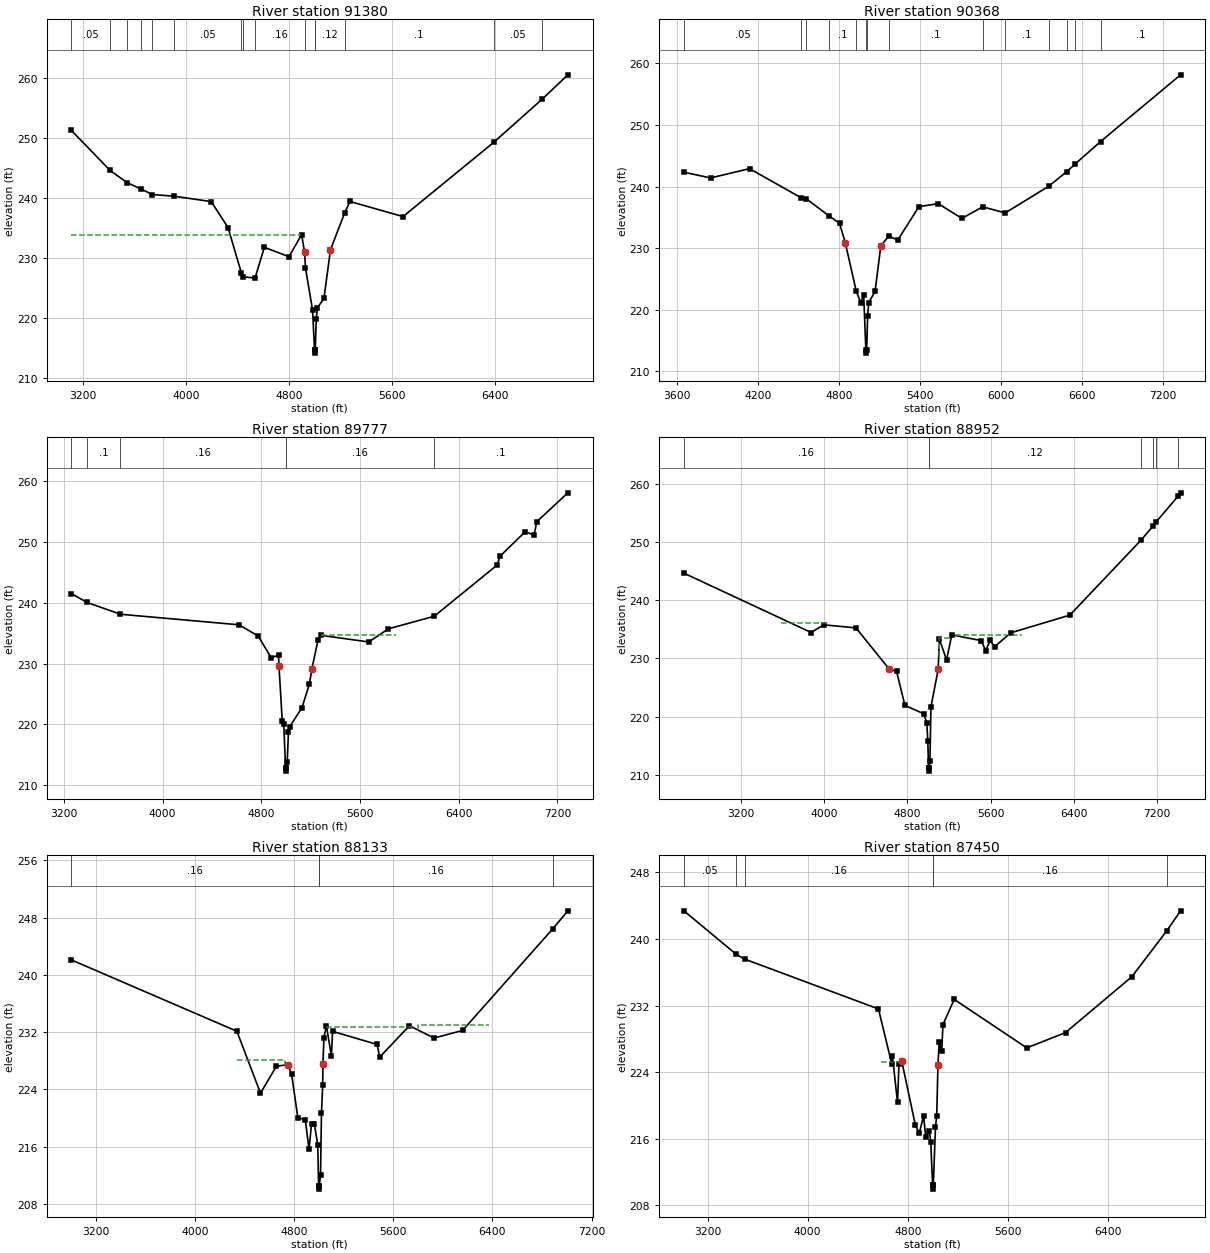
Type RM Length L Ch R = 1 ,91380   ,1012,1012,1012
BEGIN DESCRIPTION:
SULPHUR CREEK 90.0
END DESCRIPTION:
XS GIS Cut Line= 4
       2266312.1     13398634.13      2265342.73     13398568.64
      2263273.06     13398830.62      2262631.97     13399314.71
#Sta/Elev= 30
    3109  251.31  3410.3  244.63  3542.1  242.61  3649.2  241.55  3738.7  240.62
  3910.6  240.33  4196.5  239.44  4327.5  235.11  4430.7  227.57    4442   226.9
  4537.6  226.69  4609.8  231.82  4801.3  230.25  4899.8  233.93  4922.3  231.03
  4929.8  228.37    4985  221.31  4999.9  214.67  5002.6  214.17  5005.9  214.67
    5013  219.91  5023.1  221.75  5073.5  223.31  5123.9   231.4  5234.1  237.54
    5275  239.46  5688.3  236.94  6393.1  249.31  6771.3  256.54  6970.1  260.58
#Mann= 15 ,-1 , 0
    3109     .05       0  3410.3      .1       0  3542.1     .05       0
  3649.2     .08       0  3738.7      .1       0  3910.6     .05       0
  4430.7     .12       0    4442      .1       0  4537.6     .16       0
  4929.8     .12       0  4999.9     .07       0  5005.9     .12       0
  5234.1      .1       0  6393.1     .05       0  6771.3      .1       0
#XS Ineff= 2 , 0
         4897.73  233.95
Permanent Ineff=
       T       T
Bank Sta=4922.3,5123.9
XS Rating Curve= 0 ,0
Exp/Cntr=0.3,0.1

Type RM Length L Ch R = 1 ,90368   ,591,591,591
BEGIN DESCRIPTION:
SULPHUR CREEK 89.0
END DESCRIPTION:
XS GIS Cut Line= 4
      2265748.79     13397808.88      2265106.95      13397573.1
      2263063.48     13398057.77      2262448.25     13398712.26
#Sta/Elev= 30
  3650.1  242.33  3846.4   241.4  4135.2  242.91  4519.1  238.17  4556.6  238.01
  4722.5  235.28  4802.9  234.04  4845.1  230.91  4926.9     223    4960  221.17
  4982.1  222.39  4998.1  213.45  5000.9  212.95  5004.1  213.45  5011.4  218.92
  5019.2  221.15  5066.5  222.97  5108.7  230.32  5166.1  231.94  5235.4  231.34
  5391.7  236.74  5535.5  237.23  5710.1  234.83  5864.2  236.71  6031.7  235.72
  6353.1  240.04  6486.6   242.4  6550.4  243.67  6738.6  247.31  7332.3  258.15
#Mann= 14 ,-1 , 0
  3650.1     .05       0  4519.1      .1       0  4556.6     .16       0
  4722.5      .1       0  4926.9     .12       0  4998.1     .07       0
  5004.1     .12       0  5166.1      .1       0  5864.2     .07       0
  6031.7      .1       0  6353.1     .05       0  6486.6      .1       0
  6550.4     .05       0  6738.6      .1       0
Bank Sta=4845.1,5108.7
XS Rating Curve= 0 ,0
Exp/Cntr=0.3,0.1

Type RM Length L Ch R = 1 ,89777   ,825,825,825
BEGIN DESCRIPTION:
SULPHUR CREEK 88.0
END DESCRIPTION:
XS GIS Cut Line= 3
      2265945.27     13397127.73      2263273.06     13397258.72
      2262422.15     13398305.99
#Sta/Elev= 30
  3260.2  241.49    3388  240.04  3658.2   238.1  4619.4  236.37  4774.4  234.53
  4879.7  230.96  4939.8  231.39 4943.18  229.59  4969.8  220.56  4981.6  220.14
  4996.8  212.84  4999.6  212.34  5002.8  212.84  5009.9  213.79  5019.9  218.73
  5029.9  219.62    5130  222.78  5190.1  226.66  5210.1  229.15  5260.2  233.91
  5280.2  234.65  5670.6  233.55  5830.8  235.71  6201.6  237.77    6713   246.2
  6733.8  247.61  6939.9  251.66  7011.8   251.1  7032.6  253.29    7285  258.04
#Mann= 6 ,-1 , 0
  3260.2     .05       0    3388      .1       0  3658.2     .16       0
  4996.8     .07       0  5002.8     .16       0  6201.6      .1       0
#XS Ineff= 1 ,-1
 5293.88  5889.8  234.69
Permanent Ineff=
       T
Bank Sta=4943.18,5210.1
XS Rating Curve= 0 ,0
Exp/Cntr=0.3,0.1

Type RM Length L Ch R = 1 ,88952   ,819,819,819
BEGIN DESCRIPTION:
SULPHUR CREEK 87.0
END DESCRIPTION:
XS GIS Cut Line= 3
      2266168.02     13396459.67      2263404.05     13396498.97
      2262212.36     13398109.71
#Sta/Elev= 30
  2655.9  244.65  3876.3  234.46  3996.3  235.78  4306.4  235.25  4626.4  228.15
  4696.4  227.78  4776.4  221.91  4956.4  220.49  4986.4  218.92  4996.4  215.78
  5003.4  211.11  5006.2  210.61  5009.4  211.11  5016.4  212.42  5026.4  221.64
  5096.4  228.16  5106.4  233.39  5176.5  229.73  5226.5  234.05  5508.6  233.07
  5552.5  231.36  5594.2  233.09  5638.1  232.03  5794.6  234.41  6360.3  237.45
  7047.1  250.41  7157.5  252.75  7185.8  253.42  7397.7  257.87  7423.8  258.49
#Mann= 8 ,-1 , 0
  2655.9     .16       0  5003.4     .12       0  5003.4     .07       0
  5009.4     .12       0  7047.1     .05       0  7157.5      .1       0
  7185.8     .05       0  7397.7      .1       0
#XS Ineff= 3 ,-1
 3586.94 4042.45  236.02 5100.41 5232.65  233.46 5266.94 5898.78  234.08
Permanent Ineff=
       T       T       T
Bank Sta=4626.4,5096.4
XS Rating Curve= 0 ,0
Exp/Cntr=0.3,0.1

Type RM Length L Ch R = 1 ,88133   ,683,683,683
BEGIN DESCRIPTION:
SULPHUR CREEK 86.0
END DESCRIPTION:
XS GIS Cut Line= 3
      2265937.68     13395896.85      2263937.72     13395696.85
      2261937.75     13395696.85
#Sta/Elev= 30
  2998.9   242.1  4335.5  232.13  4526.4  223.47  4654.6  227.23  4747.5  227.46
  4777.7  226.12  4827.9  220.05  4888.2  219.76  4918.4  215.62  4938.5  219.16
  4961.1  219.18  4988.7  216.28  4995.8  210.56  4998.5  210.06  5001.8  210.56
  5011.3  212.05  5018.8  220.65  5028.8  224.61 5030.68  227.52  5038.8  231.25
  5058.8   232.9  5098.8  228.69  5108.8  232.11  5468.8  230.28  5488.8  228.51
  5728.8  232.89  5928.8  231.18  6158.8  232.24  6888.8  246.48  7008.8  248.96
#Mann= 4 ,-1 , 0
  2998.9     .16       0  4995.8     .07       0  5001.8     .16       0
  6888.8     .05       0
#XS Ineff= 3 ,-1
 4336.33 4728.16  228.11 5061.22 5751.84  232.79 5800.82 6368.98  232.95
Permanent Ineff=
       T       T       T
Bank Sta=4747.5,5030.68
XS Rating Curve= 0 ,0
Exp/Cntr=0.3,0.1

Type RM Length L Ch R = 1 ,87450   ,684,684,684
BEGIN DESCRIPTION:
SULPHUR CREEK 85.0
END DESCRIPTION:
XS GIS Cut Line= 3
      2266037.75     13395896.87      2264237.72     13395096.85
      2262237.72     13395096.85
#Sta/Elev= 30
  3011.9  243.36  3429.6  238.14  3495.5  237.58  4565.9  231.59  4671.9  225.02
  4677.3  225.96  4718.4  220.35    4730  224.94  4752.6  225.29  4861.3  217.61
  4892.1  216.68    4927  218.72  4944.1  216.18  4972.8  216.97  4984.2  215.59
  4998.7  210.44  5001.5  209.94  5004.7  210.44  5021.7  217.39  5031.7  218.76
  5041.7  224.87  5051.7  227.65  5071.7  226.48  5081.7  229.71  5171.7  232.74
  5751.7  226.91  6061.7  228.75  6591.7  235.46  6871.7  240.99  6981.7  243.38
#Mann= 6 ,-1 , 0
  3011.9     .05       0  3429.6      .1       0  3495.5     .16       0
  4998.7     .07       0  5004.7     .16       0  6871.7     .05       0
#XS Ineff= 2 ,-1
 4586.94 4737.14  225.25 5177.96 6402.45  232.62
Permanent Ineff=
       T       T
Bank Sta=4752.6,5041.7
XS Rating Curve= 0 ,0
Exp/Cntr=0.3,0.1

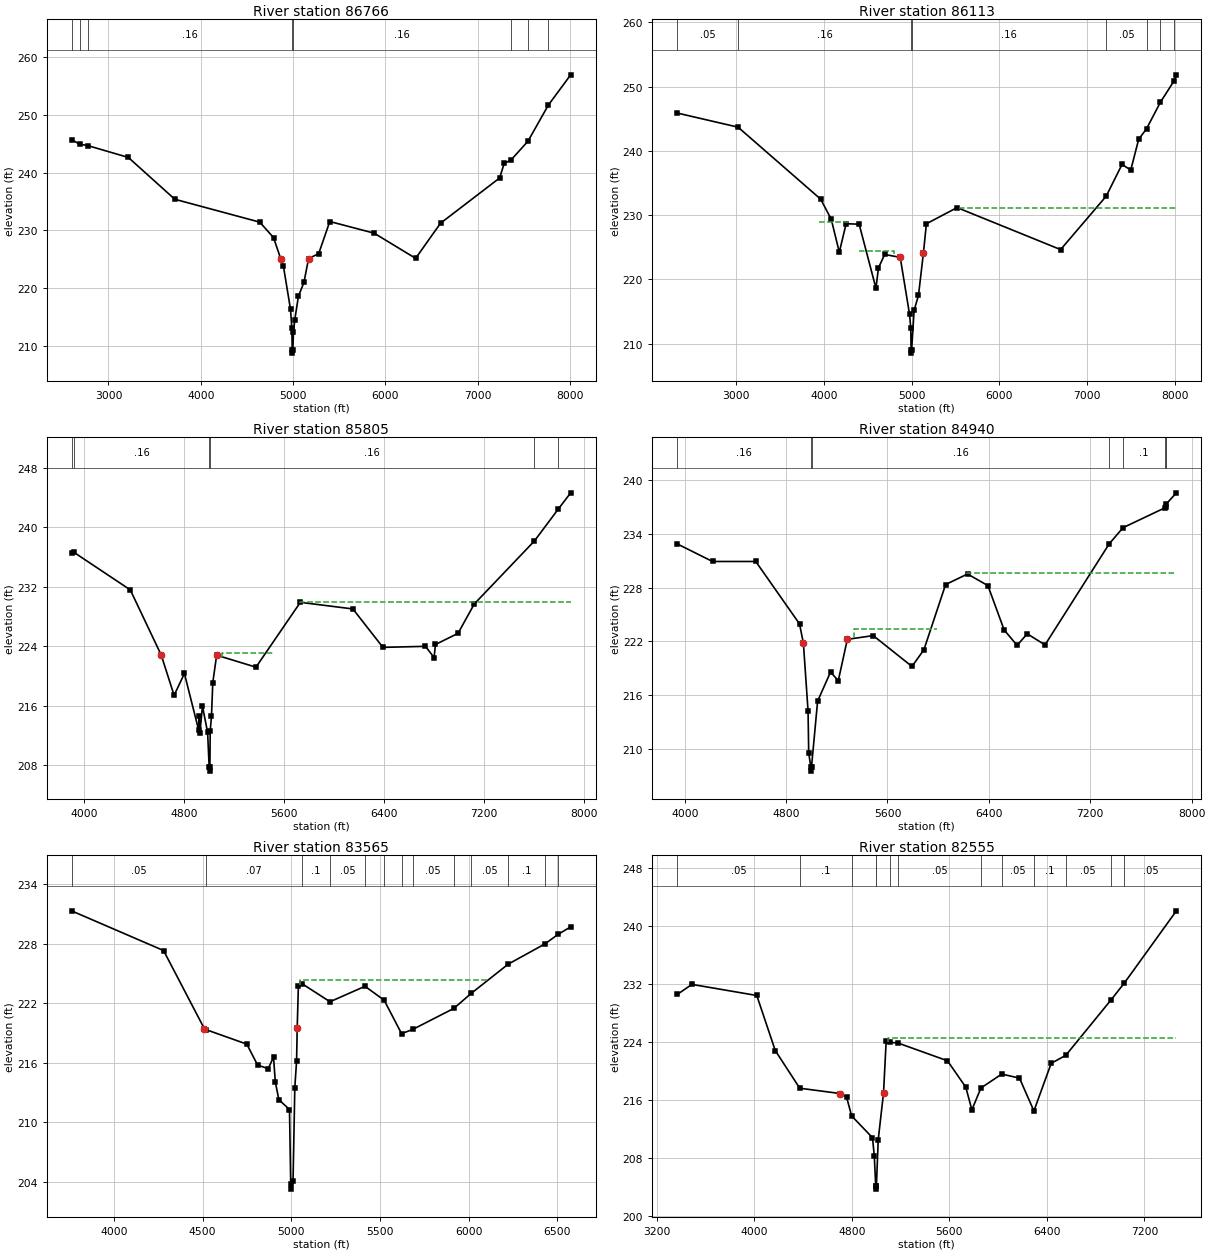
Type RM Length L Ch R = 1 ,86766   ,653,653,653
BEGIN DESCRIPTION:
SULPHUR CREEK 84.0
END DESCRIPTION:
XS GIS Cut Line= 3
      2266387.75     13396146.88      2264587.72     13394546.85
      2261587.67     13394546.85
#Sta/Elev= 30
  2599.7  245.71  2687.6  244.92  2776.6  244.67  3215.6  242.62    3719  235.39
  4639.7  231.43  4788.5  228.76  4866.3  225.11  4894.7  223.91  4972.5  216.36
  4986.7  213.18  4991.3  209.28    4994  208.78  4997.3  209.28  5004.7  212.41
  5018.1  214.49  5058.1   218.6  5118.1  221.02  5168.1  225.12  5278.1     226
  5398.1  231.54  5878.1  229.53  6328.1  225.17  6598.1  231.25  7238.1  239.07
  7288.1  241.61  7358.1  242.12  7545.2  245.43  7766.6  251.69  8008.1  256.91
#Mann= 8 ,-1 , 0
  2599.7      .1       0  2687.6     .08       0  2776.6     .16       0
  4991.3     .07       0  4997.3     .16       0  7358.1     .05       0
  7545.2      .1       0  7766.6     .05       0
#XS Ineff= 1 ,-1
 5411.43 6914.29  231.48
Permanent Ineff=
       T
Bank Sta=4866.3,5168.1
XS Rating Curve= 0 ,0
Exp/Cntr=0.3,0.1

Type RM Length L Ch R = 1 ,86113   ,308,308,308
BEGIN DESCRIPTION:
SULPHUR CREEK 83.0
END DESCRIPTION:
XS GIS Cut Line= 3
       2266637.7     13395946.84      2264837.72     13393946.85
      2261837.72     13393946.85
#Sta/Elev= 30
  2328.1  245.89  3022.1  243.69  3963.8  232.48  4084.1  229.36  4176.1  224.22
  4253.8  228.66  4402.5  228.58  4593.9  218.61  4622.3  221.78  4693.3  223.87
  4870.4  223.42  4976.6  214.57  4990.8   212.4  4994.5  209.01  4997.2  208.51
  5000.5  209.01  5028.8  215.17  5078.8  217.52  5135.4  224.15  5168.8  228.65
  5518.8  231.17  6698.8  224.63  7218.8  232.95  7398.8  237.88  7498.8  237.02
  7588.8  241.81  7678.8  243.45  7837.1  247.59  7994.3  250.94  8018.8  251.84
#Mann= 8 ,-1 , 0
  2328.1     .05       0  3022.1     .16       0  4994.5     .07       0
  5000.5     .16       0  7218.8     .05       0  7678.8      .1       0
  7837.1     .05       0  7994.3      .1       0
#XS Ineff= 3 ,-1
 3948.57    4280  228.89    4400 4794.29  224.47 5555.68  8018.8  231.16
Permanent Ineff=
       T       T       T
Bank Sta=4870.4,5135.4
XS Rating Curve= 0 ,0
Exp/Cntr=0.3,0.1

Type RM Length L Ch R = 1 ,85805   ,865,865,865
BEGIN DESCRIPTION:
SULPHUR CREEK 82.0
END DESCRIPTION:
XS GIS Cut Line= 4
      2265932.22     13394141.14      2265657.11     13393852.93
       2264294.8     13393512.35      2262107.28     13393590.95
#Sta/Elev= 30
  3898.9  236.61  3919.1  236.64  4368.9  231.59  4616.2  222.81  4719.3  217.37
  4801.8  220.32  4915.1  212.73  4920.3  214.58  4925.5  212.29  4946.1  215.91
  4987.3  212.38  4999.7  207.66  5002.5  207.16  5005.7  207.66  5007.9  212.58
  5018.2  214.54  5028.6  219.09  5059.5  222.79  5373.8  221.17  5728.7  229.91
  6148.9  229.02  6389.1  223.84  6729.3  223.98  6798.1  222.47  6809.4  224.23
  6989.5  225.73  7119.6  229.69  7599.9  238.17  7792.6  242.51  7890.5  244.67
#Mann= 6 ,-1 , 0
  3898.9      .1       0  3919.1     .16       0  4999.7     .07       0
  5005.7     .16       0  7599.9     .05       0  7792.6      .1       0
#XS Ineff= 2 ,-1
 5106.12  5510.2  223.05 5727.27  7890.5  229.97
Permanent Ineff=
       T       T
Bank Sta=4616.2,5059.5
XS Rating Curve= 0 ,0
Exp/Cntr=0.3,0.1

Type RM Length L Ch R = 1 ,84940   ,1375,1375,1375
BEGIN DESCRIPTION:
SULPHUR CREEK 81.0
END DESCRIPTION:
XS GIS Cut Line= 4
      2266325.14     13392935.99      2265604.72     13392870.49
      2264045.91     13393184.87      2262422.19     13393106.31
#Sta/Elev= 30
  3940.6  232.91  4219.2  230.94  4560.6  230.94  4905.8  223.96  4936.4   221.8
  4973.2  214.22  4978.3  209.55  4994.6  207.99  4997.3  207.49  5000.6  207.99
  5048.6  215.32  5150.6  218.57  5211.8  217.61  5283.2  222.23  5487.2  222.65
  5793.3   219.2  5887.5  221.07  6058.5  228.36  6231.9  229.54  6392.5  228.24
  6520.6  223.28  6622.8  221.56  6702.9  222.85  6843.1  221.61  7349.9  232.92
  7458.6  234.72  7787.2  236.93  7795.4  237.03  7801.6   237.4  7879.8  238.62
#Mann= 8 ,-1 , 0
  3940.6     .16       0  4994.6     .07       0  5000.6     .16       0
  7349.9     .05       0  7458.6      .1       0  7787.2     .05       0
  7795.4      .1       0  7801.6     .05       0
#XS Ineff= 2 ,-1
 5334.69 5991.84  223.36 6227.27  7879.8  229.62
Permanent Ineff=
       T       T
Bank Sta=4936.4,5283.2
XS Rating Curve= 0 ,0
Exp/Cntr=0.3,0.1

Type RM Length L Ch R = 1 ,83565   ,1010,1010,1010
BEGIN DESCRIPTION:
Mapping XS dd27b473
END DESCRIPTION:
XS GIS Cut Line= 3
      2265565.43     13392136.94      2265198.64     13392045.25
      2262762.46     13392071.44
#Sta/Elev= 30
  3760.8  231.34  4279.8  227.33  4509.8  219.44  4519.8  219.34  4749.2  217.88
  4809.8  215.77  4869.8   215.4  4899.8  216.57  4909.8  214.08  4929.8  212.27
  4989.8  211.28  4996.8  203.74  4999.6  203.24  5009.8  204.04  5019.8  213.49
  5029.8  216.19 5033.24  219.49  5039.9   223.7  5059.9  223.99  5218.1  222.16
  5415.4  223.72  5523.4  222.32  5621.6  218.94    5684  219.36  5916.5  221.49
  6014.8  223.01  6223.2  225.96  6429.1  227.99  6506.3  228.99  6575.2  229.72
#Mann= 13 ,-1 , 0
  3760.8     .05       0  4519.8     .07       0  5059.9      .1       0
  5218.1     .05       0  5415.4      .1       0  5523.4     .05       0
  5621.6      .1       0    5684     .05       0  5916.5      .1       0
  6014.8     .05       0  6223.2      .1       0  6429.1     .05       0
  6506.3      .1       0
#XS Ineff= 1 ,-1
  5049.5 6113.86  224.31
Permanent Ineff=
       T
Bank Sta=4509.8,5033.24
XS Rating Curve= 0 ,0
Exp/Cntr=0.3,0.1

Type RM Length L Ch R = 1 ,82555   ,1196,1196,1196
BEGIN DESCRIPTION:
SULPHUR CREEK 80.0
END DESCRIPTION:
XS GIS Cut Line= 4
      2266128.65     13391966.62      2265735.71     13391586.77
      2264504.38     13391075.91       2262291.7     13390997.35
#Sta/Elev= 30
  3368.7   230.5  3489.4  231.89  4021.3  230.36  4172.9  222.77  4373.6  217.58
  4703.4  216.85  4757.5  216.36  4799.3  213.76  4970.2  210.76  4984.9  208.28
  4996.5  204.17  4999.3  203.67  5002.5  204.17  5017.3   210.5  5060.7  216.93
  5082.3  224.08  5114.6   223.9  5179.2  223.81  5585.2  221.36  5735.3  217.72
  5785.3   214.6  5859.4  217.61  6030.3  219.53  6175.6  218.97  6293.9  214.45
  6435.7  221.01  6555.9  222.12    6923  229.68  7036.5   232.1  7462.4  242.03
#Mann= 13 ,-1 , 0
  3368.7     .05       0  4373.6      .1       0  4799.3     .12       0
  4996.5     .07       0  5002.5     .12       0  5114.6      .1       0
  5179.2     .05       0  5859.4      .1       0  6030.3     .05       0
  6293.9      .1       0  6555.9     .05       0    6923      .1       0
  7036.5     .05       0
#XS Ineff= 2 , 0
       0                 5096.59       0  224.53
Permanent Ineff=
       T       T
Bank Sta=4703.4,5060.7
XS Rating Curve= 0 ,0
Exp/Cntr=0.3,0.1

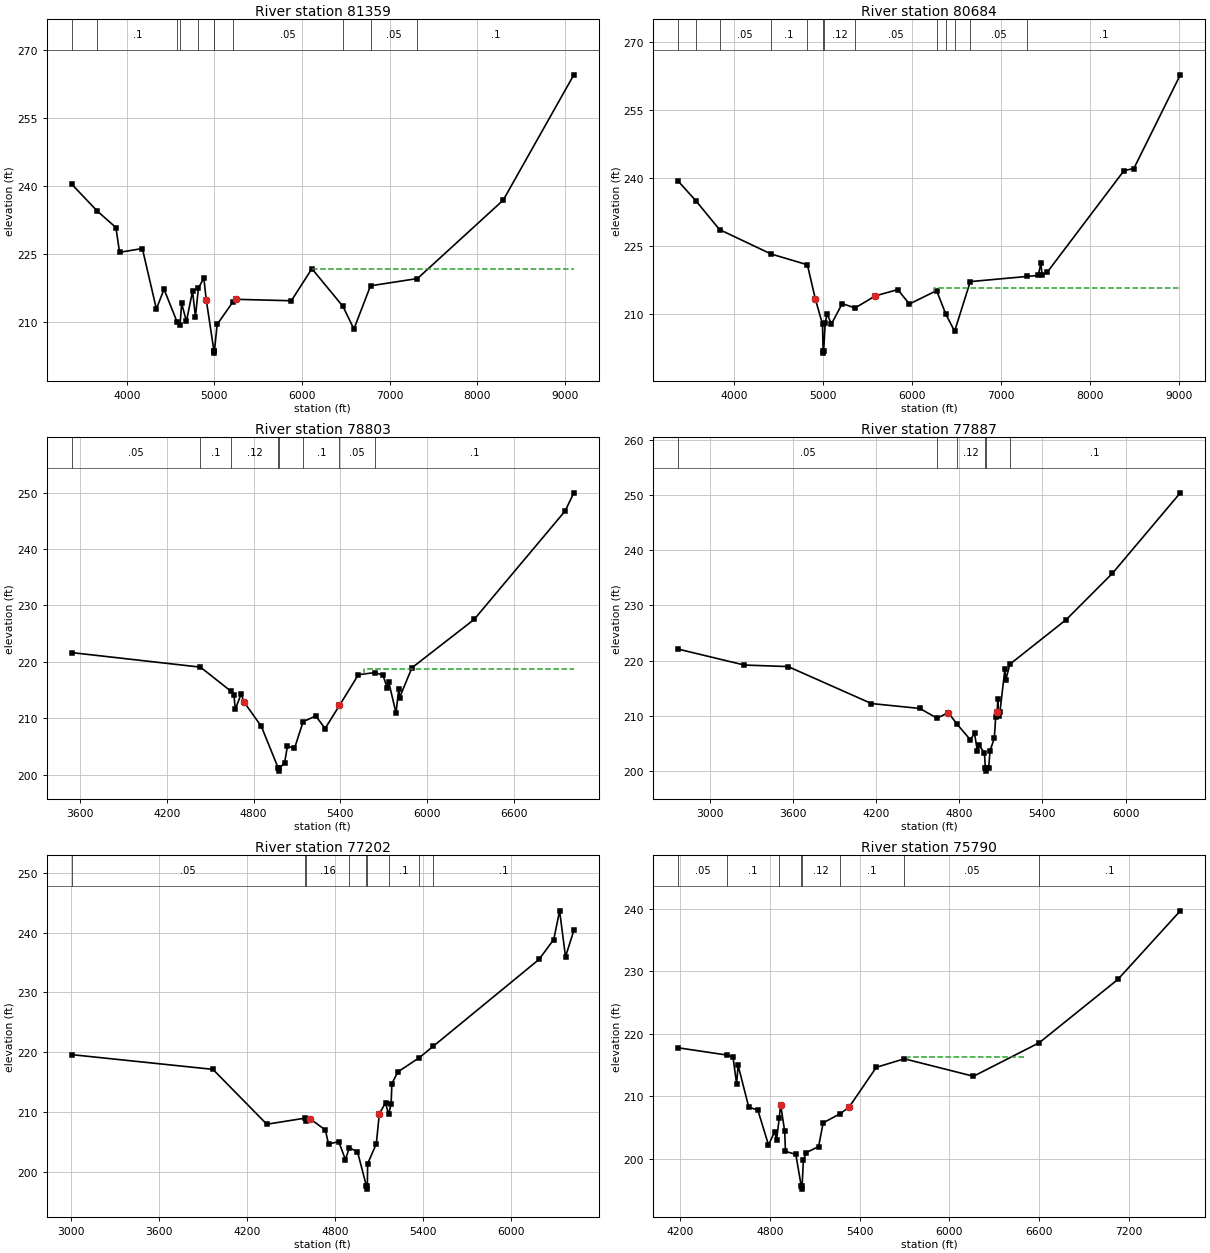
Type RM Length L Ch R = 1 ,81359   ,675,675,675
BEGIN DESCRIPTION:
SULPHUR CREEK 78.0
END DESCRIPTION:
XS GIS Cut Line= 3
      2267337.76     13391046.87      2265737.72     13390646.85
      2261737.72     13389846.86
#Sta/Elev= 30
  3371.7  240.34  3663.5  234.41  3876.8  230.77  3918.1   225.3  4178.3  226.14
  4338.1  212.82  4425.7  217.15  4576.7  209.84  4607.9  209.27  4626.7  214.02
  4680.8  210.09  4750.4  216.71  4783.9  211.13  4817.8  217.39  4879.3  219.65
  4907.6  214.76  4994.8  203.57  4997.5  203.07  5000.8  203.57  5031.2  209.39
  5213.1  214.42  5245.3  214.94  5877.6  214.62  6112.2  221.69  6466.4  213.38
  6591.5  208.39  6780.8  217.92  7316.6  219.52  8294.6  236.81  9100.2  264.45
#Mann= 11 ,-1 , 0
  3371.7     .05       0  3663.5      .1       0  4576.7     .12       0
  4607.9      .1       0  4817.8     .12       0  4994.8     .07       0
  5000.8     .12       0  5213.1     .05       0  6466.4      .1       0
  6780.8     .05       0  7316.6      .1       0
#XS Ineff= 2 , 0
                         6108.93          221.66
Permanent Ineff=
       T       T
Bank Sta=4907.6,5245.3
XS Rating Curve= 0 ,0
Exp/Cntr=0.3,0.1

Type RM Length L Ch R = 1 ,80684   ,1881,1881,1881
BEGIN DESCRIPTION:
SULPHUR CREEK 77.0
END DESCRIPTION:
XS GIS Cut Line= 4
      2267237.74     13390896.87      2266183.35     13390178.82
      2264145.11     13389927.59      2261837.75     13389696.86
#Sta/Elev= 30
  3366.4  239.32  3569.1  234.89    3832  228.59  4410.7   223.2  4820.4  220.81
  4909.7  213.25  4990.3  207.67  4997.4  201.78  5000.1  201.28  5003.4  201.78
  5020.5  207.87  5040.7  209.96  5091.1  207.74    5212  212.22  5357.1  211.27
  5584.8  213.94  5836.7  215.32  5967.7  212.14  6273.9   215.1  6376.9  209.91
  6476.2  206.12  6652.1  217.09  7289.6  218.23  7416.7  218.46  7446.8  221.17
  7459.4  218.57  7517.2  219.15  8381.5  241.62    8492  242.09  9014.6   262.8
#Mann= 13 ,-1 , 0
  3366.4     .05       0  3569.1      .1       0    3832     .05       0
  4410.7      .1       0  4820.4     .12       0  4997.4     .07       0
  5003.4     .12       0  5357.1     .05       0  6273.9      .1       0
  6376.9     .12       0  6476.2      .1       0  6652.1     .05       0
  7289.6      .1       0
#XS Ineff= 2 , 0
                         6248.82          215.67
Permanent Ineff=
       T       T
Bank Sta=4909.7,5584.8
XS Rating Curve= 0 ,0
Exp/Cntr=0.3,0.1

Type RM Length L Ch R = 1 ,78803   ,916,916,916
BEGIN DESCRIPTION:
Mapping XS a7acf00d
END DESCRIPTION:
XS GIS Cut Line= 4
      2265721.36     13389467.13      2264941.83     13389349.47
      2263243.07     13389467.13      2262257.64     13389430.36
#Sta/Elev= 30
  3540.4  221.63  4432.3  219.05  4642.2  214.81  4663.7   214.2  4673.7  211.59
  4713.8  214.28  4733.8  212.88  4854.1  208.54  4971.4  201.12  4974.2  200.62
  4977.4  201.12  5014.5  202.04  5034.6  205.05  5083.3  204.65  5143.2  209.39
  5230.8   210.4  5295.2  208.17  5394.9  212.27  5525.9  217.71  5640.3  218.09
  5696.1  217.63  5726.2  215.29  5736.2  216.39  5786.4  210.94  5805.9  215.26
    5811  213.66  5896.6  218.94  6327.1   227.5  6957.6  246.74  7017.7  249.95
#Mann= 8 ,-1 , 0
  3540.4     .05       0  4432.3      .1       0  4642.2     .12       0
  4971.4     .07       0  4977.4     .12       0  5143.2      .1       0
  5394.9     .05       0  5640.3      .1       0
#XS Ineff= 2 , 0
                         5565.88          218.69
Permanent Ineff=
       T       T
Bank Sta=4733.8,5394.9
XS Rating Curve= 0 ,0
Exp/Cntr=0.3,0.1

Type RM Length L Ch R = 1 ,77887   ,685,685,685
BEGIN DESCRIPTION:
Mapping XS 71eee639
END DESCRIPTION:
XS GIS Cut Line= 3
      2265816.97     13389261.22      2263000.39     13388702.32
      2262250.33     13388621.43
#Sta/Elev= 30
  2769.6  222.08    3248  219.19    3564  218.91  4165.5  212.21  4515.2  211.32
  4639.2  209.55  4719.9  210.57  4782.9   208.5  4879.2  205.65  4909.8  206.79
  4930.2  203.59  4940.4  204.72  4981.1  203.26  4988.3  200.46  4991.1  199.96
  4994.3  200.46  5011.7   200.5  5021.9  203.66  5052.5  205.92  5062.7  209.86
  5072.9  210.65  5078.2     213  5083.3  209.94  5093.3  210.74  5129.3  218.46
  5134.4  216.41  5164.5  219.33  5572.5  227.44  5905.3  235.81  6395.5  250.41
#Mann= 6 ,-1 , 0
  2769.6     .05       0  4639.2      .1       0  4782.9     .12       0
  4988.3     .07       0  4994.3     .12       0  5164.5      .1       0
Bank Sta=4719.9,5072.9
XS Rating Curve= 0 ,0
Exp/Cntr=0.3,0.1

Type RM Length L Ch R = 1 ,77202   ,1412,1412,1412
BEGIN DESCRIPTION:
SULPHUR CREEK 76.0
END DESCRIPTION:
XS GIS Cut Line= 3
      2265824.34     13388922.95      2263323.97     13388114.01
      2262531.24     13388033.27
#Sta/Elev= 30
  3002.1  219.59  3965.5  217.13  4332.9  207.96  4590.5  208.96  4603.1  208.55
  4626.2   208.9  4732.7  206.99  4753.8  204.64  4823.5  205.05  4869.4  202.03
  4895.5  204.01  4951.5  203.37  5012.5  197.61  5015.3  197.11  5018.5  197.61
  5020.8  201.36  5079.6  204.67  5100.6  209.73  5142.6  211.53  5163.3   209.6
  5180.8   211.3  5186.1  214.76  5226.7   216.7  5373.9   219.1  5468.5     221
  6189.2   235.5  6289.7  238.83  6329.9  243.63  6370.1  235.95  6426.9  240.36
#Mann= 9 ,-1 , 0
  3002.1     .05       0  4590.5     .12       0  4603.1     .16       0
  4895.5     .12       0  5012.5     .07       0  5018.5     .12       0
  5163.3      .1       0  5373.9     .05       0  5468.5      .1       0
Bank Sta=4626.2,5100.6
XS Rating Curve= 0 ,0
Exp/Cntr=0.3,0.1

Type RM Length L Ch R = 1 ,75790   ,1118,1118,1118
BEGIN DESCRIPTION:
SULPHUR CREEK 75.0
END DESCRIPTION:
XS GIS Cut Line= 3
      2266022.87     13388025.76      2263684.31     13387613.94
      2262700.77     13387599.26
#Sta/Elev= 30
  4186.8  217.78  4510.5  216.63  4553.9  216.31  4577.9  212.02    4588  214.97
  4659.1   208.3    4720  207.83  4791.1  202.26  4831.7  204.32  4845.3  203.12
  4863.1  206.54  4872.3   208.7  4899.5  204.42  4904.6  201.23  4973.9  200.75
    5010   195.7  5012.7   195.2    5016   195.7  5024.6   199.9    5045  201.05
  5126.2     202  5156.6  205.79  5269.1  207.23  5329.3  208.27    5512  214.66
  5699.2  216.02  6161.9  213.23  6601.2  218.58    7128  228.71    7545  239.66
#Mann= 8 ,-1 , 0
  4186.8     .05       0  4510.5      .1       0  4863.1     .12       0
    5010     .07       0    5016     .12       0  5269.1      .1       0
  5699.2     .05       0  6601.2      .1       0
#XS Ineff= 1 ,-1
  5725.6 6506.36  216.32
Permanent Ineff=
       T
Bank Sta=4872.3,5329.3
XS Rating Curve= 0 ,0
Exp/Cntr=0.3,0.1

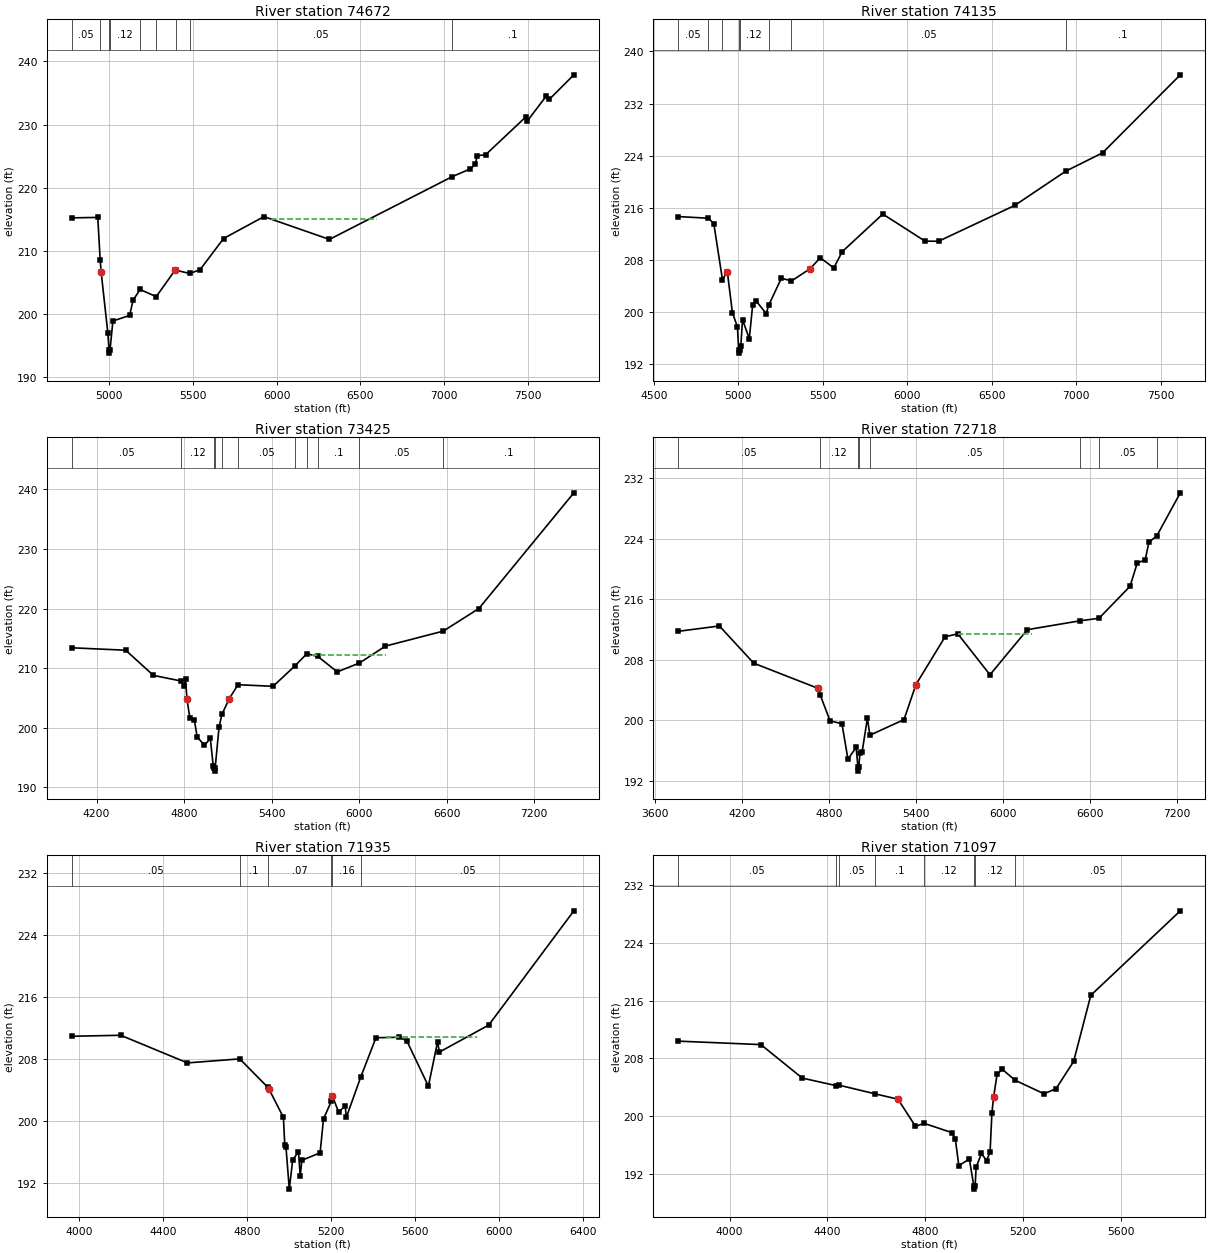
Type RM Length L Ch R = 1 ,74672   ,537,537,537
BEGIN DESCRIPTION:
SULPHUR CREEK 74.0
END DESCRIPTION:
XS GIS Cut Line= 2
      2265743.36     13387055.04      2262751.56     13387143.26
#Sta/Elev= 30
  4778.7  215.23  4934.4   215.3  4948.6   208.6  4954.4  206.68  4994.4     197
  5001.4  194.33  5004.2  193.83  5007.4  194.33  5024.4  198.91  5124.5   199.8
  5144.5  202.19  5186.9   203.9  5282.7  202.76  5394.6  206.94  5398.5  206.95
  5483.4  206.43  5544.7  207.05  5684.1  211.96  5924.8  215.43    6315  211.82
  7048.3  221.77  7155.4  222.98  7185.4  223.75  7195.4  225.08  7245.4   225.2
  7485.5   231.2  7495.5  230.59  7605.6  234.44  7625.6  233.98  7771.8  237.86
#Mann= 9 ,-1 , 0
  4778.7     .05       0  4948.6     .12       0  5001.4     .07       0
  5007.4     .12       0  5186.9      .1       0  5282.7     .05       0
  5398.5      .1       0  5483.4     .05       0  7048.3      .1       0
#XS Ineff= 1 ,-1
 5975.25 6599.01  215.08
Permanent Ineff=
       T
Bank Sta=4954.4,5394.6
XS Rating Curve= 0 ,0
Exp/Cntr=0.3,0.1

Type RM Length L Ch R = 1 ,74135   ,710,710,710
BEGIN DESCRIPTION:
SULPHUR CREEK 73.0
END DESCRIPTION:
XS GIS Cut Line= 2
      2265728.73     13386540.27      2262757.75     13386628.51
#Sta/Elev= 30
  4643.2  214.65  4822.2  214.39  4854.3  213.58  4905.6  204.96  4934.3  206.21
  4964.4  199.91  4994.4  197.71  5001.4  194.18  5004.1  193.68  5007.4  194.18
  5014.4   194.8  5024.4  198.83  5064.4   195.9  5084.4  201.05  5104.4  201.72
  5164.4  199.75    5180  201.07  5254.5  205.19  5314.1  204.76  5424.6  206.64
  5484.6  208.33  5564.6  206.76  5614.6  209.26  5854.7  215.03  6104.9  210.87
  6184.9  210.86  6635.1  216.35  6937.7  221.62  7155.3  224.43  7615.5  236.41
#Mann= 8 ,-1 , 0
  4643.2     .05       0  4822.2     .16       0  4905.6     .12       0
  5001.4     .07       0  5007.4     .12       0    5180      .1       0
  5314.1     .05       0  6937.7      .1       0
#XS Ineff= 1 ,-1
 5871.29 6643.56   214.3
Permanent Ineff=
       T
Bank Sta=4934.3,5424.6
XS Rating Curve= 0 ,0
Exp/Cntr=0.3,0.1

Type RM Length L Ch R = 1 ,73425   ,707,707,707
BEGIN DESCRIPTION:
Mapping XS 7551b0e2
END DESCRIPTION:
XS GIS Cut Line= 2
      2266008.16     13385951.95      2262566.49     13385937.25
#Sta/Elev= 30
  4029.6  213.42    4400  213.01    4590  208.79  4781.8  207.84    4800  206.97
    4810   208.2    4820  204.81    4840  201.58    4870  201.37    4890  198.47
    4940  197.06    4980  198.23    5000  193.58    5007  193.24  5009.8  192.74
    5013  193.24    5040  200.17  5059.7  202.27    5110   204.9  5169.6  207.23
    5410  206.96  5559.8  210.38    5641  212.42  5715.4  211.99  5850.1  209.38
    6002  210.87  6180.1   213.7  6575.8  216.21  6820.1  219.99  7471.3   239.4
#Mann= 11 ,-1 , 0
  4029.6     .05       0  4781.8     .12       0    5007     .07       0
    5013     .12       0  5059.7      .1       0  5169.6     .05       0
  5559.8      .1       0    5641     .05       0  5715.4      .1       0
    6002     .05       0  6575.8      .1       0
#XS Ineff= 1 ,-1
 5678.22 6183.17  212.27
Permanent Ineff=
       T
Bank Sta=4820,5110
XS Rating Curve= 0 ,0
Exp/Cntr=0.3,0.1

Type RM Length L Ch R = 1 ,72718   ,783,783,783
BEGIN DESCRIPTION:
SULPHUR CREEK 72.0
END DESCRIPTION:
XS GIS Cut Line= 3
      2266103.78     13385569.56      2263515.17     13384922.41
      2262721.87     13384878.33
#Sta/Elev= 30
  3759.6  211.76  4044.2  212.47  4281.1  207.54  4724.5  204.21  4739.4  203.34
  4806.9  199.92  4889.4  199.52  4930.6  194.84  4987.2  196.38  4999.8  193.75
  5002.5  193.25  5005.8  193.75  5013.1  195.69  5028.4  195.79  5064.5  200.23
  5082.2  198.01    5317  200.07  5399.5  204.71  5600.5  211.04  5688.1  211.43
  5909.9  206.01  6167.6  211.98  6529.3  213.15  6661.9  213.49    6876  217.73
  6926.1  220.85  6979.9  221.18  7006.2  223.57    7060  224.39  7222.4   230.1
#Mann= 8 ,-1 , 0
  3759.6     .05       0  4739.4     .12       0  4999.8     .07       0
  5005.8     .12       0  5082.2     .05       0  6529.3      .1       0
  6661.9     .05       0    7060      .1       0
#XS Ineff= 1 ,-1
 5689.53 6198.73  211.45
Permanent Ineff=
       T
Bank Sta=4724.5,5399.5
XS Rating Curve= 0 ,0
Exp/Cntr=0.3,0.1

Type RM Length L Ch R = 1 ,71935   ,838,838,838
BEGIN DESCRIPTION:
SULPHUR CREEK 71.0
END DESCRIPTION:
XS GIS Cut Line= 3
       2266030.2     13385143.02      2264287.33     13384179.66
      2264074.22     13383841.62
#Sta/Elev= 30
  3963.6  210.96    4197  211.09  4514.9  207.52    4764  208.04  4896.9  204.39
  4903.4  204.12  4971.9  200.48  4978.3  196.93    4984  196.68  4999.8  191.22
  5016.1  194.99  5043.5  196.05  5051.9   192.9  5059.6  194.94  5146.6  195.91
  5162.7  200.28  5200.4   202.6  5205.5   203.2  5234.7  201.17  5265.8  201.96
  5271.5   200.5  5340.4  205.72  5412.4  210.77  5521.2  210.83    5559  210.39
  5662.1  204.52  5705.6  210.22  5714.6  208.92  5949.6  212.41  6354.6  227.16
#Mann= 6 ,-1 , 0
  3963.6     .05       0    4764      .1       0  4896.9     .07       0
  5200.4     .12       0  5205.5     .16       0  5340.4     .05       0
#XS Ineff= 1 ,-1
 5464.64 5893.21  210.93
Permanent Ineff=
       T
Bank Sta=4903.4,5205.5
XS Rating Curve= 0 ,0
Exp/Cntr=0.3,0.1

Type RM Length L Ch R = 1 ,71097   ,887,887,887
BEGIN DESCRIPTION:
SULPHUR CREEK 70.0
END DESCRIPTION:
XS GIS Cut Line= 3
      2266059.66     13384650.34       2264706.5     13383539.87
      2264412.53     13383466.37
#Sta/Elev= 30
  3789.6   210.4    4128  209.92  4297.4  205.28  4436.4  204.23  4448.9  204.29
  4594.8   203.1  4688.5  202.36  4760.2   198.6  4795.7  199.01  4908.8  197.73
  4923.1  196.85  4937.5  193.15  4980.5  194.08  4998.3   190.4  5001.1   189.9
  5004.3   190.4  5008.1  192.92    5030  194.84  5050.8  193.85  5065.2  195.02
  5072.8  200.48  5079.5  202.63  5093.9  205.79  5114.7  206.51  5167.6  204.98
  5285.5  203.11    5335  203.81  5406.8  207.58  5477.1  216.75  5843.1  228.45
#Mann= 8 ,-1 , 0
  3789.6     .05       0  4436.4      .1       0  4448.9     .05       0
  4594.8      .1       0  4795.7     .12       0  4998.3     .07       0
  5004.3     .12       0  5167.6     .05       0
Bank Sta=4688.5,5079.5
XS Rating Curve= 0 ,0
Exp/Cntr=0.3,0.1

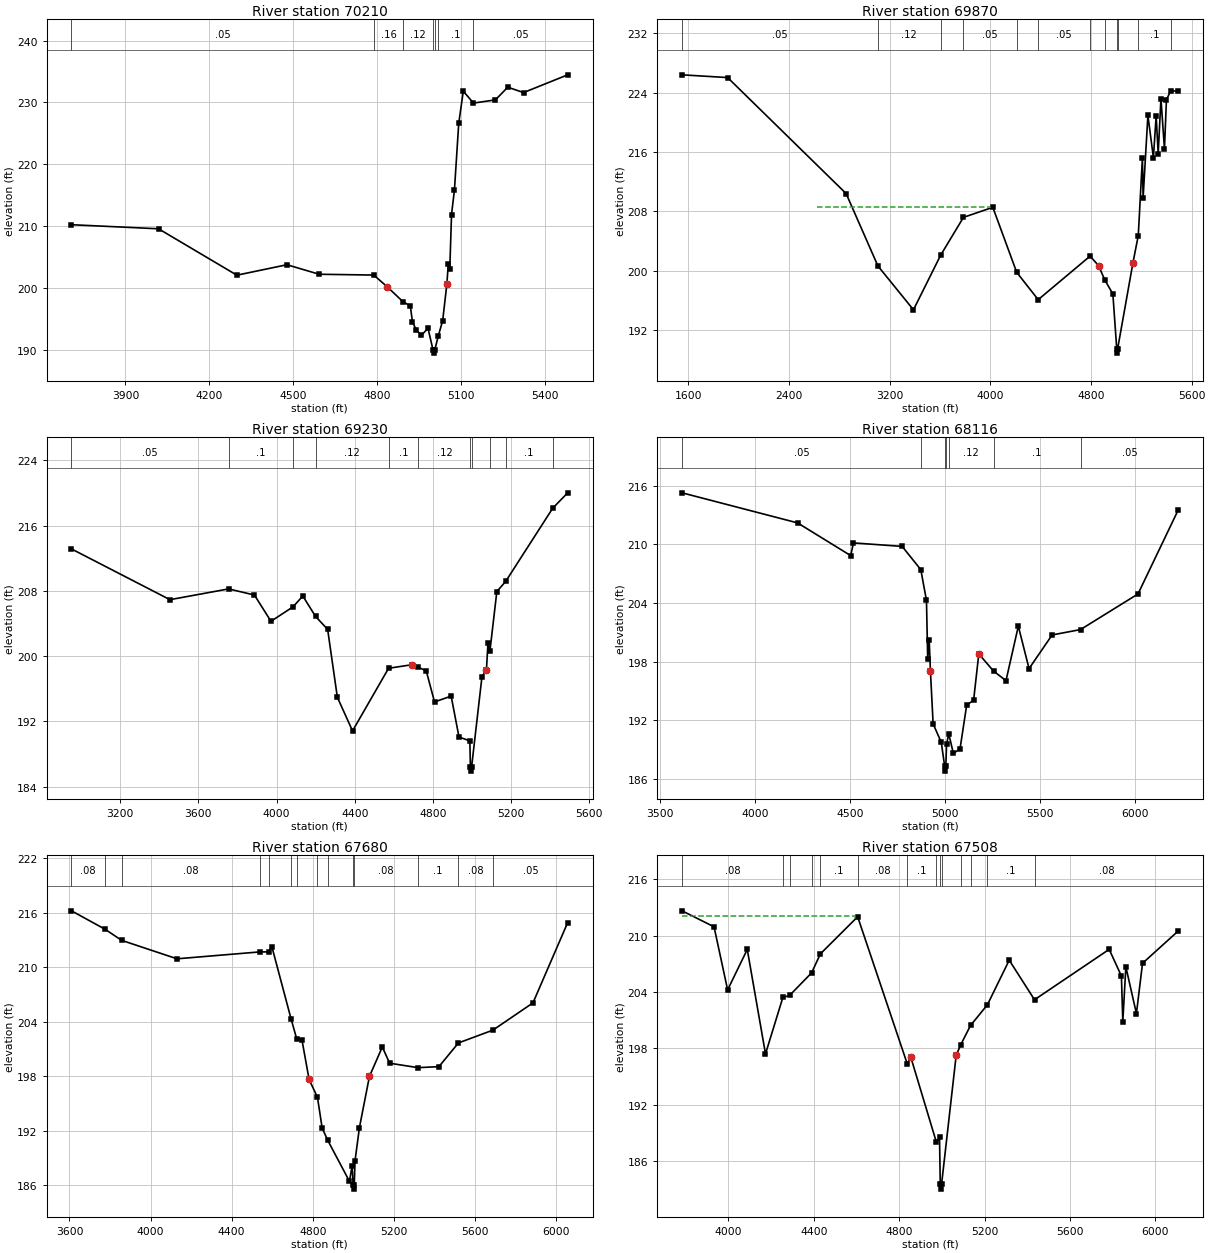
Type RM Length L Ch R = 1 ,70210   ,340,340,340
BEGIN DESCRIPTION:
SULPHUR CREEK 69.0
END DESCRIPTION:
XS GIS Cut Line= 3
      2266147.87      13384569.4      2265691.93     13383157.46
      2265456.63     13382988.34
#Sta/Elev= 30
  3707.4  210.24  4018.6  209.58  4298.5  202.08  4477.5  203.77  4592.8  202.23
  4787.7   202.1  4835.2  200.23  4892.4  197.78  4918.5  197.11    4926  194.53
  4939.6  193.23    4958  192.36  4981.6   193.5  4999.6  189.98  5002.4  189.48
  5005.6  189.98  5018.6   192.3  5034.1  194.75 5048.86  200.58  5054.1  203.85
  5059.4  203.03  5065.7  211.89  5076.2  215.93  5091.4  226.61  5107.7  231.83
  5144.1   229.9  5222.5  230.42  5266.7  232.47  5323.1   231.6  5480.9  234.47
#Mann= 7 ,-1 , 0
  3707.4     .05       0  4787.7     .16       0  4892.4     .12       0
  4999.6     .07       0  5005.6     .12       0  5018.6      .1       0
  5144.1     .05       0
Bank Sta=4835.2,5048.86
XS Rating Curve= 0 ,0
Exp/Cntr=0.3,0.1

Type RM Length L Ch R = 1 ,69870   ,640,640,640
BEGIN DESCRIPTION:
SULPHUR CREEK 68.0
END DESCRIPTION:
XS GIS Cut Line= 4
      2268078.44     13386011.52       2267318.9     13384731.15
      2266617.08     13384265.44       2265847.1     13382850.34
#Sta/Elev= 30
    1552  226.38    1914  226.01  2855.3  210.41  3107.9  200.67  3390.2  194.78
  3606.5  202.13  3787.5  207.21  4020.7  208.56  4210.4  199.82    4381  196.14
  4793.6     202  4860.4  200.72  4911.1  198.76  4974.3  196.91  5005.4  189.45
  5008.2  188.95  5011.4  189.45  5133.7  201.09  5176.1  204.76    5209  215.22
  5214.6  209.86  5252.6  220.93  5296.3  215.24  5318.2  220.89  5334.3  215.75
  5356.2  223.19  5384.1  216.42  5399.9  223.02  5432.5  224.19    5494  224.22
#Mann= 12 ,-1 , 0
    1552     .05       0  3107.9     .12       0  3606.5      .1       0
  3787.5     .05       0  4210.4      .1       0    4381     .05       0
  4793.6      .1       0  4911.1     .12       0  5005.4     .07       0
  5011.4     .12       0  5176.1      .1       0  5432.5     .05       0
#XS Ineff= 1 ,-1
 2626.59 3998.59  208.66
Permanent Ineff=
       T
Bank Sta=4860.4,5133.7
XS Rating Curve= 0 ,0
Exp/Cntr=0.3,0.1

Type RM Length L Ch R = 1 ,69230   ,1114,1114,1114
BEGIN DESCRIPTION:
SULPHUR CREEK 67.0
END DESCRIPTION:
XS GIS Cut Line= 4
       2268036.1     13384647.25      2267577.67     13384277.57
      2266810.23     13383477.33       2266525.5     13382685.65
#Sta/Elev= 30
  2950.5  213.14  3454.4  206.92  3754.5  208.24  3886.6  207.49  3971.2  204.27
    4084  206.04  4134.1  207.37  4199.5  204.86  4261.2  203.28  4310.8  194.96
  4388.5  190.83    4573  198.51  4691.2  198.94  4725.6  198.62  4765.6   198.2
  4808.1  194.38  4893.1   195.1  4933.3  190.08  4988.7  189.61  4991.7   186.4
  4994.5   185.9  4997.7   186.4  5050.8  197.48  5073.8  198.35  5081.6  201.63
  5091.3  200.58  5126.9  207.92  5172.2  209.16    5413  218.14  5489.5  220.02
#Mann= 11 ,-1 , 0
  2950.5     .05       0  3754.5      .1       0    4084     .16       0
  4199.5     .12       0    4573      .1       0  4725.6     .12       0
  4991.7     .07       0  4997.7     .12       0  5091.3     .16       0
  5172.2      .1       0    5413     .05       0
Bank Sta=4691.2,5073.8
XS Rating Curve= 0 ,0
Exp/Cntr=0.3,0.1

Type RM Length L Ch R = 1 ,68116   ,436,436,436
BEGIN DESCRIPTION:
SULPHUR CREEK 66.0
END DESCRIPTION:
XS GIS Cut Line= 4
      2268582.38     13384404.36      2267880.97     13383452.94
      2267547.64     13383175.16      2266735.17     13382591.85
#Sta/Elev= 30
  3614.1  215.29  4223.1  212.21    4503  208.86  4517.6  210.16  4774.5   209.8
  4872.8  207.42  4902.6  204.27  4909.1  198.27  4916.9  200.24  4923.4  197.08
  4937.7  191.62  4980.7  189.73  4998.5  187.28  5001.2  186.78  5004.5  187.28
  5008.6  189.52    5020  190.61  5044.5  188.59  5079.6  189.07  5114.7  193.55
  5151.2  194.05  5178.5  198.79  5256.2  197.03  5321.8  196.05  5386.9  201.63
  5443.4  197.28    5565  200.73  5714.7  201.28  6017.8  204.93  6230.2  213.55
#Mann= 7 ,-1 , 0
  3614.1     .05       0  4872.8     .16       0  4998.5     .07       0
  5004.5     .16       0    5020     .12       0  5256.2      .1       0
  5714.7     .05       0
Bank Sta=4923.4,5178.5
XS Rating Curve= 0 ,0
Exp/Cntr=0.3,0.1

Type RM Length L Ch R = 1 ,67680   ,172,172,172
BEGIN DESCRIPTION:
Mapping XS dd0859e7
END DESCRIPTION:
XS GIS Cut Line= 4
      2268637.93     13383932.12      2267894.86     13383112.66
      2267499.03      13382758.5      2266846.25     13382279.33
#Sta/Elev= 30
    3610  216.19    3775  214.17  3857.5  212.94  4130.4  210.91  4539.2  211.67
    4583  211.67    4598  212.26  4692.5  204.33  4720.4  202.12  4746.6  201.98
  4781.8  197.63  4823.1  195.66  4846.1  192.29  4873.5  190.94  4980.7  186.42
  4994.1  188.14  4998.6  186.06  5001.3  185.56  5004.6  186.06  5008.3  188.68
    5030  192.34  5079.3  197.96  5142.9  201.21  5178.8  199.42  5318.7  198.93
    5422  199.04  5518.2  201.65  5688.3  203.06  5885.8  206.06  6057.1   214.9
#Mann= 14 ,-1 , 0
    3610     .08       0    3775     .05       0  3857.5     .08       0
  4539.2     .05       0    4583     .08       0  4692.5     .16       0
  4720.4     .08       0  4823.1     .16       0  4873.5     .08       0
  4998.6     .07       0  5004.6     .08       0  5318.7      .1       0
  5518.2     .08       0  5688.3     .05       0
Bank Sta=4781.8,5079.3
XS Rating Curve= 0 ,0
Exp/Cntr=0.3,0.1

Type RM Length L Ch R = 1 ,67508   ,278,278,278
BEGIN DESCRIPTION:
SULPHUR CREEK 65.0
END DESCRIPTION:
XS GIS Cut Line= 3
        2268631.      13383675.2      2268040.69     13383001.55
       2266943.5     13382084.91
#Sta/Elev= 30
  3782.4  212.63  3932.3  210.93  3995.9  204.22    4088  208.52  4173.4  197.41
  4254.7  203.41  4286.4  203.63  4389.4  206.03  4430.6  208.05  4605.3     212
  4838.4   196.3  4853.5  197.12  4974.5  187.99  4988.9  188.55  4992.4  183.52
  4995.1  183.02  4998.4  183.52    5067  197.26  5088.3  198.38  5134.1  200.43
  5213.2  202.63  5315.5  207.38    5434  203.17    5784  208.53  5841.3  205.69
  5847.8  200.84  5862.1  206.67  5911.6   201.7  5940.2  207.05  6107.8  210.49
#Mann= 14 ,-1 , 0
  3782.4     .08       0  4254.7     .05       0  4286.4     .08       0
  4389.4     .05       0  4430.6      .1       0  4605.3     .08       0
  4838.4      .1       0  4974.5     .08       0  4992.4     .07       0
  4998.4     .08       0  5088.3      .1       0  5134.1     .08       0
  5213.2      .1       0    5434     .08       0
#XS Ineff= 2 , 0
         4594.77  212.06
Permanent Ineff=
       T       T
Bank Sta=4853.5,5067
XS Rating Curve= 0 ,0
Exp/Cntr=0.3,0.1