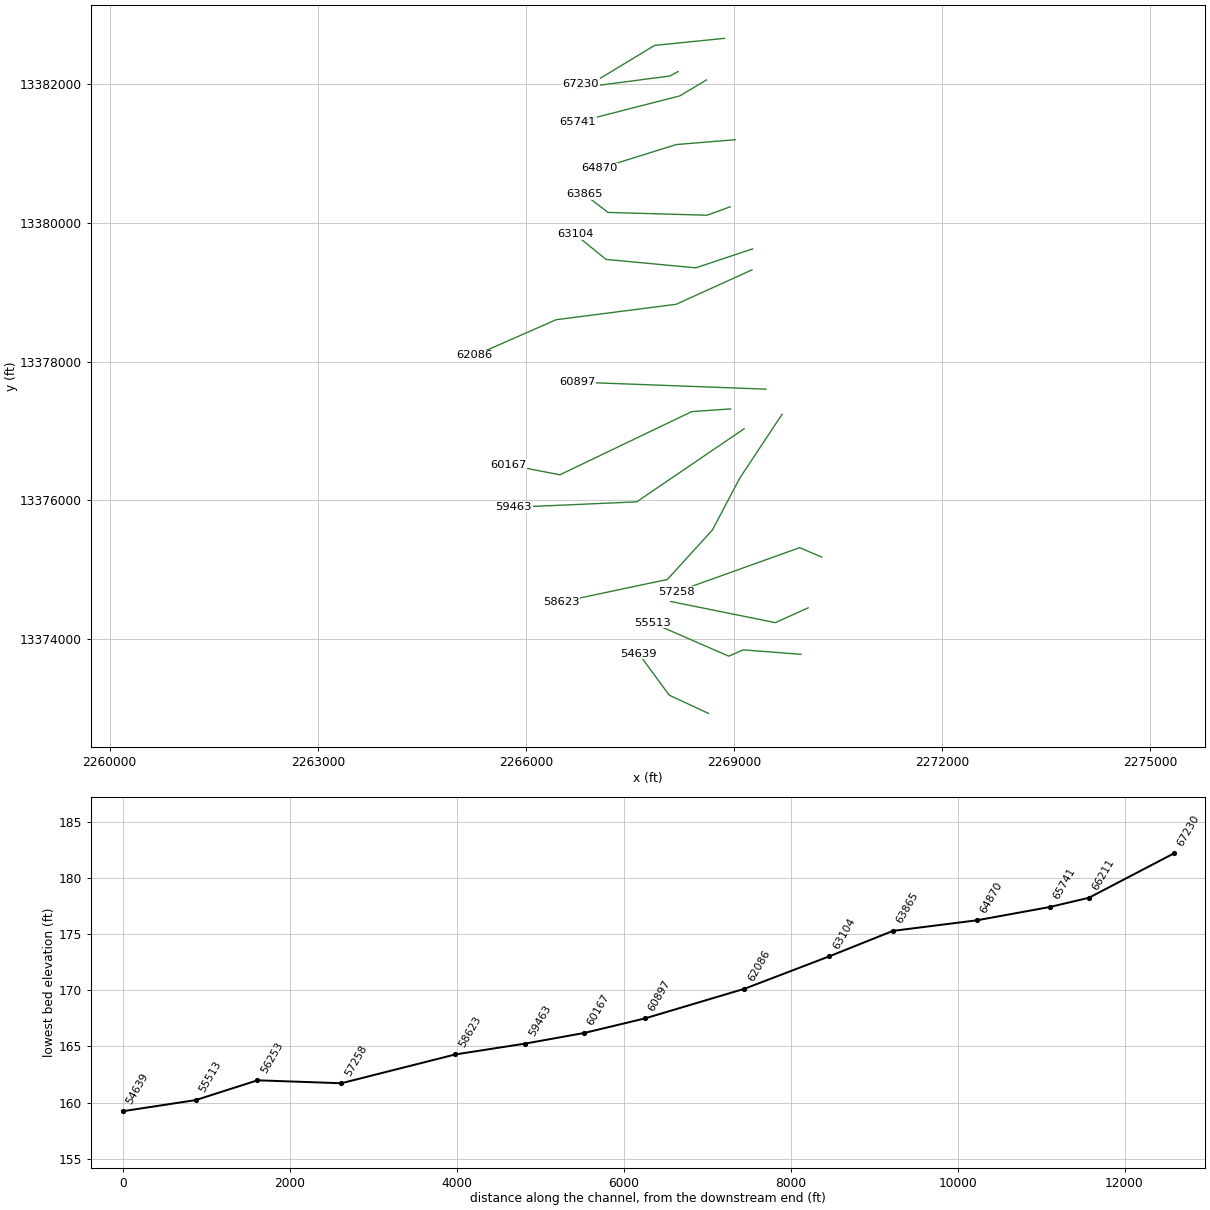
HEC-RAS study SULPHUR CREEK.prj: SULPHUR CREEK Base Level Engineering

--- SULPHUR CREEK.g01 (geometry) --- (continued)

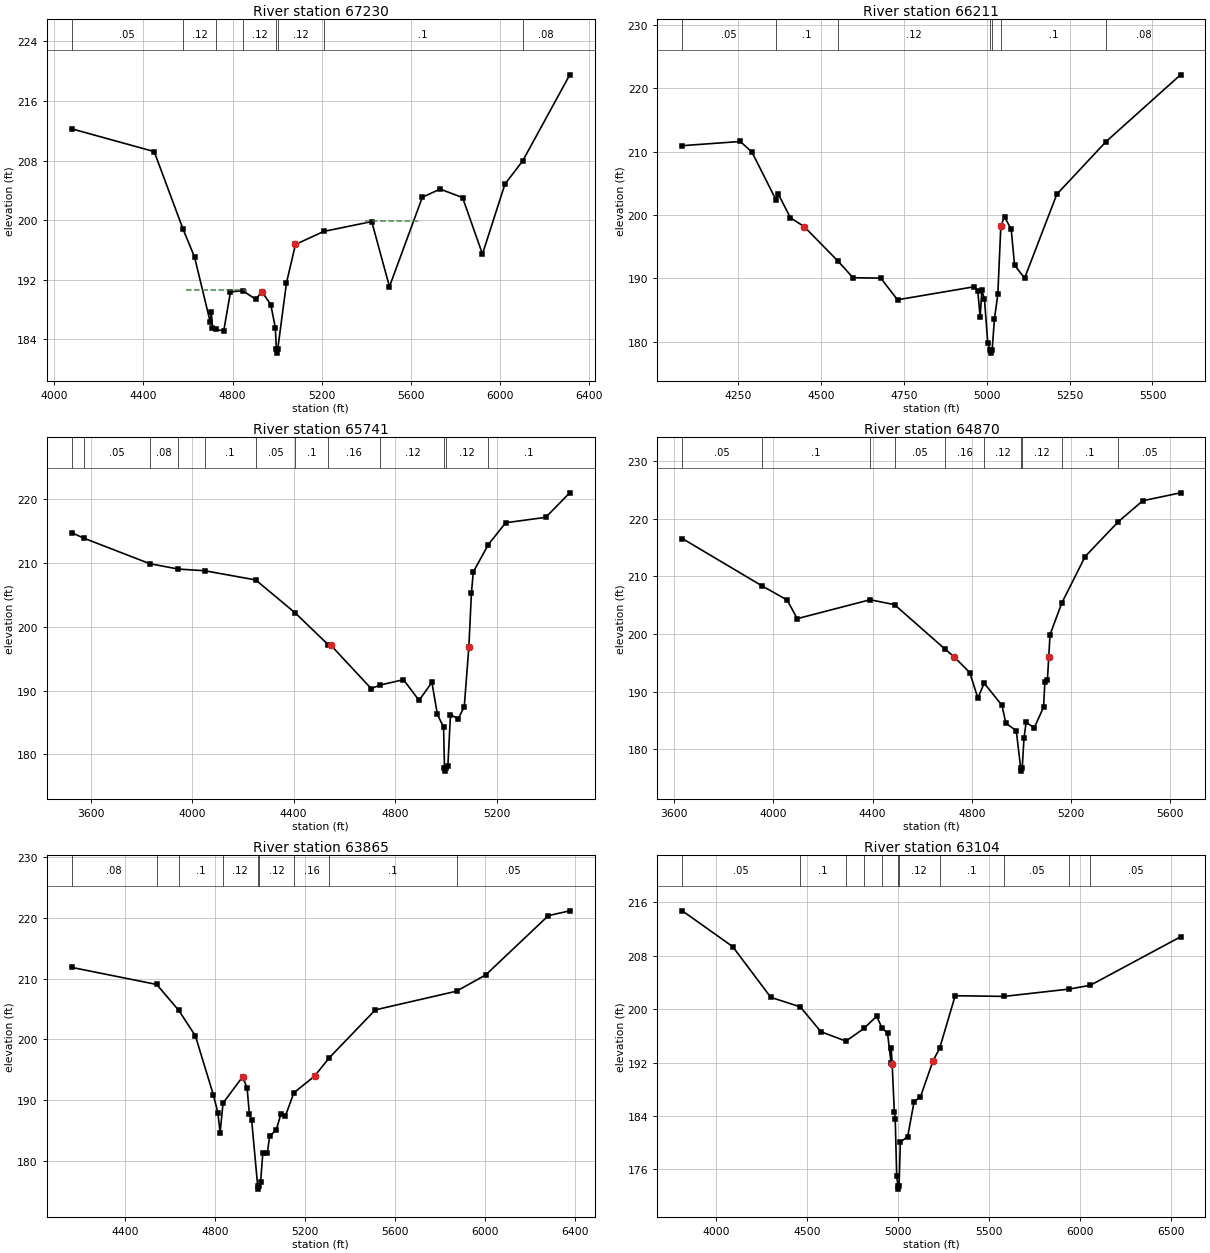
Type RM Length L Ch R = 1 ,67230   ,1019,1019,1019
BEGIN DESCRIPTION:
SULPHUR CREEK 64.0
END DESCRIPTION:
XS GIS Cut Line= 4
      2268866.25     13382664.92      2267857.16     13382562.74
      2266950.29     13382013.51      2266791.69     13382007.16
#Sta/Elev= 30
  4078.4  212.27  4448.8  209.21  4577.9  198.82  4629.7  195.06  4699.7  186.37
  4704.7  187.75  4710.1   185.6  4726.7  185.36  4760.4  185.13  4790.6  190.38
  4845.5  190.56  4904.5  189.38  4931.3  190.43  4971.5  188.67  4991.6  185.59
  4996.4  182.67  4999.1  182.17  5002.4  182.67  5041.8  191.61    5082  196.75
  5208.8   198.5  5423.9  199.82  5503.4  191.09  5650.7  203.08  5730.3  204.18
  5831.1  203.04  5920.3  195.46  6021.2  204.86  6100.8  207.97  6311.6  219.51
#Mann= 8 ,-1 , 0
  4078.4     .05       0  4577.9     .12       0  4726.7     .08       0
  4845.5     .12       0  4996.4     .07       0  5002.4     .12       0
  5208.8      .1       0  6100.8     .08       0
#XS Ineff= 3 ,-1
 4590.52 4859.26  190.59 5400.28 5644.27  199.94 5729.14 6086.28  204.05
Permanent Ineff=
       T       T       T
Bank Sta=4931.3,5082
XS Rating Curve= 0 ,0
Exp/Cntr=0.3,0.1

Type RM Length L Ch R = 1 ,66211   ,470,470,470
BEGIN DESCRIPTION:
Mapping XS af374e66
END DESCRIPTION:
XS GIS Cut Line= 3
      2268195.62     13382185.93      2268080.68     13382122.07
      2266721.55     13381943.41
#Sta/Elev= 30
  4082.2  210.93    4257  211.59  4292.2  209.91  4365.2  202.34  4370.9  203.36
  4408.3  199.56  4449.6  198.17  4551.8  192.72  4596.9  190.11  4680.7  190.04
  4731.1  186.63    4963  188.69  4973.1  188.06  4980.4  183.88  4985.4  188.12
  4993.3  186.75  5003.4  179.74  5010.5  178.72  5013.2  178.22  5016.5  178.72
  5023.5  183.67  5033.6  187.48  5042.7  198.27  5053.8  199.72    5074  197.73
  5084.1  192.09  5114.3  190.04  5211.5  203.27  5360.2  211.58  5584.5   222.1
#Mann= 7 ,-1 , 0
  4082.2     .05       0  4365.2      .1       0  4551.8     .12       0
  5010.5     .07       0  5016.5     .12       0  5042.7      .1       0
  5360.2     .08       0
Bank Sta=4449.6,5042.7
XS Rating Curve= 0 ,0
Exp/Cntr=0.3,0.1

Type RM Length L Ch R = 1 ,65741   ,871,871,871
BEGIN DESCRIPTION:
SULPHUR CREEK 63.0
END DESCRIPTION:
XS GIS Cut Line= 3
      2268604.36     13382064.59      2268221.19     13381834.69
      2266752.49     13381457.93
#Sta/Elev= 30
  3524.8  214.69  3572.5  213.83    3833  209.83  3945.6  208.99    4049  208.73
  4250.3  207.29    4406  202.14  4536.3  197.15  4547.3  197.05  4705.3  190.31
  4741.3  190.86  4832.7   191.7    4894  188.46  4944.7  191.28  4966.3  186.26
  4990.7  184.27  4994.3   177.9    4997   177.4  5000.3   177.9  5007.6  178.26
  5017.9  186.21  5048.9   185.6  5072.2   187.5  5090.2  196.74  5100.5  205.31
  5107.8  208.54    5167  212.82  5235.3  216.23  5393.2  217.08  5487.9  220.91
#Mann= 12 ,-1 , 0
  3524.8      .1       0  3572.5     .05       0    3833     .08       0
  3945.6     .05       0    4049      .1       0  4250.3     .05       0
    4406      .1       0  4536.3     .16       0  4741.3     .12       0
  4994.3     .07       0  5000.3     .12       0    5167      .1       0
Bank Sta=4547.3,5090.2
XS Rating Curve= 0 ,0
Exp/Cntr=0.3,0.1

Type RM Length L Ch R = 1 ,64870   ,1005,1005,1005
BEGIN DESCRIPTION:
SULPHUR CREEK 62.0
END DESCRIPTION:
XS GIS Cut Line= 3
      2269019.52     13381202.43      2268170.09     13381132.18
       2267065.2      13380787.3
#Sta/Elev= 30
  3632.6  216.57  3953.6  208.37  4055.8  205.89    4096  202.67  4390.2  205.95
  4488.6   205.1  4692.6  197.38  4728.4  196.08  4792.3  193.31  4824.8  188.89
  4850.4  191.48  4922.2  187.62  4937.9  184.51  4979.8  183.25  4997.7  176.72
  5000.5  176.22  5003.7  176.72  5011.2  182.02  5019.7   184.7  5052.2  183.73
    5090  187.32  5095.2  191.69  5105.5  192.06  5110.8  195.98    5116  199.89
  5163.6   205.4  5257.7  213.45  5391.9  219.51  5490.4  223.13  5642.4   224.5
#Mann= 10 ,-1 , 0
  3632.6     .05       0  3953.6      .1       0  4390.2     .08       0
  4488.6     .05       0  4692.6     .16       0  4850.4     .12       0
  4997.7     .07       0  5003.7     .12       0  5163.6      .1       0
  5391.9     .05       0
Bank Sta=4728.4,5110.8
XS Rating Curve= 0 ,0
Exp/Cntr=0.3,0.1

Type RM Length L Ch R = 1 ,63865   ,761,761,761
BEGIN DESCRIPTION:
Mapping XS 5fbf87fe
END DESCRIPTION:
XS GIS Cut Line= 4
      2268946.71     13380233.92      2268612.78     13380112.49
      2267185.99     13380152.96      2266842.34     13380415.76
#Sta/Elev= 30
  4163.5  211.87  4541.9  209.05  4640.3  204.76    4714  200.58    4794  190.83
    4814   187.9    4824  184.58    4837  189.48    4924  193.81  4944.1  191.96
  4954.1  187.72  4964.1  186.72  4991.1  175.78  4993.8  175.28  4997.1  175.78
  5004.1  176.46  5014.1  181.31  5034.1  181.27  5044.1  183.99  5074.1  185.08
  5094.1  187.68  5114.1  187.33  5152.1  191.19  5244.2  193.92  5307.8  196.89
  5514.3  204.86  5875.2  207.94  6005.4  210.63  6283.8  220.41  6378.8   221.2
#Mann= 9 ,-1 , 0
  4163.5     .08       0  4541.9     .05       0  4640.3      .1       0
    4837     .12       0  4991.1     .07       0  4997.1     .12       0
  5152.1     .16       0  5307.8      .1       0  5875.2     .05       0
Bank Sta=4924,5244.2
XS Rating Curve= 0 ,0
Exp/Cntr=0.3,0.1

Type RM Length L Ch R = 1 ,63104   ,1018,1018,1018
BEGIN DESCRIPTION:
SULPHUR CREEK 60.0
END DESCRIPTION:
XS GIS Cut Line= 4
      2269270.49     13379626.76      2268450.87     13379353.56
      2267155.63     13379474.99      2266711.59      13379838.3
#Sta/Elev= 30
  3816.2  214.75  4093.2  209.38  4302.4  201.78  4464.7  200.35  4578.1  196.62
  4715.6  195.21  4814.5  197.11  4884.2  198.94  4913.5  197.23  4944.5  196.36
 4963.64  191.96  4964.5  194.16  4969.6  191.84  4981.5  184.64  4986.5  183.58
  4994.7  174.95  5001.7  173.52  5004.5  173.02  5007.7  173.52  5014.8  180.08
  5054.9  180.89  5090.3  186.14  5125.2  186.85    5194  192.24  5230.5  194.12
  5316.1  202.02  5585.3  201.92  5943.7  203.02  6059.4  203.59  6554.8  210.85
#Mann= 11 ,-1 , 0
  3816.2     .05       0  4464.7      .1       0  4715.6     .05       0
  4814.5     .08       0  4913.5     .12       0  5001.7     .07       0
  5007.7     .12       0  5230.5      .1       0  5585.3     .05       0
  5943.7      .1       0  6059.4     .05       0
Bank Sta=4969.6,5194
XS Rating Curve= 0 ,0
Exp/Cntr=0.3,0.1

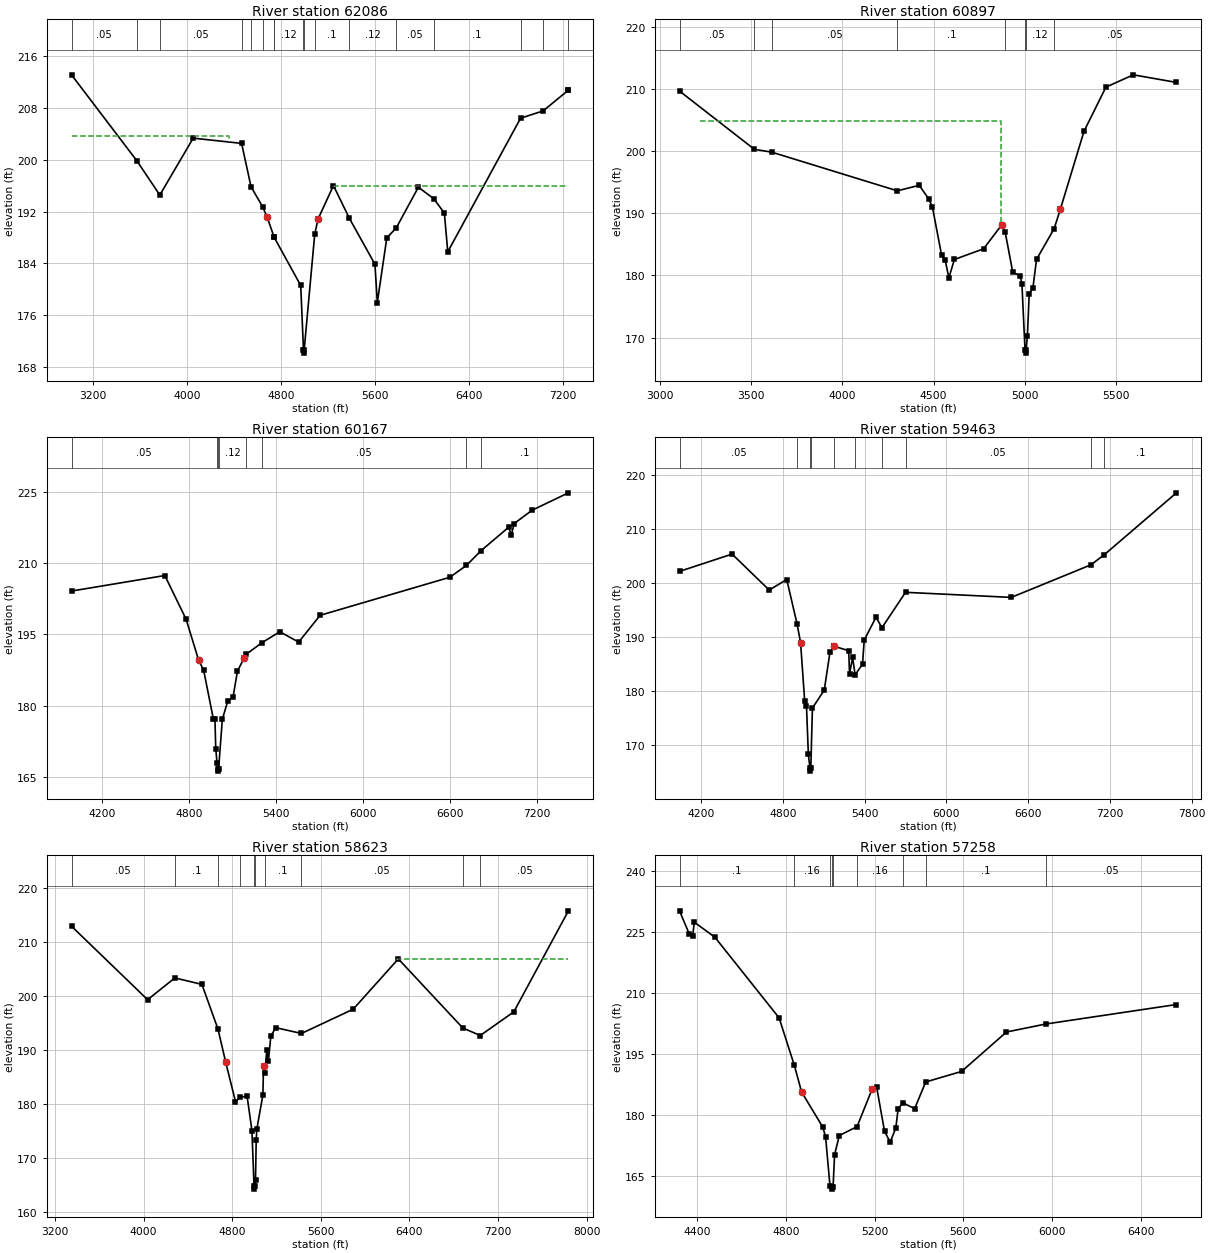
Type RM Length L Ch R = 1 ,62086   ,1189,1189,1189
BEGIN DESCRIPTION:
SULPHUR CREEK 59.0
END DESCRIPTION:
XS GIS Cut Line= 4
      2269260.37     13379323.19      2268167.54     13378827.37
      2266437.18     13378604.75      2265263.39     13378088.69
#Sta/Elev= 30
    3020  213.12  3575.9  199.84  3771.1  194.55  4055.1  203.34  4466.9  202.53
  4547.2  195.82  4645.9  192.74  4683.7  191.15  4743.9  188.03  4744.5     188
  4969.8  180.58  4993.2  170.63    4996  170.13  4999.2  170.63    5089  188.51
  5117.2  190.85  5248.3  196.01  5383.1  190.97  5601.2  183.86  5621.3  177.95
    5702  187.93  5782.2  189.47  5970.7  195.76  6102.8  193.96  6191.7  191.75
  6220.6  185.78    6840  206.42    7032  207.55  7245.4  210.73  7246.9  210.73
#Mann= 17 ,-1 , 0
    3020     .05       0  3575.9      .1       0  3771.1     .05       0
  4466.9     .08       0  4547.2     .16       0  4645.9     .12       0
  4743.9     .16       0  4744.5     .12       0  4993.2     .07       0
  4999.2     .12       0    5089      .1       0  5383.1     .12       0
  5782.2     .05       0  6102.8      .1       0    6840     .16       0
    7032      .1       0  7245.4     .05       0
#XS Ineff= 2 , 0
         4357.85  203.64 5256.01          196.01
Permanent Ineff=
       T       T
Bank Sta=4683.7,5117.2
XS Rating Curve= 0 ,0
Exp/Cntr=0.3,0.1

Type RM Length L Ch R = 1 ,60897   ,730,730,730
BEGIN DESCRIPTION:
SULPHUR CREEK 58.0
END DESCRIPTION:
XS GIS Cut Line= 2
      2269462.74     13377602.97      2266741.72     13377704.12
#Sta/Elev= 30
  3107.7  209.68  3517.9   200.3  3612.5  199.85  4301.5  193.62  4421.2  194.51
  4473.7  192.31  4493.7  190.99  4543.7  183.28  4563.7  182.45  4583.7   179.6
  4613.8  182.57  4773.9  184.29  4873.9  188.16    4892  187.01    4934  180.49
    4974  179.98    4984  178.63    5001     168  5003.8   167.5    5007     168
    5014  170.29    5024  177.06  5044.1  177.97  5064.1  182.59  5160.6  187.53
  5194.2  190.62  5324.2   203.2  5444.3  210.31  5594.4  212.29  5830.6  211.07
#Mann= 8 ,-1 , 0
  3107.7     .05       0  3517.9     .08       0  3612.5     .05       0
  4301.5      .1       0    4892     .12       0    5001     .07       0
    5007     .12       0  5160.6     .05       0
#XS Ineff= 1 ,-1
 3219.89 4869.89  204.83
Permanent Ineff=
       T
Bank Sta=4873.9,5194.2
XS Rating Curve= 0 ,0
Exp/Cntr=0.3,0.1

Type RM Length L Ch R = 1 ,60167   ,704,704,704
BEGIN DESCRIPTION:
SULPHUR CREEK 57.0
END DESCRIPTION:
XS GIS Cut Line= 4
      2268952.76     13377317.92      2268392.82     13377278.85
      2266491.78     13376367.39       2265751.2     13376510.31
#Sta/Elev= 30
  3992.1  204.11  4635.1  207.38  4782.1  198.14  4867.2  189.64  4902.8  187.41
  4969.4  177.19  4980.4  177.13    4986  170.94  4994.5     168  4999.7   166.7
  5002.4   166.2  5005.7   166.7  5031.3  177.13  5069.2  180.98  5104.8  181.76
  5135.7  187.27  5180.1  189.93  5197.2  190.83  5304.9  193.25  5427.5  195.54
  5557.2  193.36  5704.9     199  6599.6  207.02  6713.6  209.52  6814.2  212.62
  7004.4  217.55  7022.2  215.94  7042.6  218.33    7165  221.12  7415.9  224.79
#Mann= 8 ,-1 , 0
  3992.1     .05       0  4994.5     .12       0  4999.7     .07       0
  5005.7     .12       0  5197.2      .1       0  5304.9     .05       0
  6713.6     .08       0  6814.2      .1       0
Bank Sta=4867.2,5180.1
XS Rating Curve= 0 ,0
Exp/Cntr=0.3,0.1

Type RM Length L Ch R = 1 ,59463   ,840,840,840
BEGIN DESCRIPTION:
SULPHUR CREEK 56.0
END DESCRIPTION:
XS GIS Cut Line= 3
      2269147.99     13377031.43      2267598.55     13375976.77
       2265827.7     13375898.64
#Sta/Elev= 30
  4041.4   202.2  4427.2   205.4  4699.6  198.75  4828.3   200.7  4904.5  192.45
    4930  188.99  4959.9  178.29  4973.2  177.36  4986.9  168.41  4998.9  165.76
  5001.6  165.26  5004.9  165.76  5016.8  176.93  5103.6  180.24  5145.5  187.22
  5175.4  188.44  5177.6  188.34  5283.2  187.53  5289.2  183.25  5311.9  186.29
    5330  183.07  5384.5  185.03    5397  189.49  5483.7  193.73    5527  191.78
  5700.1  198.33  6476.5  197.39  7061.2  203.42  7159.4  205.29  7688.3  216.73
#Mann= 10 ,-1 , 0
  4041.4     .05       0  4904.5     .12       0  4998.9     .07       0
  5004.9     .12       0  5177.6      .1       0    5330     .12       0
    5527      .1       0  5700.1     .05       0  7061.2     .08       0
  7159.4      .1       0
Bank Sta=4930,5175.4
XS Rating Curve= 0 ,0
Exp/Cntr=0.3,0.1

Type RM Length L Ch R = 1 ,58623   ,1365,1365,1365
BEGIN DESCRIPTION:
SULPHUR CREEK 55.0
END DESCRIPTION:
XS GIS Cut Line= 5
      2269694.91      13377239.8      2269082.92     13376315.31
       2268692.3     13375573.12      2268041.26     13374856.98
      2266505.79     13374531.67
#Sta/Elev= 30
    3350  212.96  4036.7  199.36    4283  203.39    4527  202.19  4672.1  193.91
  4741.7  187.78  4829.9  180.51  4872.5  181.26  4934.4  181.55  4978.4  175.14
  4997.5  164.79  5000.2  164.29  5003.5  164.79  5010.7  166.05  5016.9  173.33
  5022.5  175.39  5077.3  181.72    5083     187  5096.6  185.75  5112.4  190.08
    5127  188.02  5149.1  192.61  5193.1  194.18  5425.3  193.11  5892.6   197.6
  6299.5  206.91  6881.6  194.12    7039  192.73  7342.2  197.11  7834.8  215.81
#Mann= 10 ,-1 , 0
    3350     .05       0    4283      .1       0  4672.1     .16       0
  4872.5     .12       0  4997.5     .07       0  5003.5     .12       0
  5096.6      .1       0  5425.3     .05       0  6881.6      .1       0
    7039     .05       0
#XS Ineff= 2 , 0
                         6288.54          206.92
Permanent Ineff=
       T       T
Bank Sta=4741.7,5083
XS Rating Curve= 0 ,0
Exp/Cntr=0.3,0.1

Type RM Length L Ch R = 1 ,57258   ,1005,1005,1005
BEGIN DESCRIPTION:
Mapping XS ddbfaebf
END DESCRIPTION:
XS GIS Cut Line= 3
      2270268.73     13375178.68      2269948.74     13375315.81
      2268165.87     13374675.81
#Sta/Elev= 30
  4319.4  230.19    4364  224.41  4379.3  224.05  4385.8  227.41    4479   223.7
  4768.8  203.86  4837.6  192.17  4870.5  185.61  4966.1  176.97  4978.6  174.56
  4998.5  162.49  5006.4  162.23  5009.1  161.73  5012.4  162.23  5019.2  170.19
  5040.5  174.92  5120.6   177.1  5189.2  186.41  5208.6  186.96  5244.6  175.96
  5270.1  173.29  5295.5  176.77  5306.1  181.52  5327.1  182.96  5380.5  181.53
  5430.4  188.09  5592.2  190.68  5794.9  200.38  5971.5  202.34  6561.8  207.14
#Mann= 9 ,-1 , 0
  4319.4      .1       0  4837.6     .16       0  4998.5     .12       0
  5006.4     .07       0  5012.4     .12       0  5120.6     .16       0
  5327.1     .12       0  5430.4      .1       0  5971.5     .05       0
Bank Sta=4870.5,5189.2
XS Rating Curve= 0 ,0
Exp/Cntr=0.3,0.1

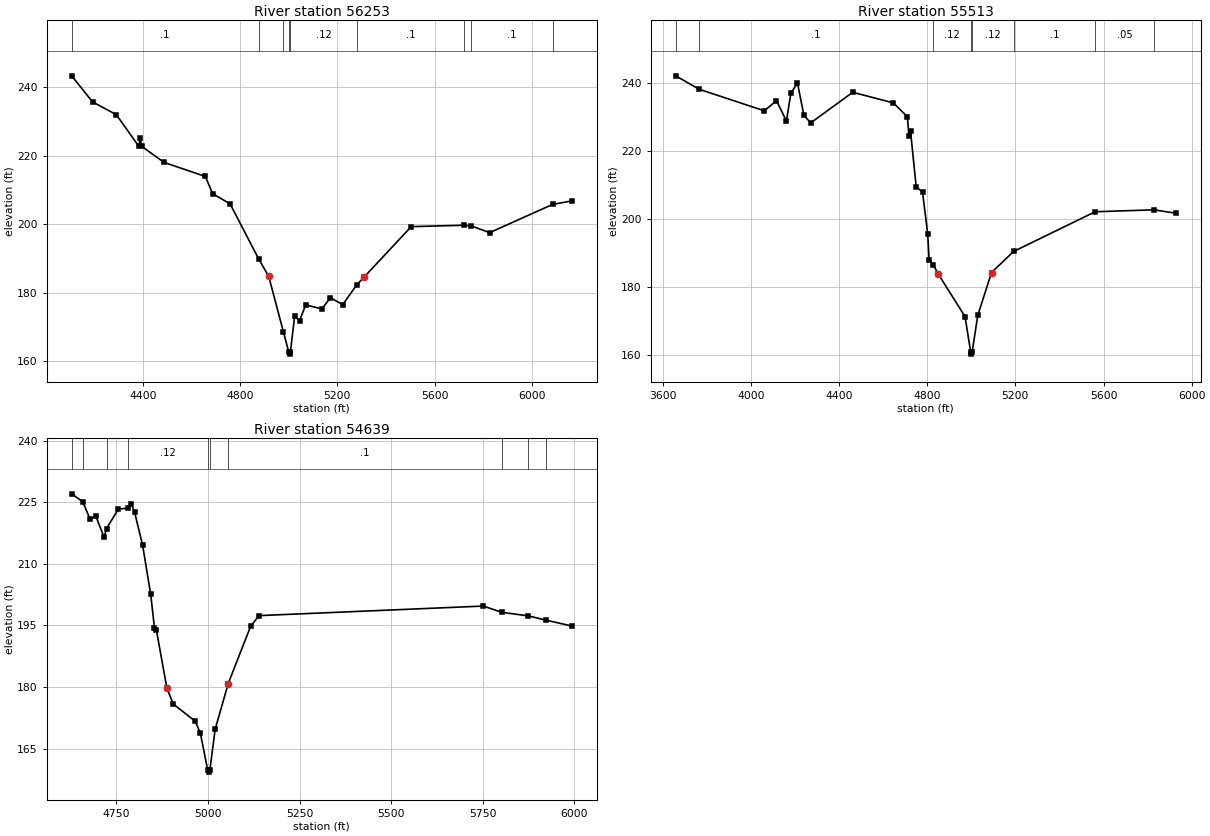
Type RM Length L Ch R = 1 ,56253   ,740,740,740
BEGIN DESCRIPTION:
SULPHUR CREEK 53.0
END DESCRIPTION:
XS GIS Cut Line= 3
      2270070.63     13374447.24      2269598.27     13374233.91
      2268091.22     13374538.36
#Sta/Elev= 30
  4107.8   243.4  4193.5  235.78  4291.5  232.04    4384  222.77  4389.5  225.13
  4396.3  222.74  4487.4  218.08  4657.3  213.97  4687.9   208.9  4759.3  205.95
  4877.4  189.75  4918.1  184.75  4978.3  168.55  5001.1  162.49  5003.9  161.99
  5007.1  162.49  5024.7  173.05  5044.9  171.79  5070.3  176.38  5136.8  175.22
  5171.9  178.49  5222.6  176.47  5280.8  182.32  5310.2  184.51    5504  199.28
    5721  199.69  5750.7  199.51  5826.6  197.53  6085.8  205.79  6163.6   206.8
#Mann= 9 ,-1 , 0
  4107.8      .1       0  4877.4     .16       0  4978.3     .12       0
  5001.1     .07       0  5007.1     .12       0  5280.8      .1       0
    5721     .05       0  5750.7      .1       0  6085.8     .05       0
Bank Sta=4918.1,5310.2
XS Rating Curve= 0 ,0
Exp/Cntr=0.3,0.1

Type RM Length L Ch R = 1 ,55513   ,874,874,874
BEGIN DESCRIPTION:
SULPHUR CREEK 52.0
END DESCRIPTION:
XS GIS Cut Line= 4
      2269968.31     13373776.25      2269135.01     13373841.35
      2268926.67     13373750.21      2267821.48     13374231.29
#Sta/Elev= 30
    3659  242.02  3764.1   238.1  4060.8  231.74  4116.1  234.73  4161.1  228.73
  4181.2  236.86  4211.3  239.93  4240.4  230.42  4271.5   228.2    4462  237.18
  4646.7  234.06  4710.2  229.98  4716.9  224.28  4724.3  225.75  4749.9  209.47
  4778.8  207.83  4802.2  195.61  4808.4  188.03  4827.5  186.53  4849.1  183.86
  4971.7  171.26  4997.6  160.73  5000.3  160.23  5003.6  160.73  5029.5  171.62
  5091.9  184.21    5192   190.4  5561.9  202.07  5828.6  202.64  5927.6  201.64
#Mann= 8 ,-1 , 0
    3659     .05       0  3764.1      .1       0  4827.5     .12       0
  4997.6     .07       0  5003.6     .12       0    5192      .1       0
  5561.9     .05       0  5828.6      .1       0
Bank Sta=4849.1,5091.9
XS Rating Curve= 0 ,0
Exp/Cntr=0.3,0.1

Type RM Length L Ch R = 1 ,54639   ,1089,1089,1089
BEGIN DESCRIPTION:
SULPHUR CREEK 51.0
END DESCRIPTION:
XS GIS Cut Line= 3
      2268633.42      13372924.7       2268067.8      13373187.6
      2267629.62     13373785.11
#Sta/Elev= 30
    4628  227.11  4658.4  225.16  4678.4  220.88  4693.7  221.76  4716.6  216.48
  4723.1  218.64  4755.6   223.4  4783.1  223.62  4790.8  224.63  4799.7  222.67
  4821.8  214.53  4843.8  202.58  4853.9   194.5  4859.4  193.85  4887.9  179.76
  4905.2  175.85  4965.1  171.67  4979.4  168.71  4999.3  159.74    5002  159.24
  5005.3  159.74  5019.7  169.69  5055.4  180.85  5116.7  194.83  5139.6  197.41
  5751.9  199.74  5802.3  198.21  5874.7  197.34  5922.1  196.32  5992.7  194.88
#Mann= 10 ,-1 , 0
    4628     .05       0  4658.4     .08       0  4723.1      .1       0
  4783.1     .12       0  4999.3     .07       0  5005.3     .12       0
  5055.4      .1       0  5802.3     .08       0  5874.7      .1       0
  5922.1     .08       0
Bank Sta=4887.9,5055.4
XS Rating Curve= 0 ,0
Exp/Cntr=0.3,0.1