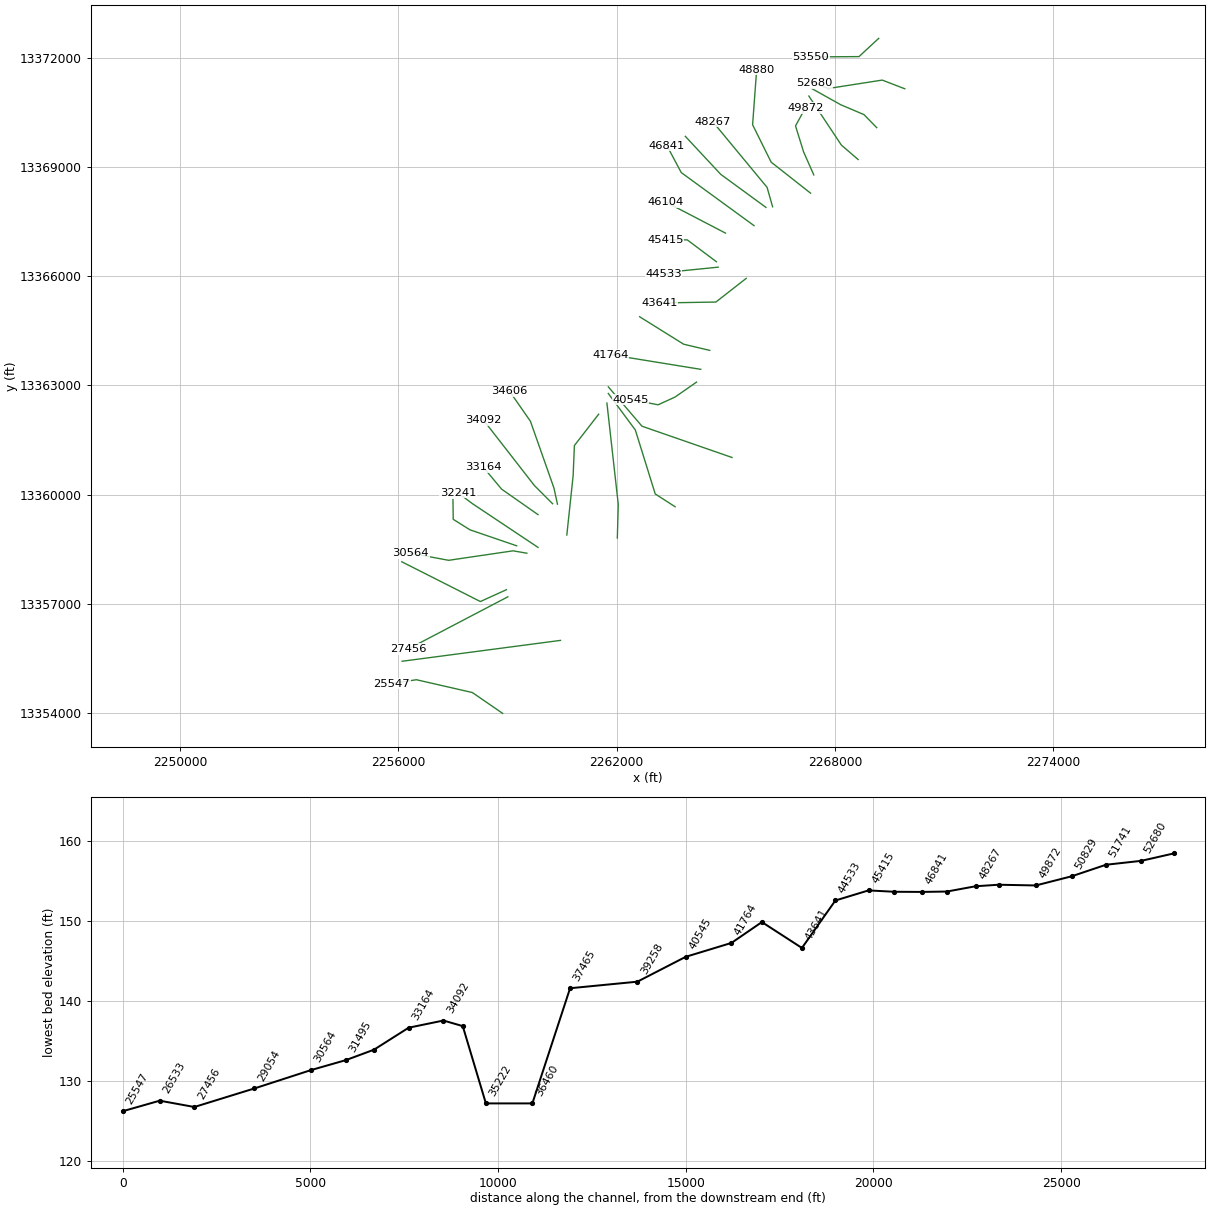
HEC-RAS study SULPHUR CREEK.prj: SULPHUR CREEK Base Level Engineering

--- SULPHUR CREEK.g01 (geometry) --- (continued)

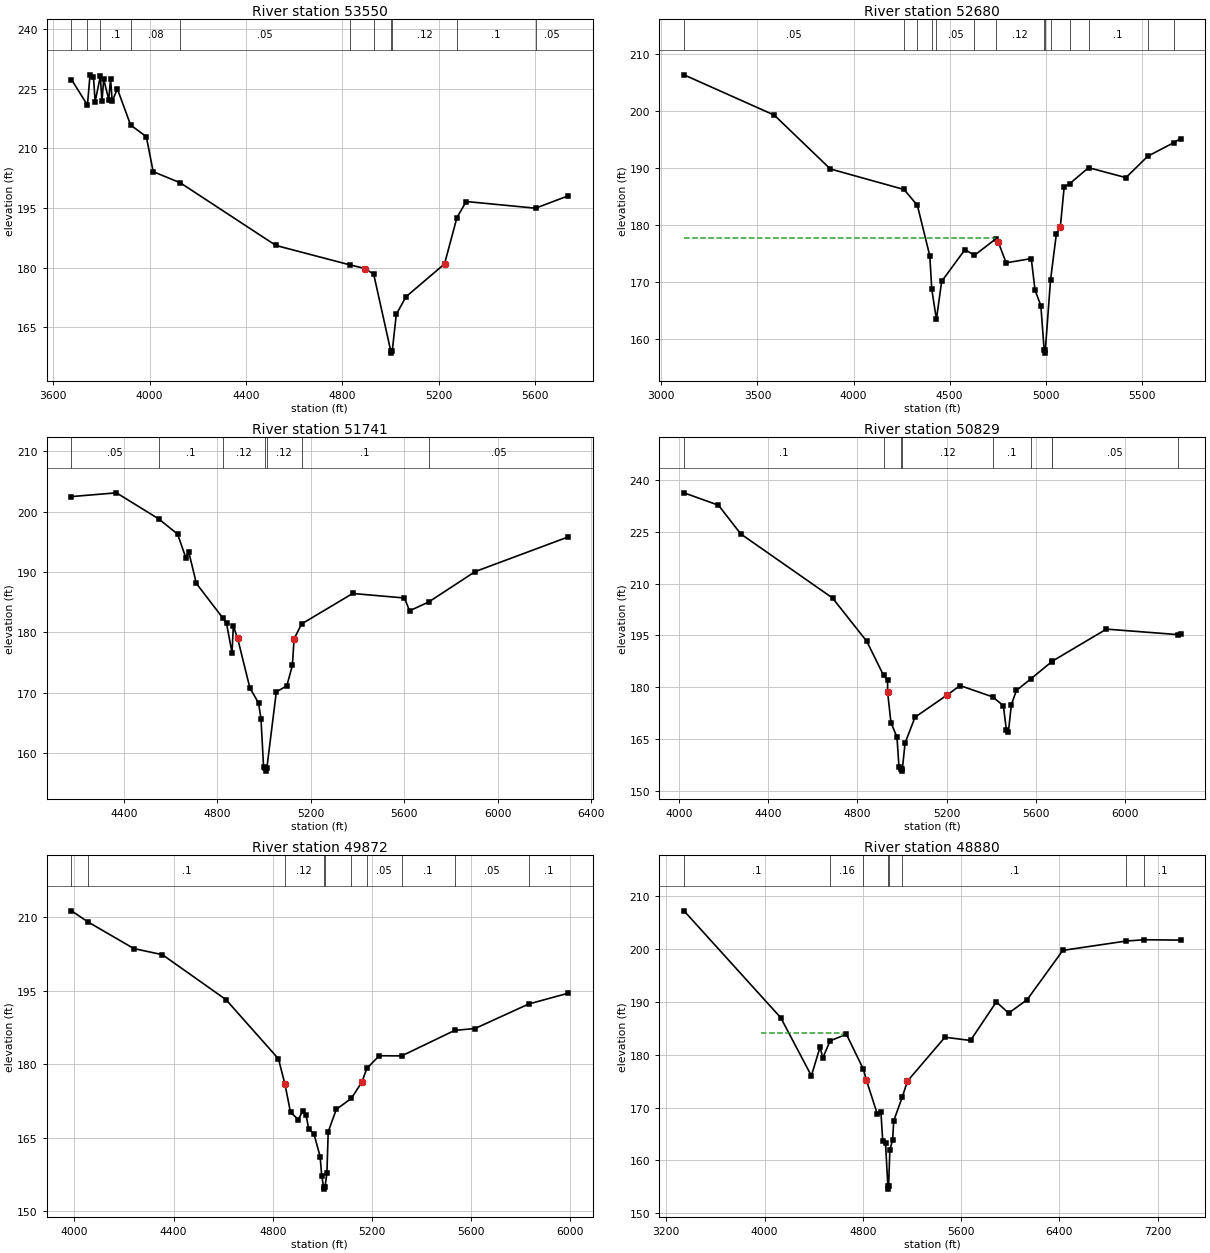
Type RM Length L Ch R = 1 ,53550   ,870,870,870
BEGIN DESCRIPTION:
SULPHUR CREEK 50.0
END DESCRIPTION:
XS GIS Cut Line= 3
      2269199.14     13372534.29      2268657.37     13372032.36
      2267334.84      13372024.4
#Sta/Elev= 30
  3676.1  227.32  3742.2   220.9  3753.1  228.51  3767.3  228.06  3774.1  221.73
  3795.7  228.11  3802.5  221.86  3809.8  227.38  3830.8  222.28  3838.2  227.54
    3845  221.86  3866.5  224.97  3921.5  215.88  3986.7  212.95  4015.1  204.15
  4127.5  201.35  4524.3  185.59  4832.2  180.69  4894.3  179.78  4930.4  178.37
  5001.3     159  5004.1   158.5  5007.3     159  5024.3  168.27  5064.3  172.67
  5224.3  180.94  5275.8  192.59  5314.3  196.64  5602.1  194.96  5737.2  198.06
#Mann= 11 ,-1 , 0
  3676.1      .1       0  3742.2     .08       0  3795.7      .1       0
  3921.5     .08       0  4127.5     .05       0  4832.2      .1       0
  4930.4     .12       0  5001.3     .07       0  5007.3     .12       0
  5275.8      .1       0  5602.1     .05       0
Bank Sta=4894.3,5224.3
XS Rating Curve= 0 ,0
Exp/Cntr=0.3,0.1

Type RM Length L Ch R = 1 ,52680   ,939,939,939
BEGIN DESCRIPTION:
SULPHUR CREEK 49.0
END DESCRIPTION:
XS GIS Cut Line= 4
      2269916.17     13371148.01      2269294.74     13371387.02
      2267812.85     13371155.98      2267422.57     13371307.31
#Sta/Elev= 30
  3117.7   206.4  3587.5  199.33  3879.3  189.88  4262.8  186.28  4332.2   183.5
    4397  174.61  4406.9  168.83  4431.2  163.49  4458.6  170.16    4580  175.74
  4629.2  174.73    4742  177.66  4752.1  177.14  4794.2  173.41  4924.9  174.16
  4944.4  168.63  4974.8  165.89    4992  158.07  4994.7  157.57    4998  158.07
    5025  170.37  5055.7  178.55    5076  179.66  5096.2  186.75    5124  187.27
    5223  190.11  5417.5  188.36  5531.2  192.12  5665.9  194.49  5701.9  195.21
#Mann= 14 ,-1 , 0
  3117.7     .05       0  4262.8      .1       0  4332.2     .05       0
  4406.9      .1       0  4431.2     .05       0  4629.2      .1       0
    4742     .12       0    4992     .07       0    4998     .12       0
    5025      .1       0    5124     .05       0    5223      .1       0
  5531.2     .05       0  5665.9      .1       0
#XS Ineff= 2 , 0
         4736.93  177.71
Permanent Ineff=
       T       T
Bank Sta=4752.1,5076
XS Rating Curve= 0 ,0
Exp/Cntr=0.3,0.1

Type RM Length L Ch R = 1 ,51741   ,912,912,912
BEGIN DESCRIPTION:
SULPHUR CREEK 48.0
END DESCRIPTION:
XS GIS Cut Line= 4
      2269143.34     13370080.44      2268792.81     13370438.94
      2268155.44     13370709.82      2267342.76     13371163.96
#Sta/Elev= 30
  4176.1  202.47  4368.4  203.09  4549.2  198.78  4630.2  196.26  4665.4  192.34
  4677.5  193.36  4710.4  188.11    4823  182.42  4839.5  181.51  4863.1  176.62
  4868.5  181.06  4886.8  179.05  4939.5  170.82  4976.4  168.35  4986.8  165.78
  4998.1  157.69    5006  157.58  5008.7  157.08    5012  157.58  5052.5  170.17
  5097.7   171.2  5121.3  174.58  5128.5  178.95  5160.9  181.42  5379.4  186.45
    5601   185.7  5622.7  183.58  5704.8  185.05  5903.6  190.07    6301  195.79
#Mann= 7 ,-1 , 0
  4176.1     .05       0  4549.2      .1       0    4823     .12       0
    5006     .07       0    5012     .12       0  5160.9      .1       0
  5704.8     .05       0
Bank Sta=4886.8,5128.5
XS Rating Curve= 0 ,0
Exp/Cntr=0.3,0.1

Type RM Length L Ch R = 1 ,50829   ,957,957,957
BEGIN DESCRIPTION:
SULPHUR CREEK 47.0
END DESCRIPTION:
XS GIS Cut Line= 3
      2268633.46     13369204.04      2268171.37     13369602.39
      2267279.04     13370948.85
#Sta/Elev= 30
  4023.6  236.36  4178.2  232.76    4278  224.44  4689.3  205.85  4842.7  193.29
  4917.7  183.45    4936  182.01 4936.08  178.55    4951  169.74  4978.1  165.46
    4987  156.91  4996.1  156.14  4998.9  155.64  5002.1  156.14  5014.2  163.74
  5058.9  171.28  5202.9  177.73  5260.8  180.46  5407.4  177.16  5454.8  174.61
  5468.4  167.55  5477.4     167  5490.8  174.95  5513.5  179.06  5579.6  182.48
  5670.8  187.34  5673.2  187.49  5916.6  196.83  6238.9  195.23    6249  195.27
#Mann= 9 ,-1 , 0
  4023.6      .1       0  4917.7     .12       0  4996.1     .07       0
  5002.1     .12       0  5407.4      .1       0  5579.6     .05       0
  5670.8      .1       0  5673.2     .05       0  6238.9      .1       0
Bank Sta=4936.08,5202.9
XS Rating Curve= 0 ,0
Exp/Cntr=0.3,0.1

Type RM Length L Ch R = 1 ,49872   ,992,992,992
BEGIN DESCRIPTION:
SULPHUR CREEK 46.0
END DESCRIPTION:
XS GIS Cut Line= 4
      2267414.49     13368781.79      2267135.64     13369411.18
      2266912.57     13370128.22      2267182.97     13370621.31
#Sta/Elev= 30
  3988.6  211.26  4053.5  209.04    4240  203.56  4355.1  202.31  4611.1  193.15
  4822.9  181.07  4849.2  175.84  4871.4  170.16  4902.9  168.69  4920.5  170.43
  4934.3  169.64  4944.8   166.7  4965.7   165.8  4990.8  161.13  4997.1  157.25
  5004.6  154.99  5007.3  154.49  5010.6  154.99  5018.1  157.75  5023.4  166.19
  5055.9  170.75  5116.5     173  5158.8   176.3  5179.2  179.12  5229.1   181.7
  5319.7  181.67  5533.2  186.87    5615  187.25  5831.9  192.26  5990.3  194.45
#Mann= 10 ,-1 , 0
  3988.6     .05       0  4053.5      .1       0  4849.2     .12       0
  5004.6     .07       0  5010.6     .12       0  5116.5      .1       0
  5179.2     .05       0  5319.7      .1       0  5533.2     .05       0
  5831.9      .1       0
Bank Sta=4849.2,5158.8
XS Rating Curve= 0 ,0
Exp/Cntr=0.3,0.1

Type RM Length L Ch R = 1 ,48880   ,613,613,613
BEGIN DESCRIPTION:
SULPHUR CREEK 45.0
END DESCRIPTION:
XS GIS Cut Line= 4
      2267326.83     13368279.86      2266243.33     13369132.33
      2265733.43     13370160.09       2265844.9     13371672.84
#Sta/Elev= 30
  3343.8  207.22  4131.6     187  4380.9  176.02  4451.4  181.44  4473.9  179.39
  4533.6  182.64    4666  183.87  4804.6  177.24    4828  175.26  4917.3   168.8
    4947  169.15  4961.9  163.65  4984.3  163.39  5003.6  155.08  5006.3  154.58
  5009.6  155.08  5019.8  161.96  5042.2   163.9  5051.2   167.5  5122.4  172.09
  5162.9  175.01  5468.1  183.31  5676.4   182.7  5886.6  189.99  5986.8  187.87
  6137.3  190.41    6428  199.74  6944.6  201.51  7090.8  201.75  7386.6  201.68
#Mann= 8 ,-1 , 0
  3343.8      .1       0  4533.6     .16       0  4804.6     .12       0
  5003.6     .07       0  5009.6     .12       0  5122.4      .1       0
  6944.6     .05       0  7090.8      .1       0
#XS Ineff= 1 ,-1
 3968.88 4633.66  184.02
Permanent Ineff=
       T
Bank Sta=4828,5162.9
XS Rating Curve= 0 ,0
Exp/Cntr=0.3,0.1

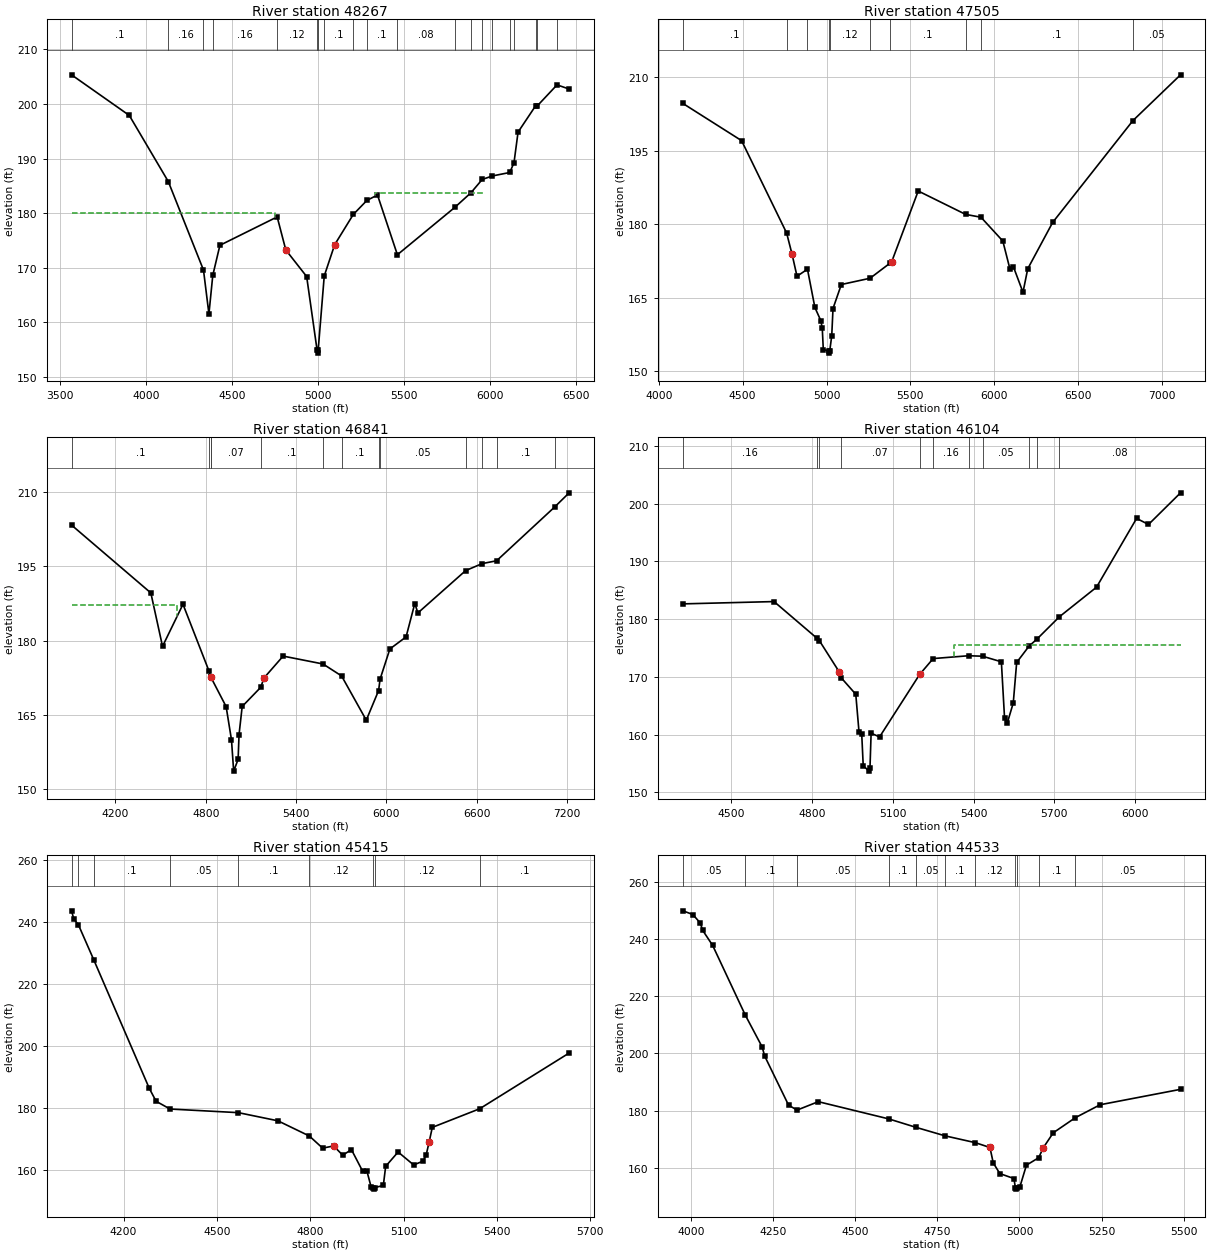
Type RM Length L Ch R = 1 ,48267   ,762,762,762
BEGIN DESCRIPTION:
SULPHUR CREEK 44.0
END DESCRIPTION:
XS GIS Cut Line= 3
      2266283.17     13367905.35      2266131.79     13368439.19
      2264642.33     13370239.28
#Sta/Elev= 30
  3567.5  205.34    3903  197.91  4129.7   185.8  4334.2  169.59  4365.7  161.57
  4388.1  168.62  4429.5  174.13  4762.3  179.33  4812.4  173.28  4933.6  168.41
  4994.4  154.89  4997.2  154.39  5000.4  154.89  5035.8  168.52  5096.4  174.24
  5204.4  179.77  5283.6  182.35  5345.2  183.34  5460.8   172.4    5794  181.06
  5888.2  183.75  5953.8  186.19  6013.3  186.83  6113.6  187.46  6138.3  189.24
  6161.9  194.85  6263.3  199.64  6273.5  199.65  6388.3   203.5  6458.8  202.74
#Mann= 20 ,-1 , 0
  3567.5      .1       0  4129.7     .16       0  4334.2      .1       0
  4388.1     .16       0  4762.3     .12       0  4994.4     .07       0
  5000.4     .12       0  5035.8      .1       0  5204.4     .08       0
  5283.6      .1       0  5460.8     .08       0    5794     .05       0
  5888.2     .08       0  5953.8     .05       0  6013.3     .08       0
  6113.6     .05       0  6138.3     .08       0  6263.3      .1       0
  6273.5     .05       0  6388.3      .1       0
#XS Ineff= 2 ,-1
  3567.5 4749.43  180.04 5328.85 5965.35  183.64
Permanent Ineff=
       T       T
Bank Sta=4812.4,5096.4
XS Rating Curve= 0 ,0
Exp/Cntr=0.3,0.1

Type RM Length L Ch R = 1 ,47505   ,664,664,664
BEGIN DESCRIPTION:
Mapping XS dbbbbae4
END DESCRIPTION:
XS GIS Cut Line= 3
      2266099.88     13367889.48      2264857.04     13368797.71
      2263885.07     13369841.38
#Sta/Elev= 30
  4144.3  204.64  4493.8  197.06  4762.2  178.23  4794.8  173.87  4824.1  169.41
  4886.5  170.84  4930.7  163.04  4966.2  160.34  4974.7  158.81  4980.9  154.42
  5013.4  154.23  5016.2  153.73  5019.4  154.23  5031.1  157.25  5038.7  162.83
  5088.3  167.72  5259.6     169  5379.5   172.1  5388.7  172.39  5546.5  186.79
    5829  182.02  5920.5  181.44  6050.7  176.59  6092.7  170.93  6114.2   171.3
  6170.9  166.14  6199.2  170.93  6347.7  180.38  6825.9  201.14  7109.8  210.48
#Mann= 10 ,-1 , 0
  4144.3      .1       0  4762.2     .16       0  4886.5     .12       0
  5013.4     .07       0  5019.4     .12       0  5259.6     .08       0
  5379.5      .1       0    5829     .08       0  5920.5      .1       0
  6825.9     .05       0
#XS Ineff= 1 ,-1
 5573.01  6869.6  185.74
Permanent Ineff=
       T
Bank Sta=4794.8,5388.7
XS Rating Curve= 0 ,0
Exp/Cntr=0.3,0.1

Type RM Length L Ch R = 1 ,46841   ,737,737,737
BEGIN DESCRIPTION:
SULPHUR CREEK 43.0
END DESCRIPTION:
XS GIS Cut Line= 3
      2265773.27     13367387.52      2263773.51     13368845.51
      2263383.12      13369578.5
#Sta/Elev= 30
  3908.7  203.26  4435.4  189.59    4513  178.82  4648.9   187.3  4821.7  173.85
  4834.6  172.63  4835.1  172.55  4935.5  166.68  4971.1  159.98  4985.5  153.68
  5015.1  156.05  5021.3  161.06  5042.2  166.71  5165.5  170.57  5186.6  172.44
  5314.1  176.86  5579.1  175.27  5702.4  172.86  5866.4  163.95  5948.3  169.92
    5958   172.2  6023.2   178.3  6130.8  180.73  6188.6  187.45  6209.4  185.56
  6526.1  194.08  6636.2   195.5  6732.2  196.07  7117.6   206.9    7214  209.76
#Mann= 13 ,-1 , 0
  3908.7      .1       0  4821.7     .16       0  4834.6     .12       0
  4835.1     .07       0  5165.5      .1       0  5579.1     .12       0
  5702.4      .1       0  5948.3     .08       0    5958     .05       0
  6526.1      .1       0  6636.2     .05       0  6732.2      .1       0
  7117.6     .05       0
#XS Ineff= 2 ,-1
  3908.7 4606.82  187.17 5321.78 6125.18  176.73
Permanent Ineff=
       T       T
Bank Sta=4835.1,5186.6
XS Rating Curve= 0 ,0
Exp/Cntr=0.3,0.1

Type RM Length L Ch R = 1 ,46104   ,689,689,689
BEGIN DESCRIPTION:
SULPHUR CREEK 42.0
END DESCRIPTION:
XS GIS Cut Line= 2
      2264988.14     13367182.86      2263347.48     13368037.04
#Sta/Elev= 30
  4319.7  182.66  4658.4  183.06  4818.9  176.67  4826.9  176.29  4901.5  170.82
  4907.1  169.91  4962.2  167.01  4974.1  160.56  4984.3  160.15  4989.9  154.63
  5011.8   153.7    5015   154.2  5019.2  160.27  5050.6  159.62  5199.6  170.44
  5249.9  173.19  5381.4  173.68  5433.3   173.6  5503.4  172.63  5515.2  162.91
  5525.5  162.05  5547.6   165.5  5560.3  172.52  5606.4  175.35  5635.4  176.55
  5718.9  180.42  5857.1  185.55  6006.1  197.46  6050.3  196.41  6169.4  201.89
#Mann= 11 ,-1 , 0
  4319.7     .16       0  4818.9      .1       0  4826.9     .16       0
  4907.1     .07       0  5199.6     .12       0  5249.9     .16       0
  5381.4     .08       0  5433.3     .05       0  5606.4     .08       0
  5635.4      .1       0  5718.9     .08       0
#XS Ineff= 2 , 0
                          5326.7          175.46
Permanent Ineff=
       T       T
Bank Sta=4901.5,5199.6
XS Rating Curve= 0 ,0
Exp/Cntr=0.3,0.1

Type RM Length L Ch R = 1 ,45415   ,882,882,882
BEGIN DESCRIPTION:
SULPHUR CREEK 41.0
END DESCRIPTION:
XS GIS Cut Line= 3
      2264737.71     13366396.86      2263937.72     13366996.85
      2263337.71     13366996.85
#Sta/Elev= 30
  4032.6  243.68  4039.9  241.02  4054.5  239.21  4104.6  227.74  4282.6  186.38
  4304.5  182.22  4349.3  179.72  4568.9  178.55  4696.1  175.92  4797.1  171.02
  4839.9   167.1  4875.3   167.8  4904.5  164.83  4932.6  166.61    4969  159.57
  4982.6  159.56  4996.1   154.5  5001.5  154.37  5004.2  153.87  5007.5  154.37
  5035.1  155.05  5042.6  161.22  5082.6  165.85  5132.6  161.68  5162.6  162.89
  5172.6  164.78  5182.6  169.17  5192.6   173.8    5345  179.81  5632.6  197.79
#Mann= 9 ,-1 , 0
  4032.6      .1       0  4054.5     .05       0  4104.6      .1       0
  4349.3     .05       0  4568.9      .1       0  4797.1     .12       0
  5001.5     .07       0  5007.5     .12       0    5345      .1       0
Bank Sta=4875.3,5182.6
XS Rating Curve= 0 ,0
Exp/Cntr=0.3,0.1

Type RM Length L Ch R = 1 ,44533   ,892,892,892
BEGIN DESCRIPTION:
SULPHUR CREEK 40.0
END DESCRIPTION:
XS GIS Cut Line= 3
      2264787.76     13366246.86      2263787.72     13366146.85
      2263287.75     13366046.86
#Sta/Elev= 30
  3975.4   249.8  4005.6  248.51  4028.2  245.54  4035.7  242.95  4065.9  237.72
  4165.7  213.28  4216.6  202.26  4224.2   199.1    4297  181.94  4322.8  180.21
  4387.5  183.15  4601.8  177.14  4686.3  174.14  4773.7  171.21  4865.4  168.84
  4910.1  167.15  4920.1  161.77  4940.2  158.04    4983  156.31  4987.6  153.11
  4990.4  152.61  4993.6  153.11  5000.8  153.25  5021.2  160.99  5058.4  163.57
  5072.2  167.02  5102.8  172.28  5170.2  177.57  5245.6  182.08  5490.3  187.46
#Mann= 11 ,-1 , 0
  3975.4     .05       0  4165.7      .1       0  4322.8     .05       0
  4601.8      .1       0  4686.3     .05       0  4773.7      .1       0
  4865.4     .12       0  4987.6     .07       0  4993.6     .12       0
  5058.4      .1       0  5170.2     .05       0
Bank Sta=4910.1,5072.2
XS Rating Curve= 0 ,0
Exp/Cntr=0.3,0.1

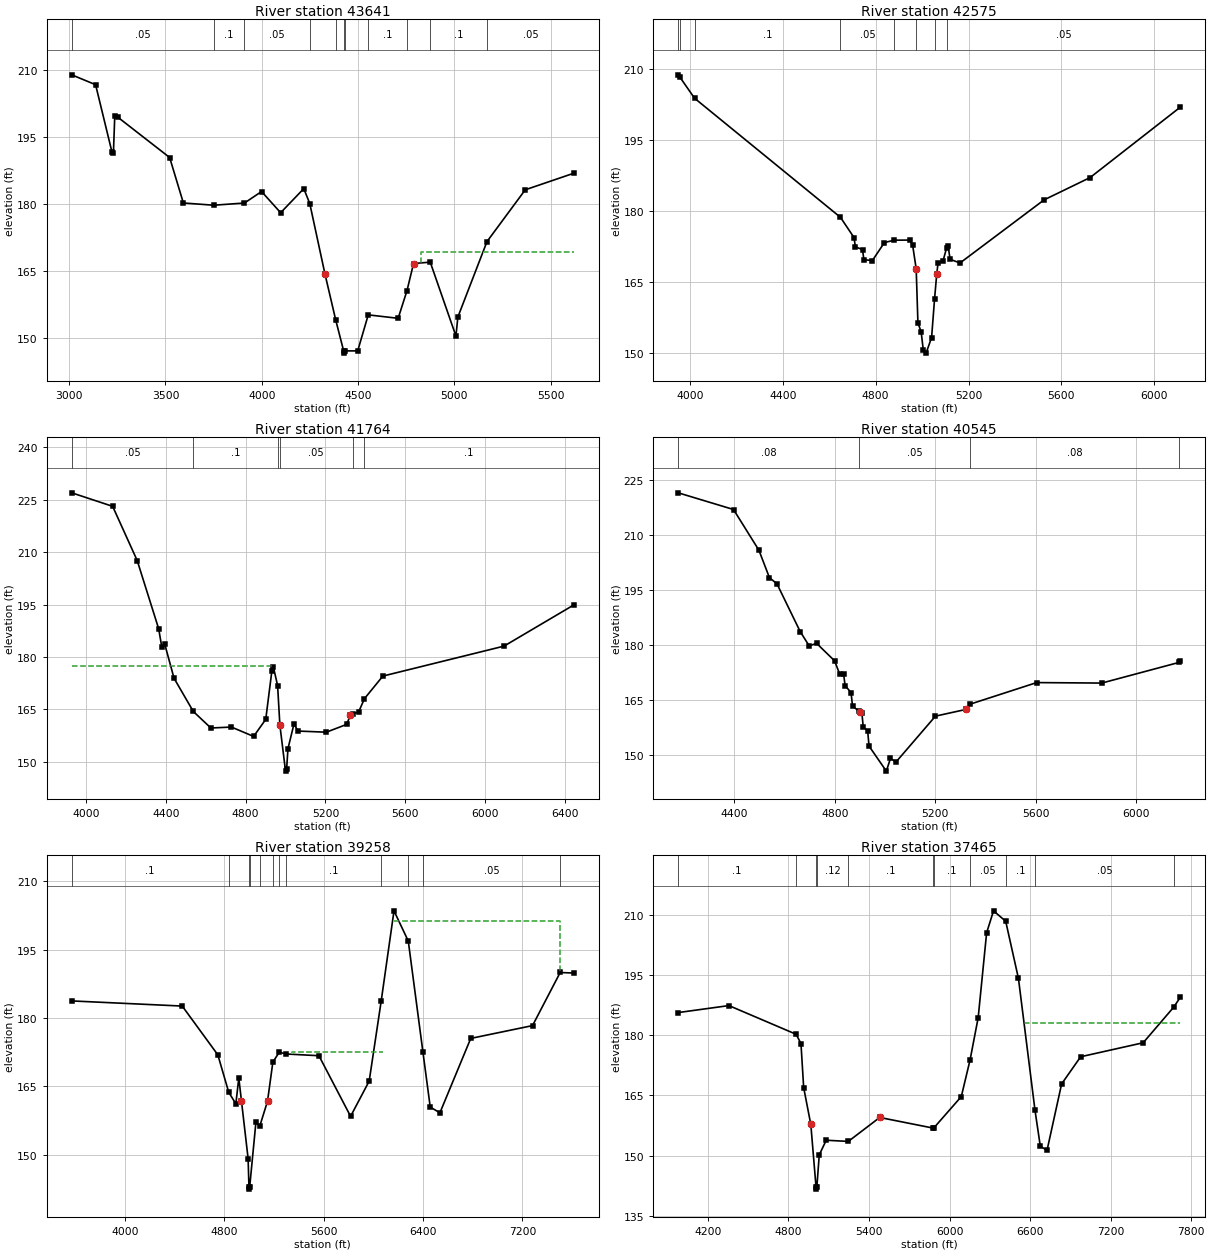
Type RM Length L Ch R = 1 ,43641   ,1066,1066,1066
BEGIN DESCRIPTION:
SULPHUR CREEK 39.0
END DESCRIPTION:
XS GIS Cut Line= 3
      2265558.28     13365939.52      2264724.93     13365288.46
      2263175.47     13365262.42
#Sta/Elev= 30
  3013.6  208.93  3137.3  206.72  3222.3  191.66    3230  191.55  3236.8   199.7
  3251.3   199.5  3521.9  190.43  3593.1  180.26  3750.7  179.76  3910.2  180.25
  3999.2  182.82  4098.3  178.08  4218.4  183.47  4249.6  180.12  4328.4  164.37
  4384.1  154.11  4425.4  147.17  4428.1  146.67  4431.4  147.17  4498.4  147.17
  4553.1  155.23  4708.4  154.46  4754.2  160.62  4788.4  166.72  4875.1  167.02
  5008.5  150.49  5018.5  154.74  5169.7  171.62  5368.5  183.21  5620.8  186.92
#Mann= 11 ,-1 , 0
  3013.6     .05       0  3750.7      .1       0  3910.2     .05       0
  4249.6      .1       0  4384.1     .07       0  4425.4     .07       0
  4431.4     .07       0  4553.1      .1       0  4754.2     .05       0
  4875.1      .1       0  5169.7     .05       0
#XS Ineff= 2 , 0
                         4825.57          169.26
Permanent Ineff=
       T       T
Bank Sta=4328.4,4788.4
XS Rating Curve= 0 ,0
Exp/Cntr=0.3,0.1

Type RM Length L Ch R = 1 ,42575   ,811,811,811
BEGIN DESCRIPTION:
SULPHUR CREEK 38.0
END DESCRIPTION:
XS GIS Cut Line= 3
      2264555.62     13363960.34      2263839.51      13364129.6
      2262628.55     13364884.82
#Sta/Elev= 30
  3949.4  208.82  3955.1  208.43  4019.8  203.86  4648.2  178.66  4706.7  174.37
  4712.6  172.39  4743.3  171.84  4749.2  169.68  4785.8  169.51  4837.7  173.32
  4880.7  173.82  4946.6  173.84  4959.2  172.77  4974.5  167.77    4982   156.3
  4995.8  154.45  5005.2  150.55  5017.1  149.91  5040.9   153.2  5053.6  161.35
    5063  166.63  5068.9  169.08  5090.1  169.42  5105.6  172.18  5111.6  172.66
  5120.8  169.77  5163.3  168.99  5525.5  182.35  5723.7  187.07  6112.4  201.98
#Mann= 8 ,-1 , 0
  3949.4      .1       0  3955.1     .05       0  4019.8      .1       0
  4648.2     .05       0  4880.7      .1       0  4974.5     .07       0
  5053.6      .1       0  5105.6     .05       0
Bank Sta=4974.5,5063
XS Rating Curve= 0 ,0
Exp/Cntr=0.3,0.1

Type RM Length L Ch R = 1 ,41764   ,1219,1219,1219
BEGIN DESCRIPTION:
SULPHUR CREEK 37.0
END DESCRIPTION:
XS GIS Cut Line= 2
      2264308.28      13363439.5      2261822.01     13363843.03
#Sta/Elev= 30
  3927.5     227  4132.6  223.13  4255.8   207.6  4363.7  188.02    4379  182.85
  4394.1  183.63  4440.6  173.89  4537.3  164.38  4625.4  159.65  4728.4  159.92
  4839.8  157.24  4900.6  162.12    4931  175.85  4938.5  177.23  4960.1  171.81
  4971.5  160.49  4999.9   147.3  5005.2  147.81  5012.1  153.73  5042.5  160.87
  5061.7  158.78  5204.6  158.45  5305.9  160.67 5325.57  163.28  5336.3  163.68
  5366.6  164.25  5395.8  168.05  5488.2  174.52  6096.1   183.1  6446.3   194.9
#Mann= 6 ,-1 , 0
  3927.5     .05       0  4537.3      .1       0  4960.1     .12       0
  4971.5     .05       0  5336.3     .05       0  5395.8      .1       0
#XS Ineff= 2 , 0
         4938.47  177.38
Permanent Ineff=
       T       T
Bank Sta=4971.5,5325.57
XS Rating Curve= 0 ,0
Exp/Cntr=0.3,0.1

Type RM Length L Ch R = 1 ,40545   ,1287,1287,1287
BEGIN DESCRIPTION:
Mapping XS 4c57cbce
END DESCRIPTION:
XS GIS Cut Line= 4
      2264192.46     13363088.23      2263602.78     13362677.69
      2263136.26     13362464.96      2262382.52     13362610.48
#Sta/Elev= 30
    4177  221.47  4397.1  216.92  4498.3   205.8  4540.2  198.31  4569.9  196.67
  4662.4  183.64  4698.2  179.74  4727.9  180.41  4799.4  175.65  4820.3  171.94
  4835.2  172.17  4841.3   168.9  4864.9  166.99    4871  163.29  4895.5  161.98
  4901.1  161.78  4908.1  161.47  4913.6  157.54  4931.1  156.63  4936.6  152.39
  5005.5  145.56    5022  149.04  5043.9  148.04  5201.1  160.56  5321.8  162.38
  5339.3  163.83  5604.1  169.71  5863.3  169.58  6170.6  175.21  6175.9  175.54
#Mann= 4 ,-1 , 0
    4177     .08       0  4895.5     .05       0  5339.3     .08       0
  6170.6     .05       0
Bank Sta=4901.1,5321.8
XS Rating Curve= 0 ,0
Exp/Cntr=0.3,0.1

Type RM Length L Ch R = 1 ,39258   ,1793,1793,1793
BEGIN DESCRIPTION:
SULPHUR CREEK 34.0
END DESCRIPTION:
XS GIS Cut Line= 3
      2265167.68     13361017.61      2262693.68       13361877.
       2261769.2     13362957.72
#Sta/Elev= 30
  3572.3  183.77  4461.5  182.64    4748  171.93  4835.6  163.72    4893  161.18
  4916.7  166.85  4937.9  161.86  4991.6  149.17  4998.4  142.95  5001.1  142.45
  5004.4  142.95  5054.3  157.09  5085.8  156.31 5147.73  161.73  5190.9  170.34
  5242.7  172.52    5296  172.12  5561.6  171.74  5816.5  158.43  5966.2  166.17
  6062.5  183.68  6165.9  203.55  6280.9  196.91  6398.6  172.57  6457.6  160.46
  6535.5  159.21  6783.6  175.54  7280.9  178.35  7503.5  190.01  7613.5  189.89
#Mann= 12 ,-1 , 0
  3572.3      .1       0  4835.6     .12       0  4998.4     .07       0
  5004.4     .12       0  5085.8     .16       0  5190.9      .1       0
  5242.7     .16       0    5296      .1       0  6062.5     .05       0
  6280.9      .1       0  6398.6     .05       0  7503.5      .1       0
#XS Ineff= 2 ,-1
 5347.95 6076.38  172.49 6168.32 7504.95  201.28
Permanent Ineff=
       T       T
Bank Sta=4937.9,5147.73
XS Rating Curve= 0 ,0
Exp/Cntr=0.3,0.1

Type RM Length L Ch R = 1 ,37465   ,1005,1005,1005
BEGIN DESCRIPTION:
SULPHUR CREEK 33.0
END DESCRIPTION:
XS GIS Cut Line= 4
      2263605.17     13359663.43      2263058.26     13360015.02
      2262511.39     13361772.83       2261769.2     13362775.43
#Sta/Elev= 30
  3980.1  185.66  4357.5   187.4  4858.3  180.24    4894  177.91    4914  166.97
  4967.3  157.75  5006.2  142.13    5009  141.63  5012.2  142.13  5030.2  150.18
  5081.9  153.82  5246.4  153.53  5480.5   159.5  5879.7  156.84  5880.9   156.8
  6087.9  164.71  6153.1  173.85  6213.6  184.41  6276.4  205.55  6327.8  211.03
  6418.4  208.43  6513.3  194.18  6636.5  161.31  6676.1  152.33  6726.2   151.3
  6834.7  167.86  6976.6  174.64  7442.1  178.13  7669.5  187.01  7718.6  189.47
#Mann= 11 ,-1 , 0
  3980.1      .1       0  4858.3     .12       0  5006.2     .07       0
  5012.2     .12       0  5246.4      .1       0  5879.7     .05       0
  5880.9      .1       0  6153.1     .05       0  6418.4      .1       0
  6636.5     .05       0  7669.5      .1       0
#XS Ineff= 2 , 0
                          6555.4          183.05
Permanent Ineff=
       T       T
Bank Sta=4967.3,5480.5
XS Rating Curve= 0 ,0
Exp/Cntr=0.3,0.1

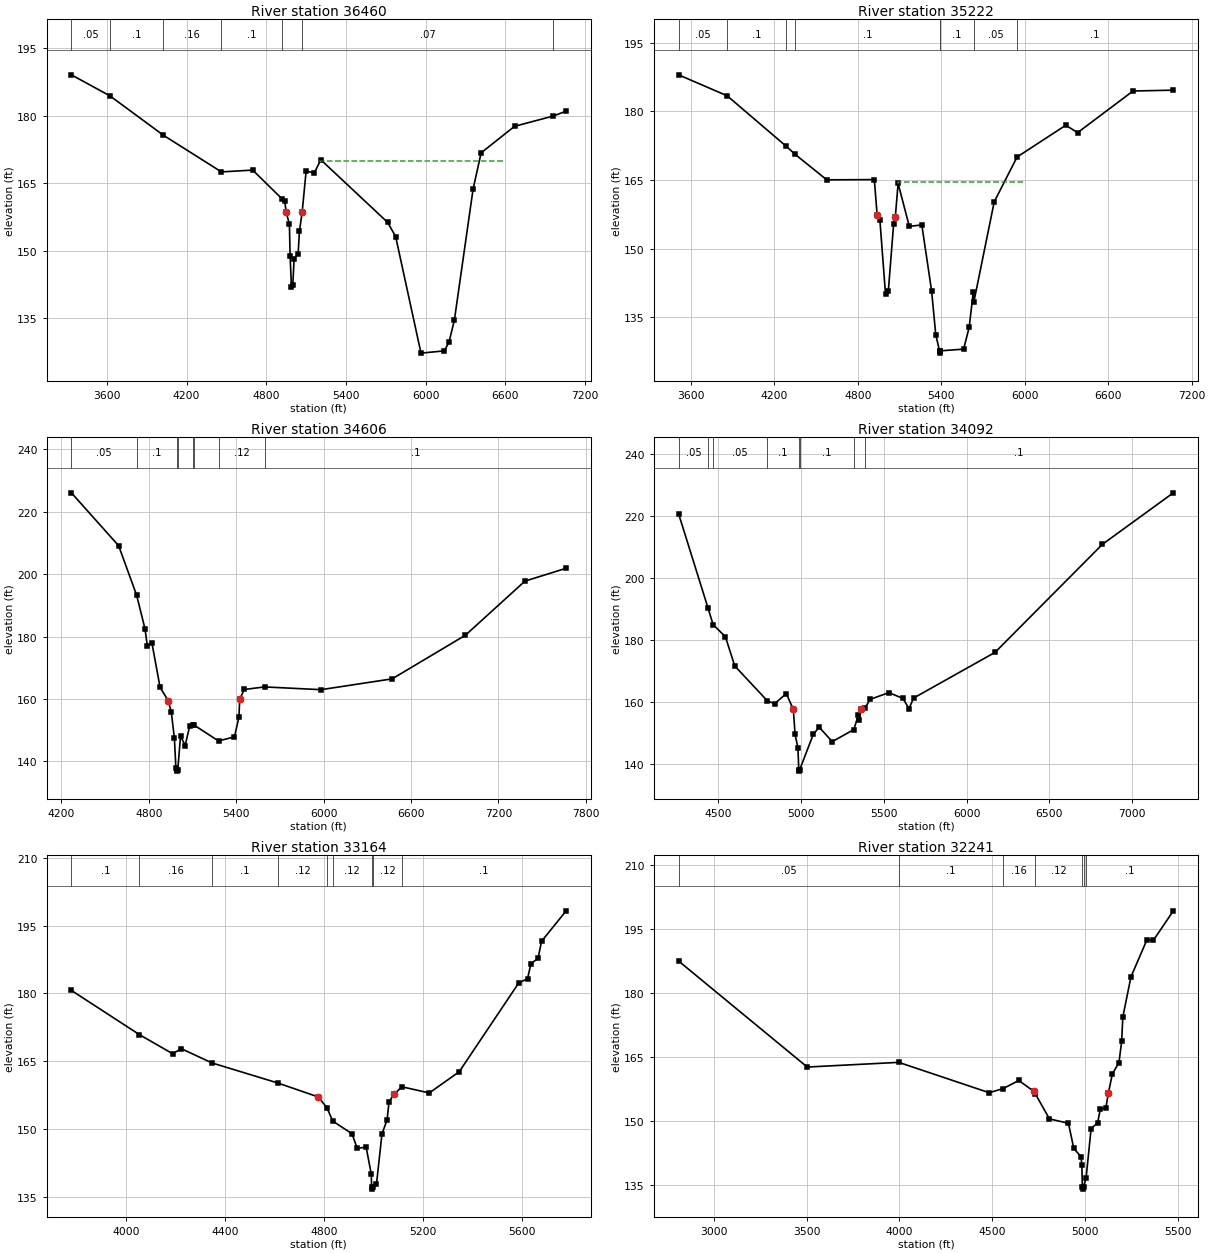
Type RM Length L Ch R = 1 ,36460   ,1238,1238,1238
BEGIN DESCRIPTION:
Mapping XS cb60f019
END DESCRIPTION:
XS GIS Cut Line= 3
      2262016.59     13358804.09      2262042.64     13359728.56
      2261730.31     13362513.47
#Sta/Elev= 30
  3332.2  189.09  3623.7  184.39  4024.2  175.68  4462.3  167.51  4698.1  167.91
  4919.5   161.5  4939.6  161.05  4949.6  158.55  4974.4  155.95  4979.8   148.8
  4989.9  141.86    5000  142.44    5010  148.19  5040.2  149.35  5050.3  154.39
  5070.4  158.53  5100.6  167.75    5161  167.23  5211.3   170.2  5714.4  156.29
  5774.8  153.13  5965.8  127.22  6141.3  127.72  6177.3   129.7  6217.5   134.6
  6358.4  163.73  6418.8  171.75  6670.4  177.64  6962.2  179.93  7059.4  181.02
#Mann= 7 ,-1 , 0
  3332.2     .05       0  3623.7      .1       0  4024.2     .16       0
  4462.3      .1       0  4919.5     .05       0  5070.4     .07       0
  6962.2     .05       0
#XS Ineff= 1 ,-1
 5202.26 6583.45  169.94
Permanent Ineff=
       T
Bank Sta=4949.6,5070.4
XS Rating Curve= 0 ,0
Exp/Cntr=0.3,0.1

Type RM Length L Ch R = 1 ,35222   ,616,616,616
BEGIN DESCRIPTION:
SULPHUR CREEK 31.0
END DESCRIPTION:
XS GIS Cut Line= 4
       2260628.9     13358887.66      2260802.52     13360519.65
      2260837.24     13361346.04      2261503.34     13362206.42
#Sta/Elev= 30
  3511.5  187.99  3860.9  183.41  4282.9  172.45  4350.4   170.6  4576.7  165.06
  4918.6  165.11  4938.7  157.42  4958.8  156.19    4999  140.09  5019.2  140.76
  5057.2  155.37  5069.4  156.91  5089.5  164.28  5169.9   154.9    5260  155.21
  5330.1  140.86  5360.1  131.28  5387.1  127.72  5389.9  127.22  5393.1  127.72
  5560.3  128.09  5600.3  132.85  5629.6  140.49  5633.2  138.28  5780.5  160.27
  5944.8  170.05  6294.9  176.98    6380  175.37  6778.4  184.46  7067.9  184.64
#Mann= 8 ,-1 , 0
  3511.5     .05       0  3860.9      .1       0  4282.9     .05       0
  4350.4      .1       0  5387.1     .07       0  5393.1      .1       0
  5633.2     .05       0  5944.8      .1       0
#XS Ineff= 1 ,-1
 5089.82 6000.71  164.49
Permanent Ineff=
       T
Bank Sta=4938.7,5069.4
XS Rating Curve= 0 ,0
Exp/Cntr=0.3,0.1

Type RM Length L Ch R = 1 ,34606   ,514,514,514
BEGIN DESCRIPTION:
SULPHUR CREEK 30.0
END DESCRIPTION:
XS GIS Cut Line= 4
      2260371.96     13359734.95      2260274.74     13360179.38
      2259628.91     13362012.71      2259059.56     13362832.01
#Sta/Elev= 30
  4268.2  226.09  4592.4  209.14  4715.9  193.29  4773.5  182.48  4789.4  177.02
  4820.4   178.1    4877  163.71  4932.5  159.52  4953.7  155.87  4975.1  147.54
  4985.5  137.92  4992.5  137.39  4995.2  136.89  4998.5  137.39  5017.3  148.15
  5049.1   145.1  5080.9  151.46  5101.3  151.66  5108.4   151.7    5278  146.57
  5387.2  147.86  5418.2  154.16  5423.5  159.87  5454.4  163.06  5594.5  163.88
  5982.1     163  6469.7  166.46    6973  180.45  7381.5  197.79  7664.6  201.91
#Mann= 8 ,-1 , 0
  4268.2     .05       0  4715.9      .1       0  4992.5     .07       0
  4998.5      .1       0  5101.3     .12       0  5108.4      .1       0
    5278     .12       0  5594.5      .1       0
Bank Sta=4932.5,5423.5
XS Rating Curve= 0 ,0
Exp/Cntr=0.3,0.1

Type RM Length L Ch R = 1 ,34092   ,928,928,928
BEGIN DESCRIPTION:
SULPHUR CREEK 29.0
END DESCRIPTION:
XS GIS Cut Line= 3
      2260237.69     13359746.88      2259737.72     13360246.85
      2258337.73     13362046.84
#Sta/Elev= 30
  4260.8  220.79  4439.1  190.21  4469.2  184.96  4543.6  181.01  4600.2  171.56
  4797.1   160.3  4840.6  159.37  4911.3  162.67  4953.7  157.51  4964.3  149.48
  4981.4  145.12  4986.6  138.09  4989.3  137.59  4992.6  138.09  5074.6  149.54
  5109.9  151.77  5188.7  147.13    5319  151.01  5346.1  155.67  5352.4  154.13
  5360.6  157.81  5385.7   157.9  5416.7  160.76  5530.7  162.97  5615.8  161.07
    5652  157.78    5680  161.21  6171.4  175.96  6820.2   210.9  7248.2  227.53
#Mann= 8 ,-1 , 0
  4260.8     .05       0  4439.1      .1       0  4469.2     .05       0
  4797.1      .1       0  4986.6     .07       0  4992.6      .1       0
    5319     .16       0  5385.7      .1       0
Bank Sta=4953.7,5360.6
XS Rating Curve= 0 ,0
Exp/Cntr=0.3,0.1

Type RM Length L Ch R = 1 ,33164   ,923,923,923
BEGIN DESCRIPTION:
SULPHUR CREEK 28.0
END DESCRIPTION:
XS GIS Cut Line= 3
      2259837.73     13359446.85      2258837.72     13360146.85
      2258337.72     13360746.86
#Sta/Elev= 30
    3779  180.65  4054.2  170.87  4188.4  166.65  4224.1  167.75  4347.6  164.61
  4614.7  160.16  4777.8  157.08  4812.8   154.7  4836.4  151.75  4914.2  148.94
  4935.6  145.68  4971.3  146.01  4992.3  139.99  4993.6  137.19  4996.4  136.69
  4999.6  137.19  5013.3  137.81  5035.5  148.92  5056.3  152.03  5064.1  156.05
  5084.9   157.7  5116.2  159.33  5226.8  157.97  5347.9  162.65  5588.7   182.3
  5624.5  183.26  5638.2   186.6  5666.8  187.72  5681.1  191.52  5780.7  198.26
#Mann= 9 ,-1 , 0
    3779      .1       0  4054.2     .16       0  4347.6      .1       0
  4614.7     .12       0  4812.8      .1       0  4836.4     .12       0
  4993.6     .07       0  4999.6     .12       0  5116.2      .1       0
Bank Sta=4777.8,5084.9
XS Rating Curve= 0 ,0
Exp/Cntr=0.3,0.1

Type RM Length L Ch R = 1 ,32241   ,746,746,746
BEGIN DESCRIPTION:
SULPHUR CREEK 27.0
END DESCRIPTION:
XS GIS Cut Line= 3
      2259837.75     13358546.84      2258037.72     13359746.85
      2257637.69     13360046.88
#Sta/Elev= 30
  2811.3  187.55  3503.9  162.63  3996.4  163.73  4483.4   156.6  4557.7  157.55
  4642.6  159.47  4722.3  156.96  4731.2  156.38  4807.9  150.44  4910.1  149.42
  4938.6  143.54  4977.8  141.54    4982   139.6  4985.2  134.44    4988  133.94
  4991.2  134.44  5005.1  136.63    5032  148.12  5067.4  149.57    5082  152.84
  5111.1  152.96  5124.7  156.44  5146.5  161.03    5182  163.67  5196.5  168.66
  5202.8  174.39  5246.5  183.81    5332  192.49  5367.4  192.42  5474.7  199.34
#Mann= 7 ,-1 , 0
  2811.3     .05       0  3996.4      .1       0  4557.7     .16       0
  4731.2     .12       0  4985.2     .07       0  4991.2     .12       0
  5005.1      .1       0
Bank Sta=4722.3,5124.7
XS Rating Curve= 0 ,0
Exp/Cntr=0.3,0.1

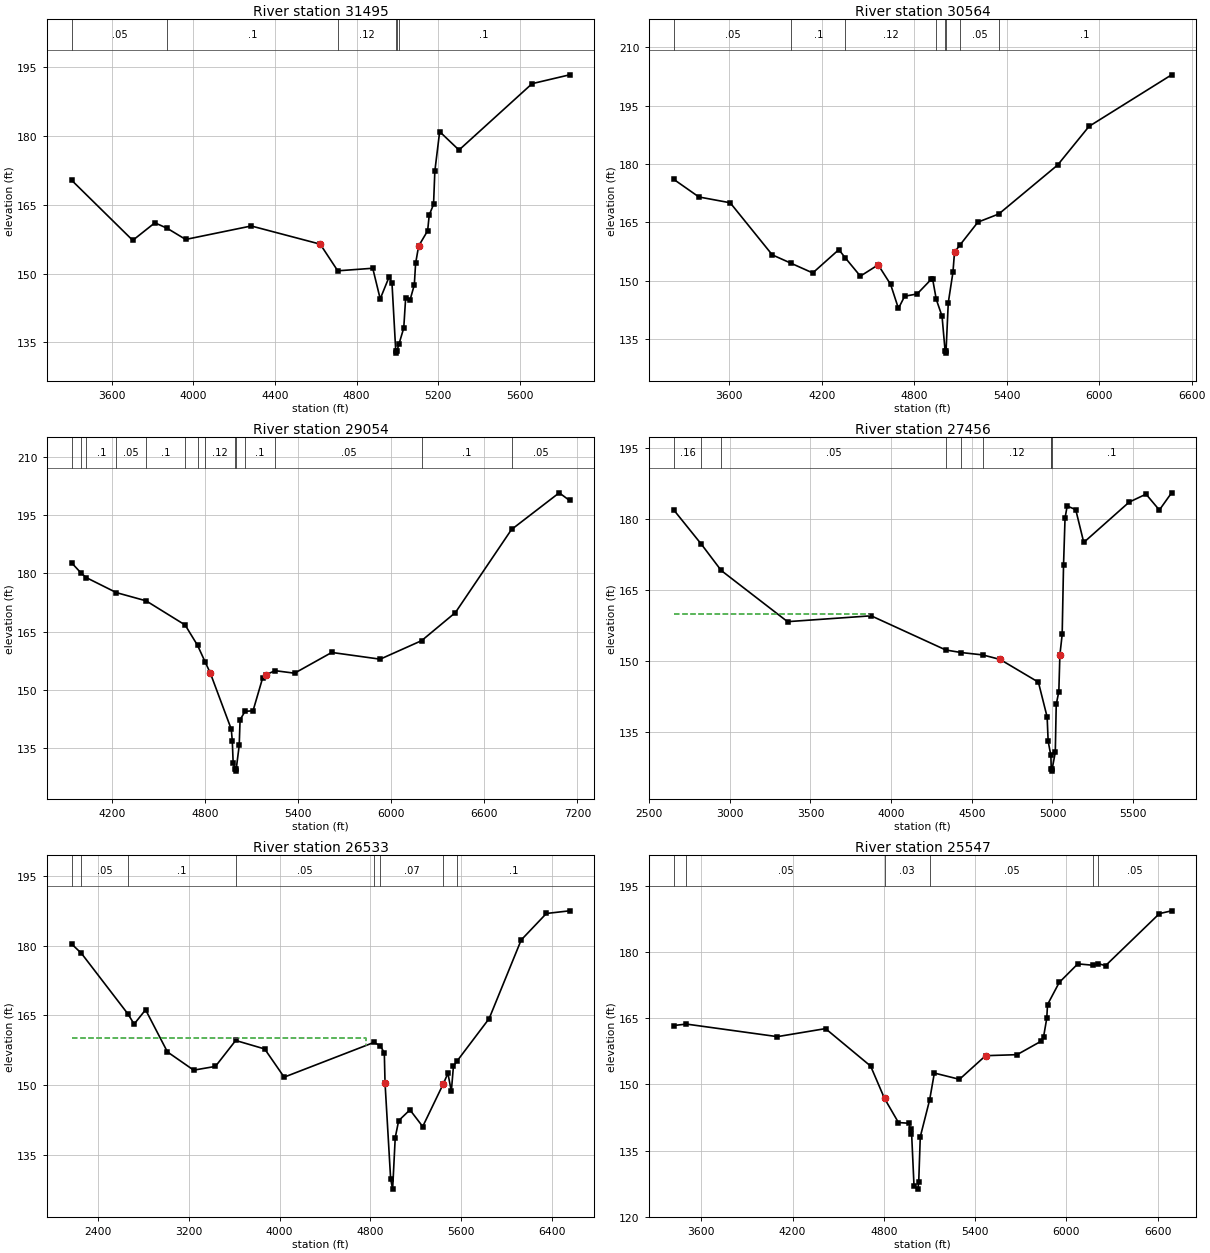
Type RM Length L Ch R = 1 ,31495   ,931,931,931
BEGIN DESCRIPTION:
SULPHUR CREEK 26.0
END DESCRIPTION:
XS GIS Cut Line= 4
      2259251.64     13358590.49      2257967.51     13359029.98
      2257507.43     13359318.39      2257500.56     13359860.89
#Sta/Elev= 30
  3402.2   170.4  3702.3  157.26  3810.6  161.09  3870.7  159.91  3961.8  157.46
  4283.6   160.4  4621.8  156.43  4707.8  150.61  4879.5  151.17  4916.1  144.48
  4959.8  149.28  4973.8  147.97  4992.3  133.14    4995  132.64  4998.3  133.14
  5007.5  134.53  5031.6  138.13    5041  144.78  5062.2   144.2  5083.4  147.55
  5089.7  152.22  5104.6  156.02  5148.7  159.35  5156.5  162.79  5177.7   165.1
  5184.1  172.39  5207.7     181  5302.5  176.98    5661  191.47    5845   193.4
#Mann= 6 ,-1 , 0
  3402.2     .05       0  3870.7      .1       0  4707.8     .12       0
  4992.3     .07       0  4998.3     .12       0  5007.5      .1       0
Bank Sta=4621.8,5104.6
XS Rating Curve= 0 ,0
Exp/Cntr=0.3,0.1

Type RM Length L Ch R = 1 ,30564   ,1510,1510,1510
BEGIN DESCRIPTION:
SULPHUR CREEK 25.0
END DESCRIPTION:
XS GIS Cut Line= 4
      2259529.58     13358387.42      2259152.01     13358452.52
      2257381.18      13358192.1      2256341.13     13358387.11
#Sta/Elev= 30
  3238.6  176.07  3402.9  171.51  3605.8  170.02  3878.8  156.64    4002  154.46
  4141.6  151.99    4311  157.98  4352.6  155.87  4450.5  151.17  4566.1  154.07
  4646.9  149.04  4697.5  142.87  4737.9  146.01  4818.8  146.59  4909.7  150.33
  4919.8  150.32    4943  145.21  4980.5  140.87  5000.4  131.89  5003.1  131.39
  5006.4  131.89  5020.9  144.34  5051.2  152.15  5061.4  157.33    5096  159.13
    5213  165.04  5348.8  167.14  5730.5  179.72    5934  189.64  6469.8  202.89
#Mann= 8 ,-1 , 0
  3238.6     .05       0    4002      .1       0  4352.6     .12       0
    4943      .1       0  5000.4     .07       0  5006.4      .1       0
    5096     .05       0  5348.8      .1       0
Bank Sta=4566.1,5061.4
XS Rating Curve= 0 ,0
Exp/Cntr=0.3,0.1

Type RM Length L Ch R = 1 ,29054   ,1598,1598,1598
BEGIN DESCRIPTION:
SULPHUR CREEK 24.0
END DESCRIPTION:
XS GIS Cut Line= 3
      2258969.74     13357384.82      2258253.57     13357059.29
      2256093.55     13358152.31
#Sta/Elev= 30
  3941.6  182.73  4003.7  180.04  4037.2  178.89  4230.3  175.04  4421.5  172.93
  4672.9  166.71  4753.1  161.46  4802.6  157.14  4835.7  154.28  4970.2  139.88
  4976.7   136.9  4982.3  131.24    4996  129.59  4998.7  129.09    5002  129.59
  5021.3  135.72  5026.9  142.33  5059.2  144.47  5110.4  144.63  5171.6  152.99
  5193.9   153.9  5252.1  154.95  5377.8   154.3  5617.2  159.64  5929.2  157.91
  6196.2  162.68  6413.8  169.91  6775.1  191.29  7082.2  200.73  7149.1  198.76
#Mann= 14 ,-1 , 0
  3941.6      .1       0  4003.7     .16       0  4037.2      .1       0
  4230.3     .05       0  4421.5      .1       0  4672.9     .05       0
  4753.1      .1       0  4802.6     .12       0    4996     .07       0
    5002     .12       0  5059.2      .1       0  5252.1     .05       0
  6196.2      .1       0  6775.1     .05       0
Bank Sta=4835.7,5193.9
XS Rating Curve= 0 ,0
Exp/Cntr=0.3,0.1

Type RM Length L Ch R = 1 ,27456   ,923,923,923
BEGIN DESCRIPTION:
SULPHUR CREEK 23.0
END DESCRIPTION:
XS GIS Cut Line= 2
      2259008.76     13357189.49      2256274.37     13355757.19
#Sta/Elev= 30
  2651.6  182.04  2824.4  174.72  2946.9  169.19    3358  158.37  3876.3  159.61
    4339  152.38  4434.9  151.84  4568.1  151.34  4675.7  150.38  4912.8  145.58
    4967  138.22  4973.3  133.09  4990.2  130.08  4992.4  127.27  4995.1  126.77
  4998.4  127.27  5017.5  130.74  5023.4  140.87  5039.5   143.6    5046  151.32
  5060.2  155.66  5068.6  170.29    5078  180.28  5091.2  182.82  5144.2  182.06
    5194  175.12  5475.2  183.64  5579.9  185.33  5662.5  181.97  5738.4  185.61
#Mann= 9 ,-1 , 0
  2651.6     .16       0  2824.4      .1       0  2946.9     .05       0
    4339      .1       0  4434.9     .05       0  4568.1     .12       0
  4990.2      .1       0  4992.4     .07       0  4998.4      .1       0
#XS Ineff= 2 , 0
         3861.39  159.91
Permanent Ineff=
       T       T
Bank Sta=4675.7,5046
XS Rating Curve= 0 ,0
Exp/Cntr=0.3,0.1

Type RM Length L Ch R = 1 ,26533   ,986,986,986
BEGIN DESCRIPTION:
SULPHUR CREEK 22.0
END DESCRIPTION:
XS GIS Cut Line= 2
      2260454.08     13355991.58      2256105.16     13355418.67
#Sta/Elev= 30
  2167.9  180.42  2253.9  178.42  2664.5  165.32    2719  163.14  2819.8  166.23
  3012.3  157.14  3243.5  153.21  3435.1  154.02  3613.4  159.61  3868.8  157.78
  4040.3   151.7  4832.3   159.2  4887.6  158.44  4922.5  156.95 4928.98   150.4
  4978.3  129.74  4995.8  127.56  5018.7  138.67  5048.9  142.32  5148.3  144.65
  5260.8  141.05  5442.3  150.27  5482.7  152.53  5512.9  148.65  5531.4  154.08
  5564.4  155.21  5845.9  164.33  6128.2  181.28  6350.1  186.99  6554.4  187.56
#Mann= 8 ,-1 , 0
  2167.9      .1       0  2253.9     .05       0  2664.5      .1       0
  3613.4     .05       0  4832.3      .1       0  4887.6     .07       0
  5442.3     .12       0  5564.4      .1       0
#XS Ineff= 2 , 0
         4758.13  160.12
Permanent Ineff=
       T       T
Bank Sta=4928.98,5442.3
XS Rating Curve= 0 ,0
Exp/Cntr=0.3,0.1

Type RM Length L Ch R = 1 ,25547   ,617,617,617
BEGIN DESCRIPTION:
SULPHUR CREEK 21.0
END DESCRIPTION:
XS GIS Cut Line= 4
      2258865.56     13353986.37      2258032.22     13354559.29
      2256495.76     13354910.85      2255818.68     13354806.69
#Sta/Elev= 30
  3418.5  163.35  3502.8  163.68  4100.2  160.83  4416.9  162.65  4713.4  154.15
 4804.55  146.81    4896  141.35  4967.8  141.17  4976.1  138.79  4981.3   139.9
  4998.6  126.85  5023.9  126.24  5029.4   127.9  5039.6   138.1  5101.2  146.49
    5132  152.57  5297.2  151.15  5468.9  156.51  5675.7  156.74  5832.9  159.78
  5850.1  160.86  5870.6  164.95  5875.8   168.1  5952.7  173.12  6074.8  177.34
    6176  177.02  6207.8   177.4  6256.9  176.93    6611  188.74    6691  189.37
#Mann= 6 ,-1 , 0
  3418.5      .1       0  3502.8     .05       0 4804.55     .03       0
  5101.2     .05       0    6176      .1       0  6207.8     .05       0
Bank Sta=4804.55,5468.9
XS Rating Curve= 0 ,0
Exp/Cntr=0.3,0.1