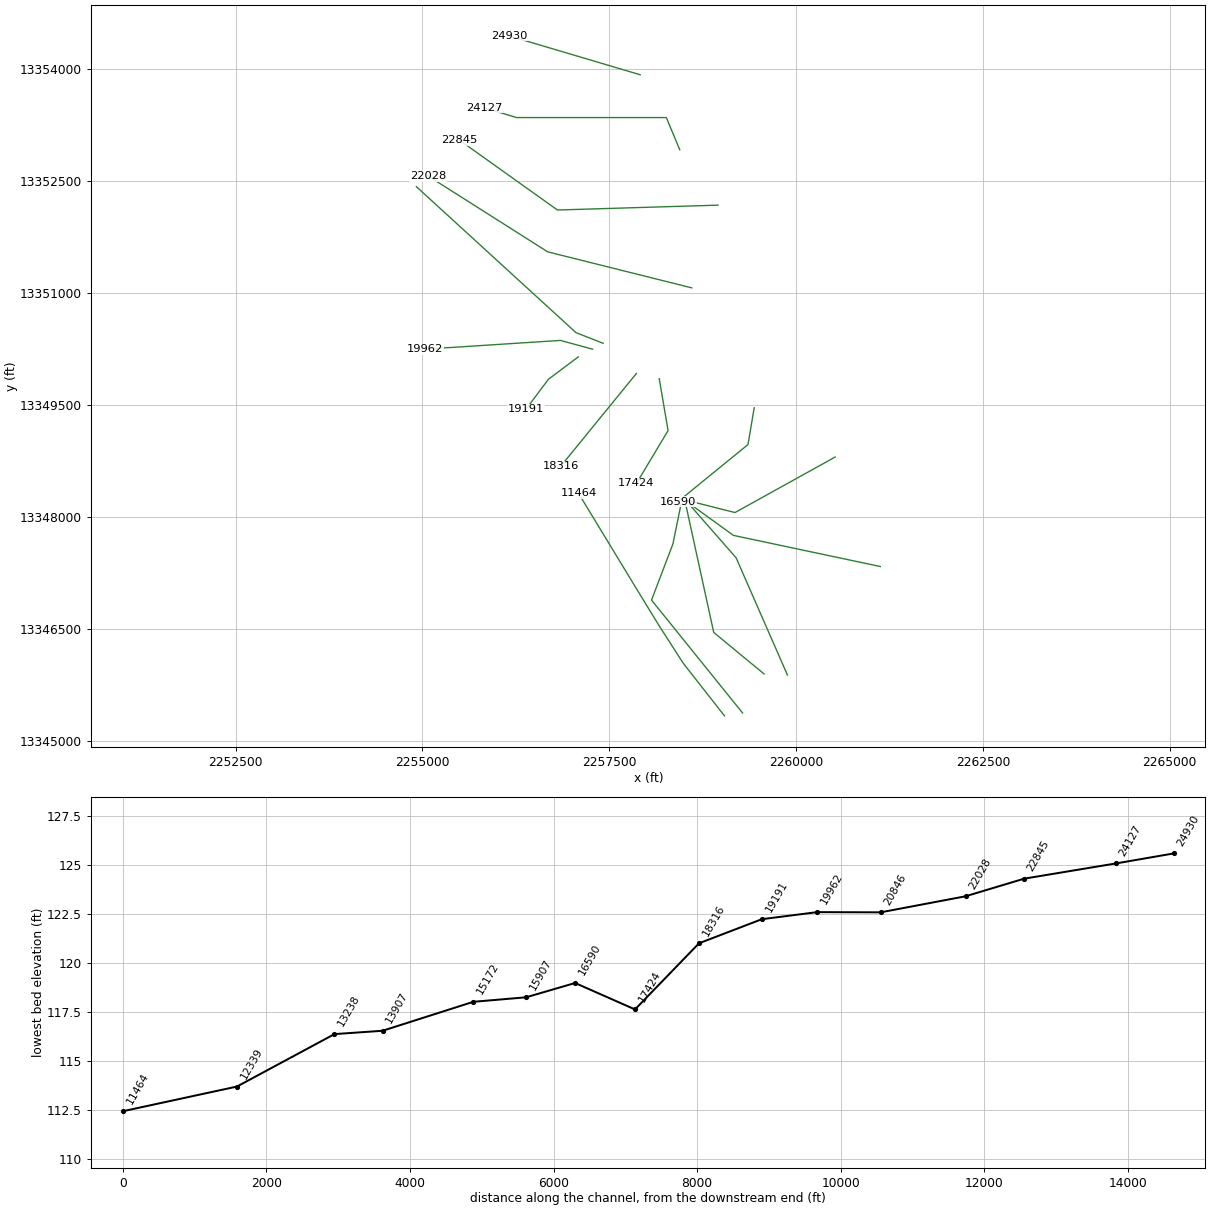
HEC-RAS study SULPHUR CREEK.prj: SULPHUR CREEK Base Level Engineering

--- SULPHUR CREEK.g01 (geometry) --- (continued)

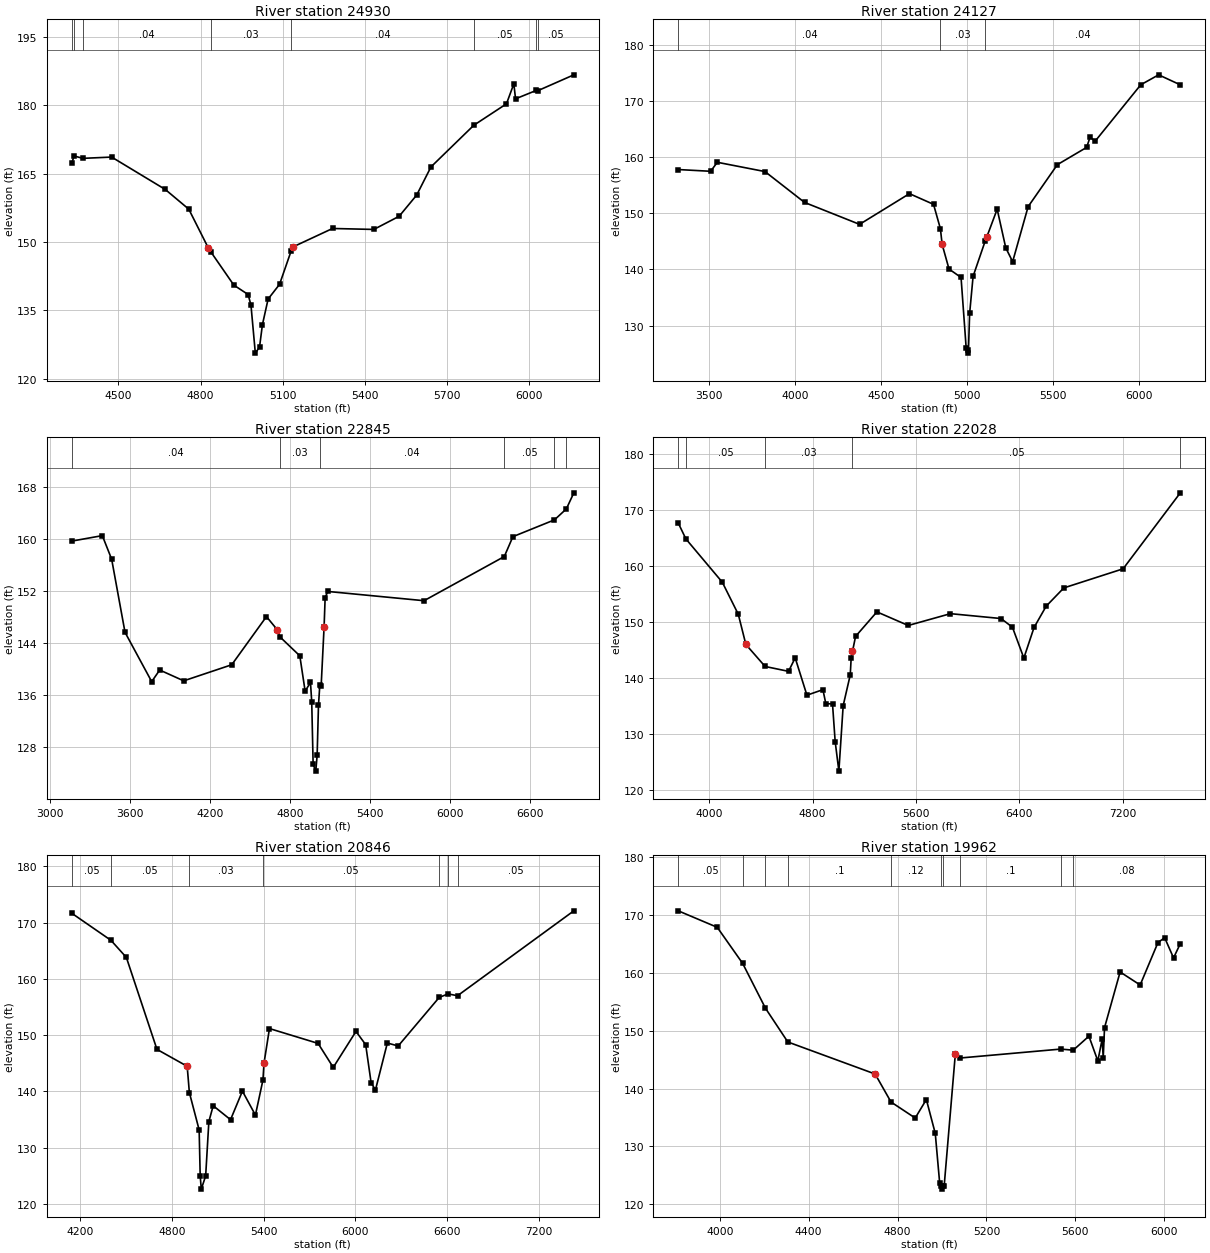
Type RM Length L Ch R = 1 ,24930   ,803,803,803
BEGIN DESCRIPTION:
SULPHUR CREEK 20.0
END DESCRIPTION:
XS GIS Cut Line= 2
      2257915.01     13353921.28      2256157.62     13354441.98
#Sta/Elev= 30
  4329.5   167.3  4337.9   168.9  4370.2  168.38  4475.1  168.66  4670.8  161.55
  4756.7  157.22  4828.4  148.65  4837.7   147.8  4921.2  140.54  4973.3  138.48
  4983.7  136.14  4999.6  125.61    5015  126.96  5025.5  131.86  5046.3  137.49
    5088  140.71  5129.8  147.95  5138.1  148.96  5281.5  152.98  5432.2  152.77
  5524.6  155.66  5588.7  160.32  5640.8   166.5  5797.3  175.65  5916.4  180.35
  5943.3  184.75  5949.6  181.45    6025  183.29  6031.8  183.26  6162.4  186.72
#Mann= 8 ,-1 , 0
  4329.5      .1       0  4337.9     .05       0  4370.2     .04       0
  4837.7     .03       0  5129.8     .04       0  5797.3     .05       0
    6025      .1       0  6031.8     .05       0
Bank Sta=4828.4,5138.1
XS Rating Curve= 0 ,0
Exp/Cntr=0.3,0.1

Type RM Length L Ch R = 1 ,24127   ,1282,1282,1282
BEGIN DESCRIPTION:
SULPHUR CREEK 19.0
END DESCRIPTION:
XS GIS Cut Line= 4
      2258444.73     13352917.08      2258264.72     13353348.35
      2256261.39     13353348.35      2255832.22      13353478.4
#Sta/Elev= 30
  3320.5  157.76  3508.7  157.45  3547.8  159.05  3824.8   157.4  4054.8  151.91
  4374.8  148.01  4664.8  153.47  4804.8  151.57  4844.8  147.23  4854.8  144.45
  4894.8  140.06  4964.8  138.56  4994.8  125.93  5004.6   125.1  5007.8   125.6
  5014.8  132.19  5034.8  138.76  5104.8  145.01  5114.8  145.79  5174.8  150.71
  5224.8  143.83  5264.8  141.37  5354.8  151.16  5524.8  158.63  5694.8   161.7
  5714.8   163.5  5744.8  162.82  6009.7  172.84  6113.6  174.61  6239.6  172.83
#Mann= 3 ,-1 , 0
  3320.5     .04       0  4844.8     .03       0  5104.8     .04       0
Bank Sta=4854.8,5114.8
XS Rating Curve= 0 ,0
Exp/Cntr=0.3,0.1

Type RM Length L Ch R = 1 ,22845   ,817,817,817
BEGIN DESCRIPTION:
SULPHUR CREEK 18.0
END DESCRIPTION:
XS GIS Cut Line= 3
      2258956.69     13352176.48      2256808.26     13352111.37
      2255493.14     13353048.89
#Sta/Elev= 30
  3164.9  159.63    3394  160.47    3464  156.85  3564.1  145.63  3764.1  138.06
  3824.2  139.84  4004.3  138.18  4364.4  140.65  4624.5  148.04  4704.6  146.05
  4724.6  144.95  4874.7  142.02  4914.7  136.59  4954.7  137.94    4964  134.98
  4974.7  125.34  4994.5  124.32  5004.7  126.77  5014.7  134.42  5024.7  137.54
  5034.7  137.39 5056.82  146.47  5064.7  150.97  5084.8   151.9  5806.2  150.48
    6408  157.26  6472.4  160.31  6784.1  162.89  6873.1  164.57  6929.4  167.04
#Mann= 6 ,-1 , 0
  3164.9     .04       0  4724.6     .03       0  5024.7     .04       0
    6408     .05       0  6784.1      .1       0  6873.1     .05       0
Bank Sta=4704.6,5056.82
XS Rating Curve= 0 ,0
Exp/Cntr=0.3,0.1

Type RM Length L Ch R = 1 ,22028   ,1182,1182,1182
BEGIN DESCRIPTION:
SULPHUR CREEK 17.0
END DESCRIPTION:
XS GIS Cut Line= 3
      2258605.12     13351069.71      2256678.05     13351551.48
       2255076.5     13352567.09
#Sta/Elev= 30
  3761.3  167.73  3820.5  164.89    4102  157.16  4225.7  151.43  4284.3  146.04
  4433.1  142.11  4614.2  141.24  4665.7  143.65  4756.5  136.98  4880.2  137.97
  4902.8  135.45  4954.3  135.44  4974.9  128.71  5003.6  123.42  5036.8  135.11
  5091.5   140.6  5098.6  143.59  5108.9   144.8  5132.7  147.48  5297.7  151.86
  5539.9  149.43  5866.5  151.54  6257.8  150.67    6346  149.11  6434.1  143.61
  6512.9  149.07  6606.9  152.88  6743.3  156.14  7201.7  159.55  7644.1  173.12
#Mann= 5 ,-1 , 0
  3761.3     .05       0  3820.5     .05       0  4433.1     .03       0
  5108.9     .05       0  7644.1     .05       0
Bank Sta=4284.3,5108.9
XS Rating Curve= 0 ,0
Exp/Cntr=0.3,0.1

Type RM Length L Ch R = 1 ,20846   ,884,884,884
BEGIN DESCRIPTION:
SULPHUR CREEK 16.0
END DESCRIPTION:
XS GIS Cut Line= 3
      2257420.27     13350327.51      2257055.66     13350470.75
      2254920.28     13352423.84
#Sta/Elev= 30
  4143.6  171.67  4400.2  166.85  4500.9  163.81    4701  147.46  4898.9  144.45
  4913.1  139.78  4977.2  133.13    4984  124.96  4991.2   122.6  5019.8  124.95
  5040.7  134.62  5069.1  137.43  5182.6  134.95  5260.3  140.03  5345.4  135.77
  5394.7  142.01  5401.5  144.98  5437.3  151.16  5755.5  148.52  5854.8  144.25
  6003.4  150.65  6066.9   148.3  6102.7  141.49    6131  140.24  6208.7  148.59
  6279.7  148.06  6548.5  156.71  6606.5  157.32  6668.1     157  7429.2   172.1
#Mann= 7 ,-1 , 0
  4143.6     .05       0  4400.2     .05       0  4913.1     .03       0
  5394.7     .05       0  6548.5     .05       0  6606.5      .1       0
  6668.1     .05       0
Bank Sta=4898.9,5401.5
XS Rating Curve= 0 ,0
Exp/Cntr=0.3,0.1

Type RM Length L Ch R = 1 ,19962   ,771,771,771
BEGIN DESCRIPTION:
SULPHUR CREEK 15.0
END DESCRIPTION:
XS GIS Cut Line= 3
      2257277.04     13350249.39      2256847.32     13350366.58
      2255037.42     13350249.39
#Sta/Elev= 30
  3813.2  170.72  3988.7  167.87  4103.1  161.63  4205.7  153.88  4306.2  148.05
  4699.1  142.51  4770.6  137.67  4879.5   134.9  4929.6   138.1  4969.7  132.24
  4989.7  123.59  4996.8  123.11  4999.5  122.61  5002.8  123.11  5009.8  123.17
  5059.9  145.93  5082.4  145.28  5534.2  146.82  5590.5  146.63  5661.1  149.05
  5701.2  144.77  5720.5  148.51  5725.5  145.32  5731.3  150.52  5801.4  160.15
  5891.6   157.9  5971.8  165.24  6001.9  166.07  6041.9  162.58  6072.3  165.05
#Mann= 10 ,-1 , 0
  3813.2     .05       0  4103.1      .1       0  4205.7     .05       0
  4306.2      .1       0  4770.6     .12       0  4996.8     .07       0
  5002.8     .12       0  5082.4      .1       0  5534.2     .05       0
  5590.5     .08       0
Bank Sta=4699.1,5059.9
XS Rating Curve= 0 ,0
Exp/Cntr=0.3,0.1

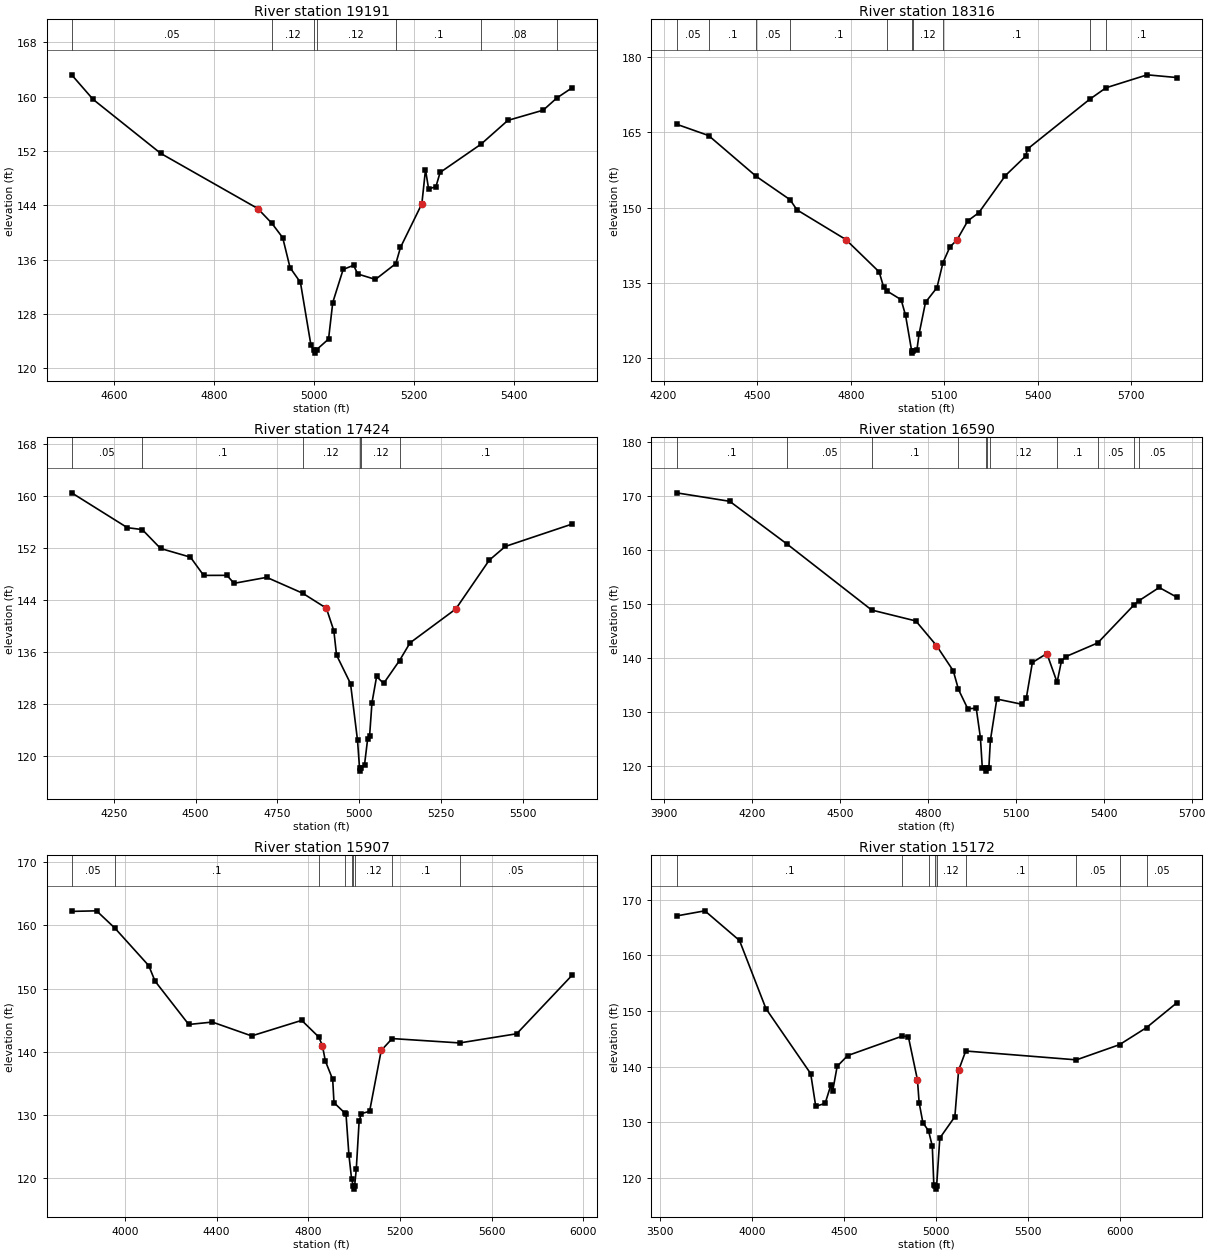
Type RM Length L Ch R = 1 ,19191   ,875,875,875
BEGIN DESCRIPTION:
SULPHUR CREEK 14.0
END DESCRIPTION:
XS GIS Cut Line= 3
      2257087.71     13350146.85      2256687.72     13349846.85
      2256387.72     13349446.85
#Sta/Elev= 30
    4516  163.22  4558.7  159.61  4694.1  151.65  4887.9  143.54  4916.1  141.37
  4937.9  139.24  4952.5  134.84  4973.3  132.66  4994.1  123.51  4999.5  122.75
  5002.2  122.25  5005.5  122.75  5029.5  124.32  5037.9   129.7  5058.7  134.57
  5079.5  135.18  5087.9   133.9  5123.3   133.1    5164  135.43  5173.3  137.81
    5216  144.23  5223.3  149.26  5229.5  146.43  5244.1  146.74  5252.5  148.85
  5334.3  153.01  5387.9  156.51  5458.7  158.02    5486  159.82    5516  161.29
#Mann= 7 ,-1 , 0
    4516     .05       0  4916.1     .12       0  4999.5     .07       0
  5005.5     .12       0    5164      .1       0  5334.3     .08       0
    5486      .1       0
Bank Sta=4887.9,5216
XS Rating Curve= 0 ,0
Exp/Cntr=0.3,0.1

Type RM Length L Ch R = 1 ,18316   ,892,892,892
BEGIN DESCRIPTION:
SULPHUR CREEK 13.0
END DESCRIPTION:
XS GIS Cut Line= 2
      2257864.52     13349924.23      2256850.63     13348681.18
#Sta/Elev= 30
  4241.4   166.6  4344.3  164.34  4497.3   156.2  4605.4  151.57  4627.8  149.54
  4784.3  143.64  4891.3  137.19  4905.7  134.14  4917.9  133.33  4961.7  131.66
    4976  128.52  4995.3  121.52    4998  121.02  5001.3  121.52  5012.3  121.64
  5019.1  124.78  5039.9  131.14  5076.6  134.06  5095.9  139.04  5118.2  142.17
  5140.5  143.53  5175.6  147.36  5210.8  148.98  5296.2  156.38  5360.7  160.22
  5367.4  161.68  5566.3  171.56  5618.7  173.85  5750.8  176.43  5845.5  175.89
#Mann= 10 ,-1 , 0
  4241.4     .05       0  4344.3      .1       0  4497.3     .05       0
  4605.4      .1       0  4917.9     .12       0  4995.3     .07       0
  5001.3     .12       0  5095.9      .1       0  5566.3     .05       0
  5618.7      .1       0
Bank Sta=4784.3,5140.5
XS Rating Curve= 0 ,0
Exp/Cntr=0.3,0.1

Type RM Length L Ch R = 1 ,17424   ,834,834,834
BEGIN DESCRIPTION:
SULPHUR CREEK 12.0
END DESCRIPTION:
XS GIS Cut Line= 3
      2258170.07     13349854.78      2258288.12     13349160.33
      2257864.54     13348452.04
#Sta/Elev= 30
  4121.2  160.51  4291.5  155.14    4337  154.85    4393  151.94  4484.3   150.6
  4524.8  147.79  4595.8   147.8  4617.8  146.57  4717.6  147.49  4827.4  145.05
    4900  142.74  4922.9  139.26  4931.1  135.52  4973.9  131.12  4995.3  122.38
  5001.4  118.14  5004.2  117.64  5007.4  118.14  5016.7  118.62  5026.4  122.66
  5032.3  123.12  5039.4  128.15  5053.7  132.22  5075.1  131.15  5123.7  134.67
  5155.9   137.4  5295.7  142.61    5398  150.13  5447.2  152.25  5650.9  155.69
#Mann= 6 ,-1 , 0
  4121.2     .05       0    4337      .1       0  4827.4     .12       0
  5001.4     .07       0  5007.4     .12       0  5123.7      .1       0
Bank Sta=4900,5295.7
XS Rating Curve= 0 ,0
Exp/Cntr=0.3,0.1

Type RM Length L Ch R = 1 ,16590   ,683,683,683
BEGIN DESCRIPTION:
Mapping XS a708c28c
END DESCRIPTION:
XS GIS Cut Line= 3
       2259440.9     13349465.91      2259357.57     13348972.83
      2258421.37     13348210.01
#Sta/Elev= 30
  3941.5  170.53  4123.1  168.96  4319.4  161.02  4607.9  148.82  4758.6   146.8
  4828.9  142.25  4886.4  137.56  4904.1  134.11  4935.9  130.53  4964.7  130.65
    4979  125.18  4985.5  119.55  4996.9  119.49  4999.6  118.99  5002.9  119.49
  5007.8  119.55    5013  124.69    5035  132.34  5121.2  131.37  5135.6   132.5
  5156.4  139.11  5205.9  140.77  5240.8  135.44  5255.5  139.35  5269.9  140.18
  5379.4  142.73  5504.6  149.84    5520  150.54  5589.4     153  5649.2  151.21
#Mann= 11 ,-1 , 0
  3941.5      .1       0  4319.4     .05       0  4607.9      .1       0
  4904.1     .16       0  4996.9     .07       0  5002.9     .16       0
    5013     .12       0  5240.8      .1       0  5379.4     .05       0
  5504.6      .1       0    5520     .05       0
Bank Sta=4828.9,5205.9
XS Rating Curve= 0 ,0
Exp/Cntr=0.3,0.1

Type RM Length L Ch R = 1 ,15907   ,735,735,735
BEGIN DESCRIPTION:
Mapping XS 522e36c1
END DESCRIPTION:
XS GIS Cut Line= 3
      2260524.27     13348806.18      2259183.95     13348063.11
      2258554.27     13348222.26
#Sta/Elev= 30
  3767.5   162.2  3875.9  162.29  3955.5  159.57  4103.6  153.62  4131.1  151.17
  4278.1  144.31    4381  144.69  4552.5   142.5  4770.9  144.96  4844.9  142.34
  4861.2  140.97  4873.9  138.54    4906  135.62  4911.7  131.94    4960  130.26
  4964.1  130.13  4976.9  123.63  4988.3  119.91  4995.7  118.76  4998.4  118.26
  5001.7  118.76    5009  121.47  5021.3  128.99  5030.7   130.2    5067  130.57
  5117.7   140.2  5165.4  142.08    5460  141.39  5708.7  142.84  5949.5  152.07
#Mann= 9 ,-1 , 0
  3767.5     .05       0  3955.5      .1       0  4844.9     .12       0
    4960     .16       0  4988.3     .12       0  4995.7     .07       0
  5001.7     .12       0  5165.4      .1       0    5460     .05       0
Bank Sta=4861.2,5117.7
XS Rating Curve= 0 ,0
Exp/Cntr=0.3,0.1

Type RM Length L Ch R = 1 ,15172   ,1265,1265,1265
BEGIN DESCRIPTION:
Mapping XS 3fa681d8
END DESCRIPTION:
XS GIS Cut Line= 3
      2261128.36     13347340.89      2259163.12     13347757.55
      2258586.77     13348174.19
#Sta/Elev= 30
  3590.2   167.1  3744.4  168.02  3932.8  162.69  4076.7  150.44  4319.9  138.77
  4347.3  132.91  4398.4  133.43  4429.1  136.66  4439.3  135.61  4463.8  140.09
  4521.1  142.02  4818.2  145.52  4850.9  145.42  4900.5  137.64  4909.5  133.58
    4930  129.95  4960.6  128.52  4981.1  125.75  4989.6  118.71  4998.5  118.53
  5001.3  118.03  5004.5  118.53    5022   127.2  5103.8  131.04  5124.2  139.37
  5162.9  142.84  5764.8  141.25  5999.2  143.98  6146.6  147.06  6310.3  151.48
#Mann= 9 ,-1 , 0
  3590.2      .1       0  4818.2     .16       0  4960.6     .12       0
  4998.5     .07       0  5004.5     .12       0  5162.9      .1       0
  5764.8     .05       0  5999.2      .1       0  6146.6     .05       0
#XS Ineff= 2 , 0
         4811.17  145.33
Permanent Ineff=
       T       T
Bank Sta=4900.5,5124.2
XS Rating Curve= 0 ,0
Exp/Cntr=0.3,0.1

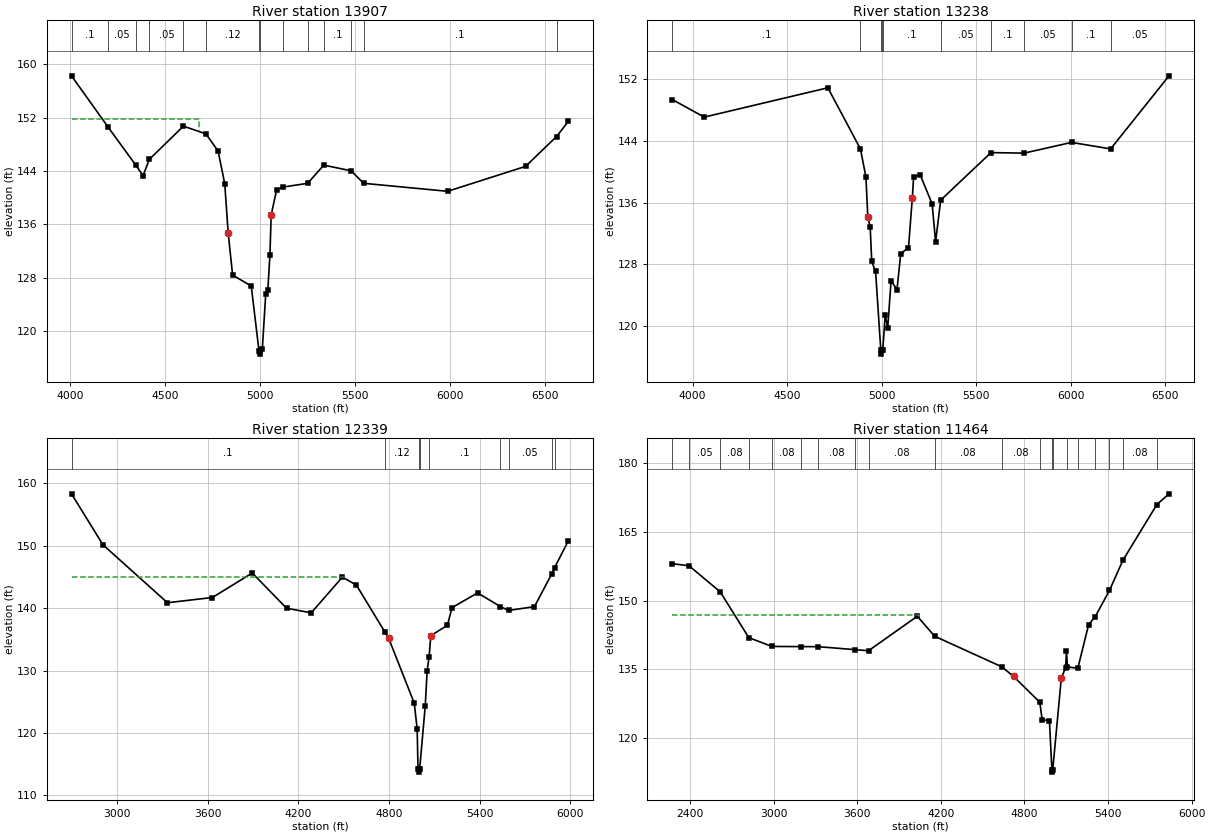
Type RM Length L Ch R = 1 ,13907   ,669,669,669
BEGIN DESCRIPTION:
SULPHUR CREEK 11.0
END DESCRIPTION:
XS GIS Cut Line= 3
      2259885.36     13345889.46      2259197.84     13347458.94
      2258601.68     13348138.29
#Sta/Elev= 30
  4008.2  158.29  4202.2  150.55  4347.1  144.88  4385.3  143.31  4417.8  145.75
  4597.6  150.74  4716.3  149.59  4780.5     147  4815.5   142.1  4833.4  134.79
  4856.8  128.41  4955.2  126.76  4995.8  117.05  4998.6  116.55  5001.8  117.05
  5013.4  117.28  5031.4  125.61  5042.5  126.17  5053.4  131.35  5060.2  137.46
    5089   141.2  5121.2   141.6  5252.7  142.17    5337   144.9    5482  144.04
  5546.7  142.17  5989.4  140.97  6400.3  144.71  6563.2  149.18  6625.5  151.45
#Mann= 14 ,-1 , 0
  4008.2      .1       0  4202.2     .05       0  4347.1      .1       0
  4417.8     .05       0  4597.6      .1       0  4716.3     .12       0
  4995.8     .07       0  5001.8     .12       0  5121.2      .1       0
  5252.7     .16       0    5337      .1       0    5482     .16       0
  5546.7      .1       0  6563.2     .05       0
#XS Ineff= 2 , 0
         4678.92  151.74
Permanent Ineff=
       T       T
Bank Sta=4833.4,5060.2
XS Rating Curve= 0 ,0
Exp/Cntr=0.3,0.1

Type RM Length L Ch R = 1 ,13238   ,1359,1359,1359
BEGIN DESCRIPTION:
SULPHUR CREEK 10.0
END DESCRIPTION:
XS GIS Cut Line= 3
      2259572.84     13345903.39      2258899.23     13346458.94
       2258524.5     13348173.02
#Sta/Elev= 30
    3892  149.38  4061.6   147.1  4715.3   150.9  4887.5  142.98  4916.5  139.36
  4926.8  134.11  4939.1  132.87  4947.3   128.4  4967.7  127.09  4995.4  116.88
  4998.2  116.38  5001.4  116.88  5005.6  116.94  5018.9  121.46    5032   119.8
  5049.6  125.88    5081  124.74  5100.8   129.4  5141.7  130.17  5162.2  136.67
  5168.8  139.33  5203.2  139.64  5266.8  135.85  5285.1  130.93    5312  136.34
    5578   142.5  5753.2  142.43    6004  143.82    6211  142.98  6519.7  152.45
#Mann= 10 ,-1 , 0
    3892      .1       0  4887.5     .12       0  4995.4     .07       0
  5001.4     .12       0  5005.6      .1       0    5312     .05       0
    5578      .1       0  5753.2     .05       0    6004      .1       0
    6211     .05       0
Bank Sta=4926.8,5162.2
XS Rating Curve= 0 ,0
Exp/Cntr=0.3,0.1

Type RM Length L Ch R = 1 ,12339   ,1589,1589,1589
BEGIN DESCRIPTION:
SULPHUR CREEK 9.1
END DESCRIPTION:
XS GIS Cut Line= 4
      2259284.76     13345381.62       2258066.6     13346892.03
      2258353.06     13347642.89      2258461.56      13348176.7
#Sta/Elev= 30
  2698.4  158.34  2906.5  150.17  3333.5  140.87    3631  141.71  3894.9  145.64
    4122  139.99  4285.3  139.25  4491.5  144.98  4584.3   143.7  4773.1  136.16
  4797.7  135.18  4967.5  124.75  4986.5  120.62  4992.2  114.22    4997   114.2
  4999.8   113.7    5003   114.2    5040  124.31  5052.4  129.93  5065.5  132.21
  5077.1   135.6  5186.8  137.25  5216.8  140.08  5386.6  142.45  5537.1  140.26
  5591.7  139.64  5762.9  140.24  5876.9  145.48  5895.7  146.47  5987.2   150.8
#Mann= 9 ,-1 , 0
  2698.4      .1       0  4773.1     .12       0    4997     .07       0
    5003     .12       0  5065.5      .1       0  5537.1     .08       0
  5591.7     .05       0  5876.9      .1       0  5895.7     .05       0
#XS Ineff= 2 , 0
          4509.9  145.05
Permanent Ineff=
       T       T
Bank Sta=4797.7,5077.1
XS Rating Curve= 0 ,0
Exp/Cntr=0.3,0.1

Type RM Length L Ch R = 1 ,11464   ,229,229,229
BEGIN DESCRIPTION:
SULPHUR CREEK 9.0
END DESCRIPTION:
XS GIS Cut Line= 5
      2259043.18     13345342.52      2258491.95     13346045.67
      2258170.77      13346544.8      2257862.61     13347048.28
      2257090.03       13348320.
#Sta/Elev= 30
  2272.2  158.06    2393  157.61  2617.1  151.88  2821.7  141.88  2987.2  139.95
  3198.1  139.91  3317.7   139.9  3586.8  139.24    3681  139.01  4031.3  146.56
  4155.3  142.19  4638.9  135.47  4722.3  133.37  4909.9  127.75  4927.1  123.93
  4979.3  123.68    4997  112.94  4999.8  112.44    5003  112.94  5064.7  133.06
  5095.6  135.28  5101.5  138.85  5108.8  135.47    5183  135.17  5260.5  144.72
  5307.8  146.45  5409.8   152.2  5506.7  158.81  5750.1     171  5837.5  173.35
#Mann= 20 ,-1 , 0
  2272.2     .08       0    2393     .05       0  2617.1     .08       0
  2821.7      .1       0  2987.2     .08       0  3198.1      .1       0
  3317.7     .08       0  3586.8      .1       0    3681     .08       0
  4155.3     .08       0  4638.9     .08       0  4909.9     .08       0
    4997     .07       0    5003     .08       0  5108.8     .08       0
    5183      .1       0  5307.8     .08       0  5409.8      .1       0
  5506.7     .08       0  5750.1      .1       0
#XS Ineff= 2 , 0
         4042.43  146.85
Permanent Ineff=
       T       T
Bank Sta=4722.3,5064.7
XS Rating Curve= 0 ,0
Exp/Cntr=0.3,0.1