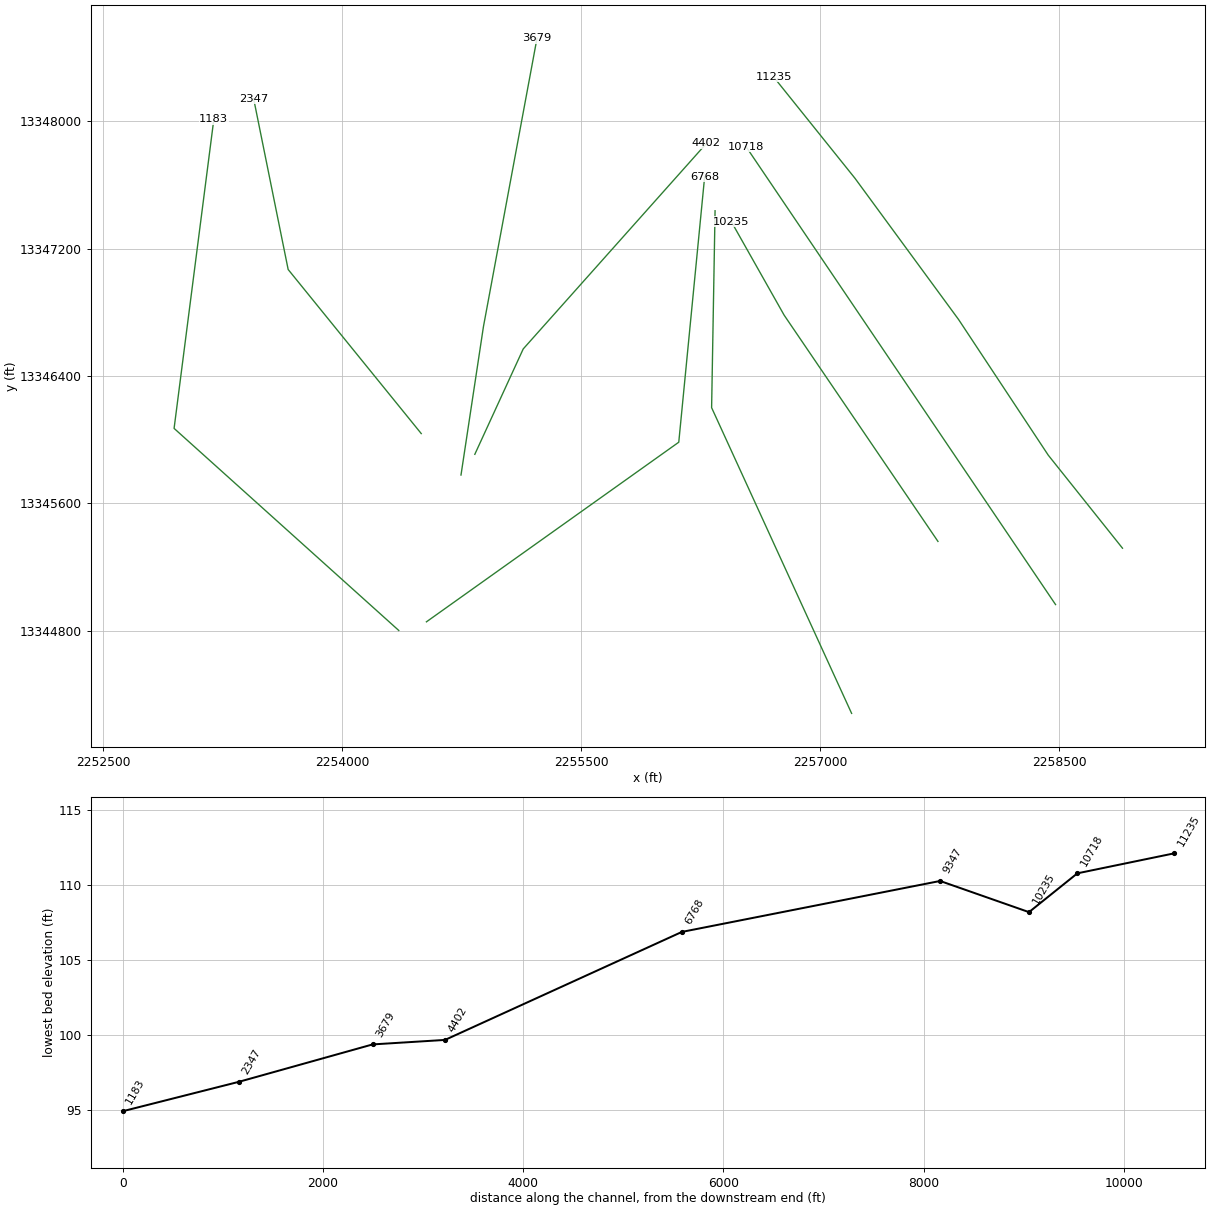
HEC-RAS study SULPHUR CREEK.prj: SULPHUR CREEK Base Level Engineering

--- SULPHUR CREEK.g01 (geometry) --- (continued)

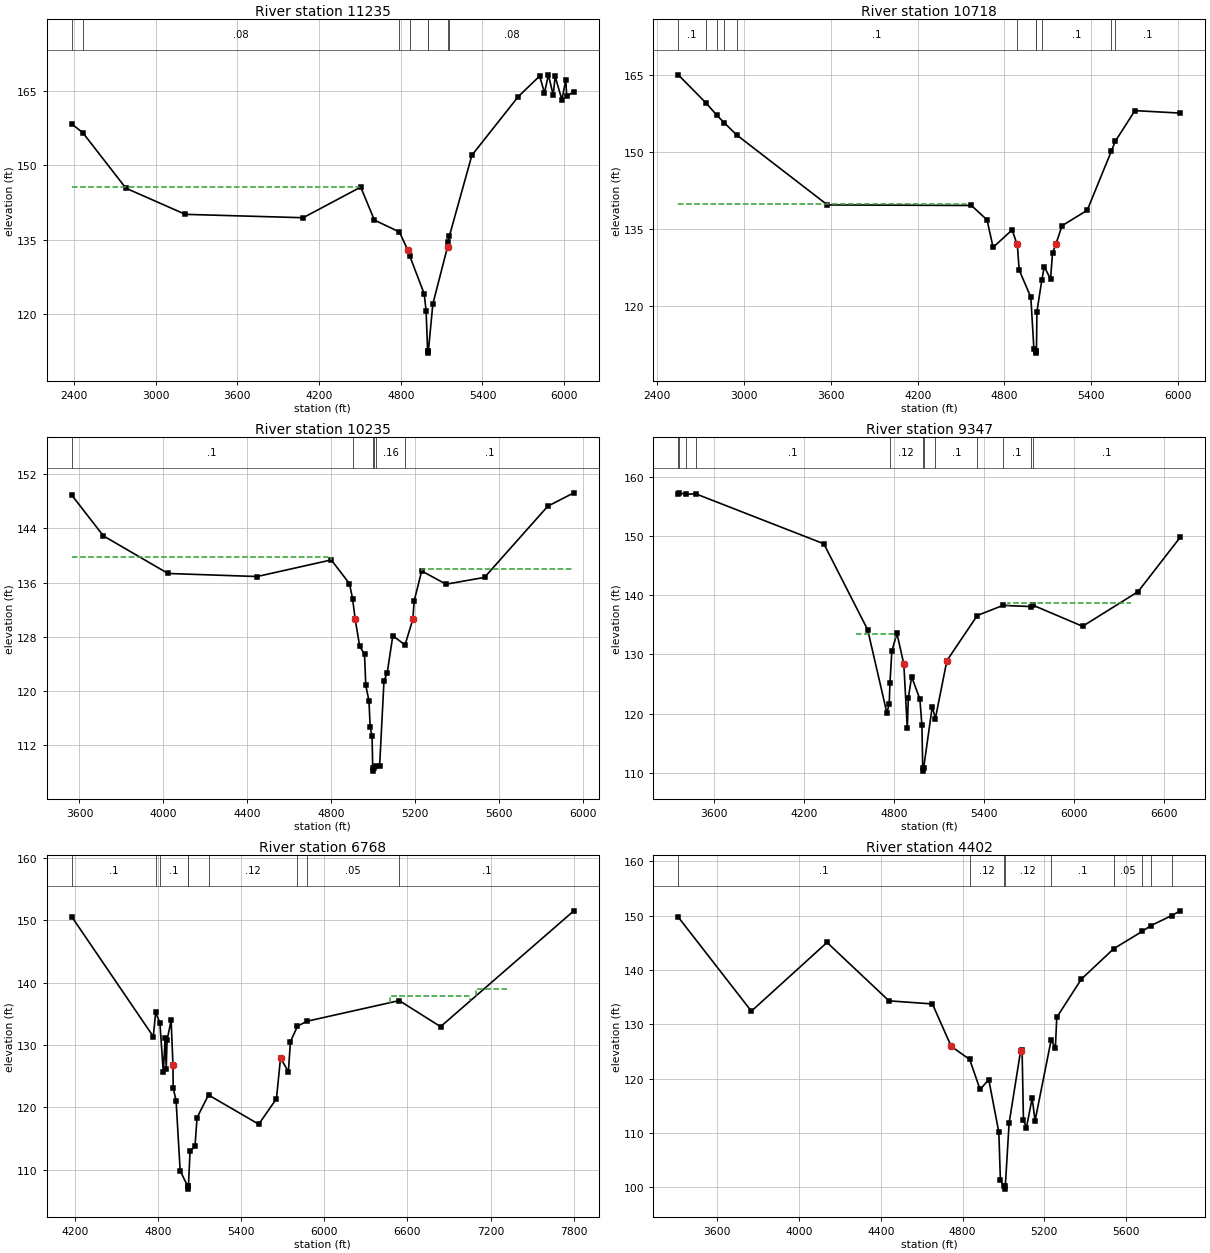
Type RM Length L Ch R = 1 ,11235   ,964,964,964
BEGIN DESCRIPTION:
Mapping XS f9d5e679
END DESCRIPTION:
XS GIS Cut Line= 5
      2258898.49     13345318.67      2258432.34     13345903.31
      2257869.84     13346754.87       2257218.8     13347642.89
      2256707.75     13348280.06
#Sta/Elev= 30
  2384.6  158.38  2465.8  156.61    2782  145.42  3218.4  140.14  4083.4  139.46
    4506  145.64  4606.3  138.99  4790.3  136.58  4849.7  133.03  4864.8  131.83
  4972.1  124.09  4986.1  120.69    4997  112.63  4999.8  112.13    5003  112.63
  5035.7  122.06  5143.5  133.58  5149.6   134.5  5157.6  135.81  5322.2  152.07
  5663.1  163.91  5819.9  168.06  5855.1  164.64  5883.9   168.3  5919.1  164.24
  5933.5  167.97  5983.2  163.27    6012  167.31  6018.4  163.95  6070.8  164.89
#Mann= 8 ,-1 , 0
  2384.6      .1       0  2465.8     .08       0  4790.3      .1       0
  4864.8     .08       0    4997     .07       0    5003     .08       0
  5149.6      .1       0  5157.6     .08       0
#XS Ineff= 2 , 0
         4495.05   145.7
Permanent Ineff=
       T       T
Bank Sta=4849.7,5143.5
XS Rating Curve= 0 ,0
Exp/Cntr=0.3,0.1

Type RM Length L Ch R = 1 ,10718   ,483,483,483
BEGIN DESCRIPTION:
SULPHUR CREEK 7.0
END DESCRIPTION:
XS GIS Cut Line= 2
      2258478.24     13344964.61      2256535.94     13347840.09
#Sta/Elev= 30
  2545.4  165.05  2737.2  159.57  2812.5  157.16    2863  155.72  2949.3  153.33
  3576.7  139.69  4571.7  139.58  4679.6  136.77  4721.6  131.42    4853  134.82
  4886.2  132.08  4889.2  131.99  4901.5  127.02  4982.3   121.7  5003.3   111.7
  5015.3   111.3  5018.1   110.8  5021.3   111.3  5024.3  118.88  5058.5  125.08
  5075.3  127.66  5118.5  125.21  5132.2  130.31  5154.7  131.99  5198.1  135.64
  5371.9  138.64  5539.5  150.22  5565.8  152.09  5701.7  158.07  6015.4  157.59
#Mann= 11 ,-1 , 0
  2545.4      .1       0  2737.2     .16       0  2812.5      .1       0
    2863     .16       0  2949.3      .1       0  4886.2     .16       0
  5015.3     .07       0  5021.3     .16       0  5058.5      .1       0
  5539.5     .08       0  5565.8      .1       0
#XS Ineff= 2 , 0
         4536.77  139.91
Permanent Ineff=
       T       T
Bank Sta=4889.2,5154.7
XS Rating Curve= 0 ,0
Exp/Cntr=0.3,0.1

Type RM Length L Ch R = 1 ,10235   ,888,888,888
BEGIN DESCRIPTION:
Mapping XS a3de9036
END DESCRIPTION:
XS GIS Cut Line= 3
      2257739.97     13345361.37      2256774.28     13346782.79
      2256442.28     13347371.04
#Sta/Elev= 30
  3563.4   148.9  3713.9   142.9  4022.3  137.35  4447.4   136.9  4800.6  139.35
  4887.4  135.85  4902.2  133.66  4914.5  130.65  4936.1  126.61  4959.3  125.45
  4965.3  120.84  4980.3   118.6  4986.3  114.68  4995.2  113.33  4998.3  108.71
    5001  108.21  5004.3  108.71  5013.7  108.93  5031.1  108.91  5052.1  121.54
  5067.1  122.63  5094.1  128.17  5152.3  126.81  5189.8  130.61  5195.8  133.29
  5231.8  137.72  5347.8  135.77  5531.3  136.77  5833.1  147.27  5957.3  149.24
#Mann= 6 ,-1 , 0
  3563.4      .1       0  4902.2     .12       0  4998.3     .07       0
  5004.3     .12       0  5013.7     .16       0  5152.3      .1       0
#XS Ineff= 2 , 0
         4797.74  139.72 5232.67          138.01
Permanent Ineff=
       T       T
Bank Sta=4914.5,5189.8
XS Rating Curve= 0 ,0
Exp/Cntr=0.3,0.1

Type RM Length L Ch R = 1 ,9347    ,2579,2579,2579
BEGIN DESCRIPTION:
Mapping XS 8050ddf6
END DESCRIPTION:
XS GIS Cut Line= 3
      2257197.86     13344281.01      2256318.95      13346201.6
      2256340.65     13347438.56
#Sta/Elev= 30
  3361.7  157.14  3366.7  157.31  3415.6  157.06  3477.8  157.15  4332.9   148.7
  4625.5  134.17  4753.8   120.1  4769.1  121.64  4774.2  125.25  4786.6  130.54
  4820.6  133.56  4866.6  128.37  4889.6  117.54  4896.8  122.72  4918.8  126.24
  4973.7  122.45  4987.2  118.03  4992.7  110.79  4995.5  110.29  4998.7  110.79
  5056.2  121.19  5077.1  119.18  5153.8  128.95  5356.5  136.58  5527.7  138.29
  5716.6  138.09  5730.5   138.3  6059.2  134.76  6429.2  140.61    6711  149.82
#Mann= 12 ,-1 , 0
  3361.7     .05       0  3366.7      .1       0  3415.6     .05       0
  3477.8      .1       0  4774.2     .12       0  4992.7     .07       0
  4998.7     .12       0  5077.1      .1       0  5356.5     .05       0
  5527.7      .1       0  5716.6     .05       0  5730.5      .1       0
#XS Ineff= 2 ,-1
 4544.55 4810.47  133.52 5562.94 6383.31  138.66
Permanent Ineff=
       T       T
Bank Sta=4866.6,5153.8
XS Rating Curve= 0 ,0
Exp/Cntr=0.3,0.1

Type RM Length L Ch R = 1 ,6768    ,2366,2366,2366
BEGIN DESCRIPTION:
Mapping XS f41746a4
END DESCRIPTION:
XS GIS Cut Line= 3
      2254528.61     13344856.14      2256112.78     13345984.59
      2256275.36      13347653.7
#Sta/Elev= 30
  4179.2  150.58  4767.4  131.36  4784.4  135.23    4815  133.56  4839.5  125.63
  4853.4   131.2  4860.4  126.19  4866.5  130.75    4896  133.98 4909.09  126.88
  4910.8  123.15  4931.7  121.07  4961.2  109.84  5014.8  107.39  5017.5  106.89
  5020.8  107.39  5032.5  112.98  5068.2  113.75  5082.9  118.36  5165.6  121.99
    5528   117.3  5655.8  121.39  5685.3  127.95  5741.9  125.71  5756.7  130.55
  5807.5  133.01  5874.3  133.81  6541.8  137.13  6839.8  132.95  7801.2  151.53
#Mann= 9 ,-1 , 0
  4179.2      .1       0  4784.4     .12       0    4815      .1       0
  5014.8     .07       0  5020.8      .1       0  5165.6     .12       0
  5807.5      .1       0  5874.3     .05       0  6541.8      .1       0
#XS Ineff= 2 ,-1
 6478.08 7055.16  137.94 7094.77 7315.42  139.07
Permanent Ineff=
       T       T
Bank Sta=4909.09,5685.3
XS Rating Curve= 0 ,0
Exp/Cntr=0.3,0.1

Type RM Length L Ch R = 1 ,4402    ,723,723,723
BEGIN DESCRIPTION:
Mapping XS c49f1211
END DESCRIPTION:
XS GIS Cut Line= 3
      2254832.41     13345908.65      2255136.22     13346570.53
       2256286.4     13347861.77
#Sta/Elev= 30
  3408.5  149.73  3766.5  132.42  4136.8  145.06  4439.9  134.32  4652.6  133.75
  4744.6  125.94  4835.1  123.54  4885.9  118.01  4928.5  119.83  4977.8  110.12
  4985.4  101.28  5003.3  100.18    5006   99.68  5009.3  100.18    5028   111.8
    5084  125.05  5091.5  125.32  5098.2  112.42  5112.5  110.95  5140.9  116.42
  5155.1  112.27  5233.3  127.03  5254.6  125.73  5261.3  131.28  5381.7  138.32
  5540.1  143.91  5679.7   147.1  5720.7  148.13  5823.8  150.01    5866  150.88
#Mann= 9 ,-1 , 0
  3408.5      .1       0  4835.1     .12       0  5003.3     .07       0
  5009.3     .12       0  5233.3      .1       0  5540.1     .05       0
  5679.7      .1       0  5720.7     .05       0  5823.8      .1       0
#XS Ineff= 1 ,-1
 3500.71 4120.23   144.3
Permanent Ineff=
       T
Bank Sta=4744.6,5084
XS Rating Curve= 0 ,0
Exp/Cntr=0.3,0.1

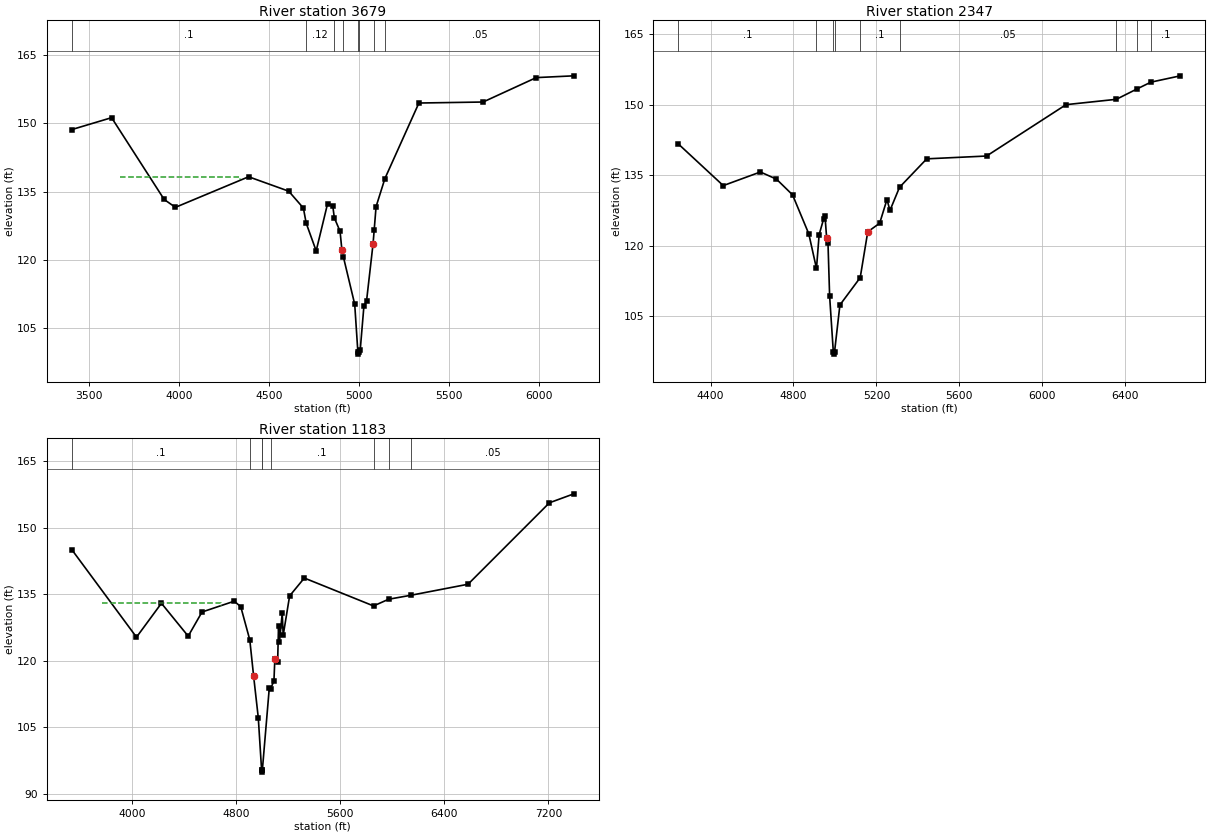
Type RM Length L Ch R = 1 ,3679    ,1332,1332,1332
BEGIN DESCRIPTION:
SULPHUR CREEK 6.0
END DESCRIPTION:
XS GIS Cut Line= 3
       2254745.6     13345778.43      2254886.65     13346711.59
       2255222.7      13348521.9
#Sta/Elev= 30
  3405.8  148.59  3626.7   151.2  3918.4  133.27  3980.7  131.55  4386.7  138.25
  4609.2  135.09  4690.6  131.39  4706.1  128.08  4761.5  122.01  4824.5  132.31
  4853.3  131.95  4862.2  129.25    4894   126.3  4904.1  122.21  4912.5  120.68
  4975.3   110.3  4992.7   99.88  4995.4   99.38  4998.7   99.88  5005.8  100.28
  5026.2  109.86  5040.9  111.03    5077  123.54  5083.2  126.54  5093.7  131.69
  5142.7  137.85  5331.3  154.41  5687.3  154.63  5982.2  159.98  6190.8  160.37
#Mann= 8 ,-1 , 0
  3405.8      .1       0  4706.1     .12       0  4862.2     .16       0
  4912.5     .12       0  4992.7     .07       0  4998.7     .12       0
  5083.2      .1       0  5142.7     .05       0
#XS Ineff= 1 ,-1
 3673.27 4341.58   138.1
Permanent Ineff=
       T
Bank Sta=4904.1,5077
XS Rating Curve= 0 ,0
Exp/Cntr=0.3,0.1

Type RM Length L Ch R = 1 ,2347    ,1164,1164,1164
BEGIN DESCRIPTION:
Mapping XS c931cd82
END DESCRIPTION:
XS GIS Cut Line= 3
        2254496.     13346038.88      2253660.53     13347069.66
      2253443.72     13348142.83
#Sta/Elev= 30
  4244.2  141.67  4461.4  132.78  4640.3  135.68  4717.9  134.16  4795.5  130.82
  4873.8  122.52    4911  115.13  4923.8  122.33  4945.7  125.73  4952.1  126.28
    4960  121.65  4966.5  120.59  4974.4  109.24  4992.2   97.39    4995   96.89
  4998.2   97.39    5024  107.36  5121.9  113.18  5158.3  122.94  5215.8  124.77
    5251  129.82  5265.4  127.49  5311.5  132.42  5442.8  138.48  5731.4  139.08
  6114.7  150.02  6357.5  151.16  6457.6  153.38  6523.8  154.81  6665.9  156.16
#Mann= 9 ,-1 , 0
  4244.2      .1       0    4911     .12       0  4992.2     .07       0
  4998.2     .12       0  5121.9      .1       0  5311.5     .05       0
  6357.5      .1       0  6457.6     .05       0  6523.8      .1       0
#XS Ineff= 1 ,-1
 4267.33 4649.22  135.36
Permanent Ineff=
       T
Bank Sta=4960,5158.3
XS Rating Curve= 0 ,0
Exp/Cntr=0.3,0.1

Type RM Length L Ch R = 1 ,1183    ,0,0,0
BEGIN DESCRIPTION:
SULPHUR CREEK 1.0
END DESCRIPTION:
XS GIS Cut Line= 3
      2254354.96     13344801.87      2252944.38     13346071.39
      2253193.83     13348012.79
#Sta/Elev= 30
  3539.8  145.08  4036.8  125.34  4228.2  132.98  4433.7  125.57  4539.9  131.01
  4787.3  133.45  4837.3  132.21  4906.7  124.73    4936  116.58  4971.9  107.19
  4997.3   95.42    5000   94.92  5003.3   95.42  5056.3  113.86  5066.4  113.64
  5092.2  115.55  5098.9  120.34  5120.6  119.83  5127.3  127.81  5134.8  124.35
  5155.7  130.73  5163.2  125.78  5212.5  134.64  5325.4  138.67  5856.9  132.38
  5972.9  133.89  6144.5  134.79  6582.3  137.27  7207.4  155.63  7394.9  157.65
#Mann= 8 ,-1 , 0
  3539.8      .1       0  4906.7     .12       0  4997.3     .07       0
  5003.3     .12       0  5066.4      .1       0  5856.9     .05       0
  5972.9      .1       0  6144.5     .05       0
#XS Ineff= 2 ,-1
 3770.86 4683.17  132.96 5340.88 6776.52  138.19
Permanent Ineff=
       T       T
Bank Sta=4936,5098.9
XS Rating Curve= 0 ,0
Exp/Cntr=0.3,0.1

Chan Stop Cuts=-1
Use User Specified Reach Order=0
Composite Channel Slope=5