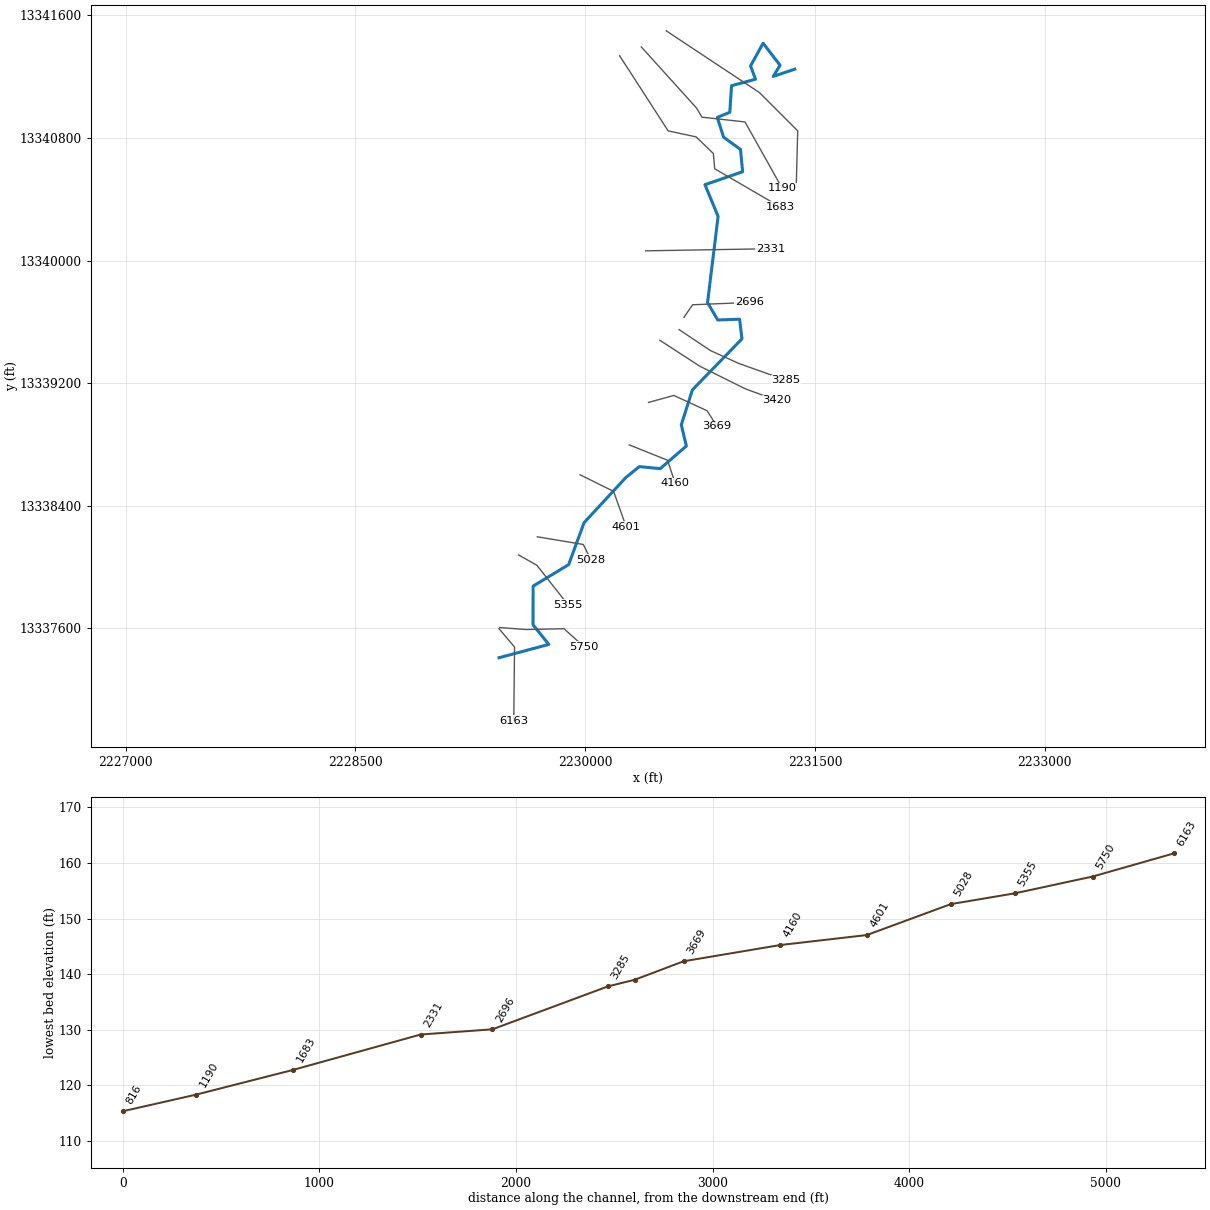
--- UNT002 IN SUCR.prj (project) ---

Proj Title=UNT002 IN SUCR Base Level Engineering
Current Plan=p01
Default Exp/Contr=0.3,0.1
English Units
Geom File=g01
Flow File=f01
Plan File=p01
BEGIN DESCRIPTION:
UNT002 IN SUCR
END DESCRIPTION:

--- UNT002 IN SUCR.p01 (plan) ---

Plan Title=Multiple Run
Short Identifier=Multiple
Geom File=g01
Flow File=f01
Subcritical Flow
K Sum by GR= 0
Std Step Tol= 0.01
Critical Tol= 0.01
Num of Std Step Trials= 20
Max Error Tol= 0.3
Flow Tol Ratio= 0.001
Split Flow NTrial= 30
Split Flow Tol= 0.02
Split Flow Ratio= 0.02
Log Output Level= 0
Friction Slope Method= 1
Unsteady Friction Slope Method= 2
Unsteady Bridges Friction Slope Method= 1
Parabolic Critical Depth
Global Vel Dist=  1 , 1 , 1
Global Log Level= 0
CheckData=True
Encroach Param= -1, 0, 0, 0
BEGIN DESCRIPTION:
Multiple Run
END DESCRIPTION:

--- UNT002 IN SUCR.f01 (steady flow) ---

Flow Title=Multiple
Number of Profiles=7
Profile Names=10-year,25-year,50-year,1pct_min,100-year,1pct_plu,500-year
River Rch & RM= UNT002 IN SUCR,Reach-1,6163
     210     291     358     325     440     595     672
River Rch & RM= UNT002 IN SUCR,Reach-1,4160
     296     418     522     480     649     877    1016
Boundary for River Rch & Prof#=UNT002 IN SUCR,Reach-1,1
Up Type=0
Dn Type=3
Dn Slope=0.005
Boundary for River Rch & Prof#=UNT002 IN SUCR,Reach-1,2
Up Type=0
Dn Type=3
Dn Slope=0.005
Boundary for River Rch & Prof#=UNT002 IN SUCR,Reach-1,3
Up Type=0
Dn Type=3
Dn Slope=0.005
Boundary for River Rch & Prof#=UNT002 IN SUCR,Reach-1,4
Up Type=0
Dn Type=3
Dn Slope=0.005
Boundary for River Rch & Prof#=UNT002 IN SUCR,Reach-1,5
Up Type=0
Dn Type=3
Dn Slope=0.005
Boundary for River Rch & Prof#=UNT002 IN SUCR,Reach-1,6
Up Type=0
Dn Type=3
Dn Slope=0.005
Boundary for River Rch & Prof#=UNT002 IN SUCR,Reach-1,7
Up Type=0
Dn Type=3
Dn Slope=0.005

--- UNT002 IN SUCR.g01 (geometry) ---

Geom Title=Existing Conditions

River Reach=UNT002 IN SUCR,Reach-1
Reach XY= 30
      2229437.64     13337407.24      2229762.87     13337494.47
      2229659.62     13337622.47      2229660.52     13337874.96
      2229892.45     13338015.19      2229993.07     13338289.12
      2230268.12     13338586.19      2230353.64     13338654.91
      2230490.18     13338641.87      2230660.86     13338789.48
      2230627.56     13338927.69      2230700.19     13339155.91
      2231023.83     13339489.05      2231008.30     13339617.41
      2230865.36     13339612.32      2230799.03     13339725.85
      2230868.00     13340288.32      2230782.35     13340495.42
      2231028.16     13340580.18      2231014.24     13340725.45
      2230903.81     13340805.51      2230862.74     13340934.95
      2230944.37     13340967.91      2230955.74     13341141.77
      2231112.36     13341184.14      2231080.02     13341270.78
      2231161.77     13341419.30      2231272.51     13341274.88
      2231227.75     13341202.18      2231368.36     13341249.50

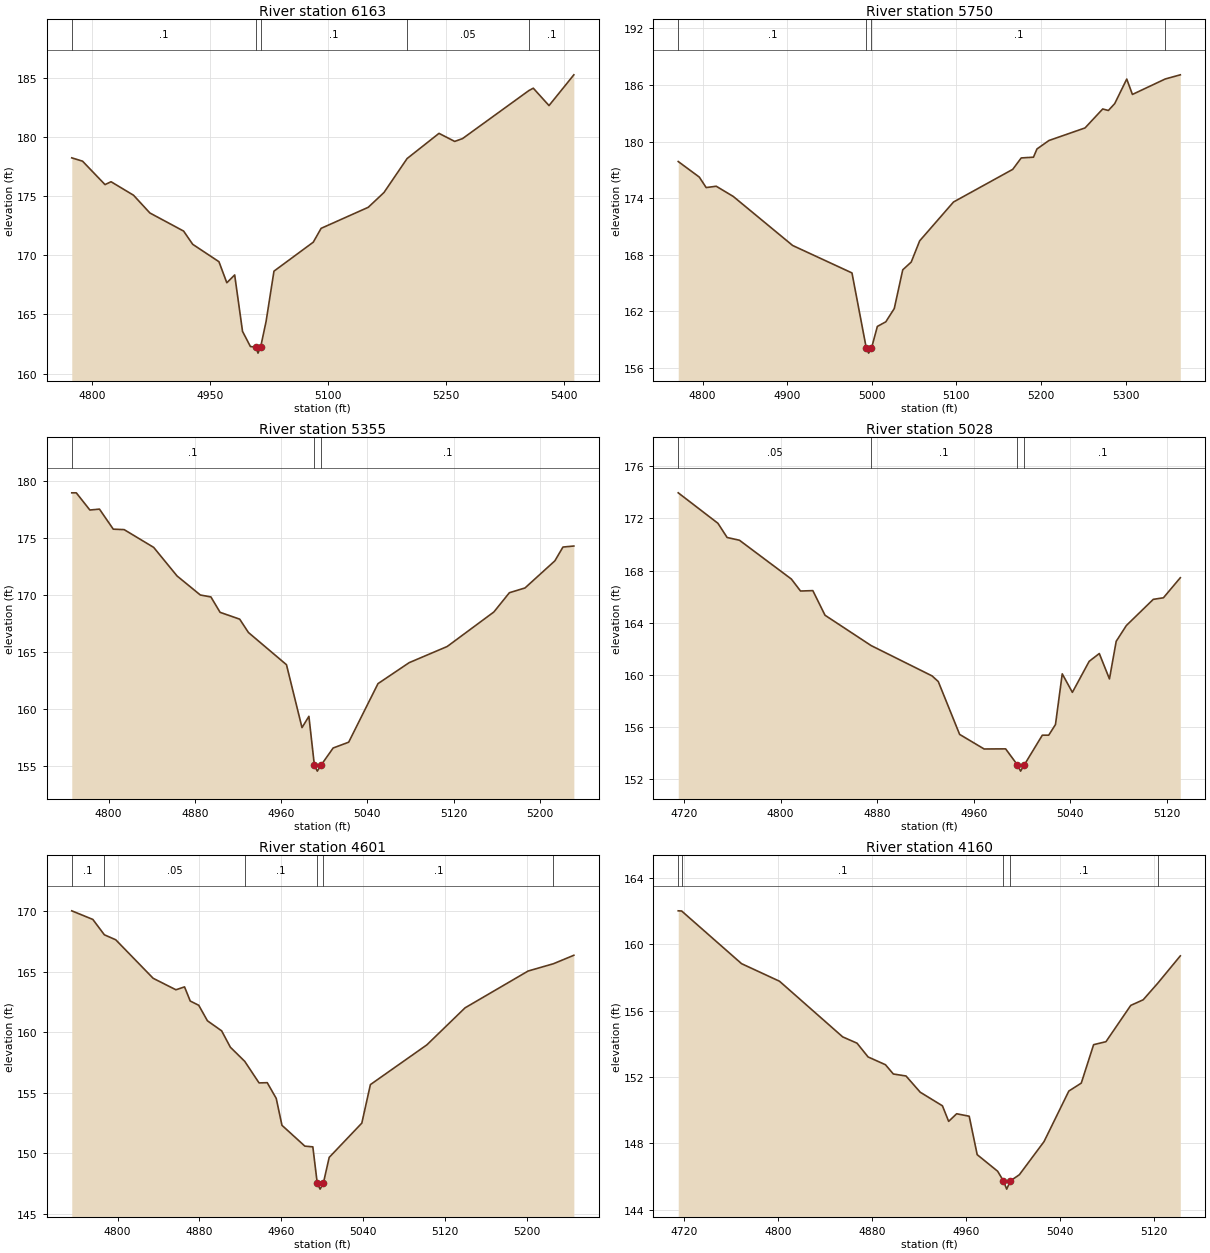
Type RM Length L Ch R = 1,6163,413,413,413
BEGIN DESCRIPTION:
UNT002 IN SUCR 12.0
END DESCRIPTION:
XS GIS Cut Line= 3
      2229437.71     13337596.87      2229539.26     13337477.03
      2229534.05     13336995.23
#Sta/Elev= 30
  4773.9  178.24  4787.6  177.96  4816.2  175.98  4823.9  176.22  4852.5  175.08
  4873.3  173.58  4916.2  172.05  4927.8  170.93  4961.2  169.46  4971.2  167.68
  4981.2  168.34  4991.2  163.57  5001.2  162.29  5008.2  162.23  5010.9  161.73
  5014.2  162.23  5021.2  164.42  5031.2  168.66  5081.2  171.11  5091.2  172.28
  5151.2  174.06  5171.2  175.31  5200.6  178.18  5241.2  180.31  5261.2  179.63
  5271.2  179.87  5355.6  183.93  5361.2  184.13  5381.2  182.66  5412.8  185.26
#Mann=5,-1,0
  4773.9     0.1       0  5008.2    0.07       0  5014.2     0.1       0
  5200.6    0.05       0  5355.6     0.1       0
Bank Sta=5008.2,5014.2
Exp/Cntr=0.3,0.1

Type RM Length L Ch R = 1,5750,395,395,395
BEGIN DESCRIPTION:
Mapping XS b4f75290
END DESCRIPTION:
XS GIS Cut Line= 4
      2229442.94     13337604.63      2229612.17     13337591.61
      2229862.17     13337596.82      2229991.14     13337480.75
#Sta/Elev= 30
  4771.3  177.88  4796.2  176.23  4804.3  175.12  4816.2  175.26  4836.3  174.18
  4906.5  168.98  4976.6  166.07  4993.6  158.07  4996.3  157.57  4999.6  158.07
  5006.6  160.40  5016.6  160.89  5026.6  162.30  5036.6  166.40  5046.6  167.22
  5056.6  169.47  5096.6  173.59  5166.6  177.05  5176.6  178.26  5191.1  178.34
  5195.2  179.21  5209.4  180.11  5252.0  181.44  5272.9  183.45  5279.6  183.29
  5287.1  184.02  5301.3  186.62  5308.0  184.99  5346.8  186.63  5364.6  187.07
#Mann=4,-1,0
  4771.3     0.1       0  4993.6    0.07       0  4999.6     0.1       0
  5346.8    0.05       0
Bank Sta=4993.6,4999.6
Exp/Cntr=0.3,0.1

Type RM Length L Ch R = 1,5355,327,327,327
BEGIN DESCRIPTION:
UNT002 IN SUCR 11.0
END DESCRIPTION:
XS GIS Cut Line= 3
      2229565.34     13338078.57      2229685.09     13338010.88
      2229888.23     13337753.05
#Sta/Elev= 30
  4765.8  178.98  4770.0  178.98  4782.6  177.47  4791.5  177.55  4804.3  175.79
  4814.4  175.75  4841.8  174.19  4863.5  171.68  4885.1  170.01  4894.9  169.84
  4903.4  168.49  4921.6  167.89  4929.7  166.72  4965.0  163.89  4979.4  158.37
  4985.8  159.36  4990.9  155.05  4993.6  154.55  4996.9  155.05  5008.3  156.58
  5022.7  157.09  5049.9  162.23  5078.8  164.07  5114.1  165.49  5157.4  168.52
  5171.8  170.21  5186.3  170.63  5214.0  173.01  5221.5  174.22  5231.6  174.31
#Mann=3,-1,0
  4765.8     0.1       0  4990.9    0.07       0  4996.9     0.1       0
Bank Sta=4990.9,4996.9
Exp/Cntr=0.3,0.1

Type RM Length L Ch R = 1,5028,427,427,427
BEGIN DESCRIPTION:
UNT002 IN SUCR 10.0
END DESCRIPTION:
XS GIS Cut Line= 3
      2229687.75     13338196.85      2229987.72     13338146.85
      2230037.72     13338046.86
#Sta/Elev= 30
  4715.2  173.97  4748.1  171.63  4755.7  170.54  4765.9  170.33  4808.9  167.35
  4816.5  166.43  4826.7  166.46  4836.8  164.57  4875.0  162.24  4925.5  159.91
  4930.6  159.48  4948.3  155.42  4968.6  154.30  4986.4  154.31  4996.0  153.10
  4998.8  152.60  5002.0  153.10  5016.8  155.36  5022.1  155.36  5027.7  156.18
  5033.3  160.07  5041.7  158.65  5055.6  161.03  5064.0  161.63  5072.4  159.68
  5078.0  162.57  5086.4  163.78  5108.7  165.79  5117.1  165.91  5131.1  167.45
#Mann=4,-1,0
  4715.2    0.05       0  4875.0     0.1       0  4996.0    0.07       0
  5002.0     0.1       0
Bank Sta=4996,5002
Exp/Cntr=0.3,0.1

Type RM Length L Ch R = 1,4601,441,441,441
BEGIN DESCRIPTION:
UNT002 IN SUCR 9.0
END DESCRIPTION:
XS GIS Cut Line= 3
      2229966.38     13338602.01      2230185.86     13338493.38
      2230268.25     13338261.37
#Sta/Elev= 30
  4755.1  170.01  4775.7  169.30  4787.0  168.03  4798.1  167.62  4834.7  164.44
  4857.0  163.49  4865.4  163.73  4871.0  162.56  4879.3  162.21  4887.8  160.93
  4901.7  160.10  4910.2  158.75  4924.3  157.58  4938.3  155.80  4946.3  155.82
  4955.1  154.52  4960.7  152.30  4983.1  150.58  4990.9  150.52  4995.2  147.53
  4998.0  147.03  5001.2  147.53  5006.9  149.65  5038.8  152.48  5047.2  155.66
  5102.4  158.94  5139.8  162.00  5201.5  165.04  5226.2  165.64  5246.2  166.34
#Mann=6,-1,0
  4755.1     0.1       0  4787.0    0.05       0  4924.3     0.1       0
  4995.2    0.07       0  5001.2     0.1       0  5226.2    0.05       0
Bank Sta=4995.2,5001.2
Exp/Cntr=0.3,0.1

Type RM Length L Ch R = 1,4160,491,491,491
BEGIN DESCRIPTION:
UNT002 IN SUCR 8.0
END DESCRIPTION:
XS GIS Cut Line= 3
      2230287.70     13338796.86      2230537.72     13338696.85
      2230587.72     13338546.85
#Sta/Elev= 30
  4715.1  162.03  4718.0  162.02  4769.0  158.84  4801.3  157.78  4855.1  154.42
  4867.3  154.04  4876.7  153.21  4891.5  152.74  4898.2  152.18  4909.0  152.06
  4921.1  151.08  4940.0  150.26  4945.3  149.32  4952.1  149.78  4962.8  149.63
  4969.6  147.31  4987.0  146.31  4991.9  145.73  4994.7  145.23  4997.9  145.73
  5005.5  146.10  5026.5  148.10  5047.6  151.15  5058.2  151.63  5068.7  153.95
  5079.2  154.13  5100.3  156.32  5110.9  156.66  5123.3  157.66  5142.5  159.31
#Mann=5,-1,0
  4715.1    0.05       0  4718.0     0.1       0  4991.9    0.07       0
  4997.9     0.1       0  5123.3    0.05       0
Bank Sta=4991.9,4997.9
Exp/Cntr=0.3,0.1

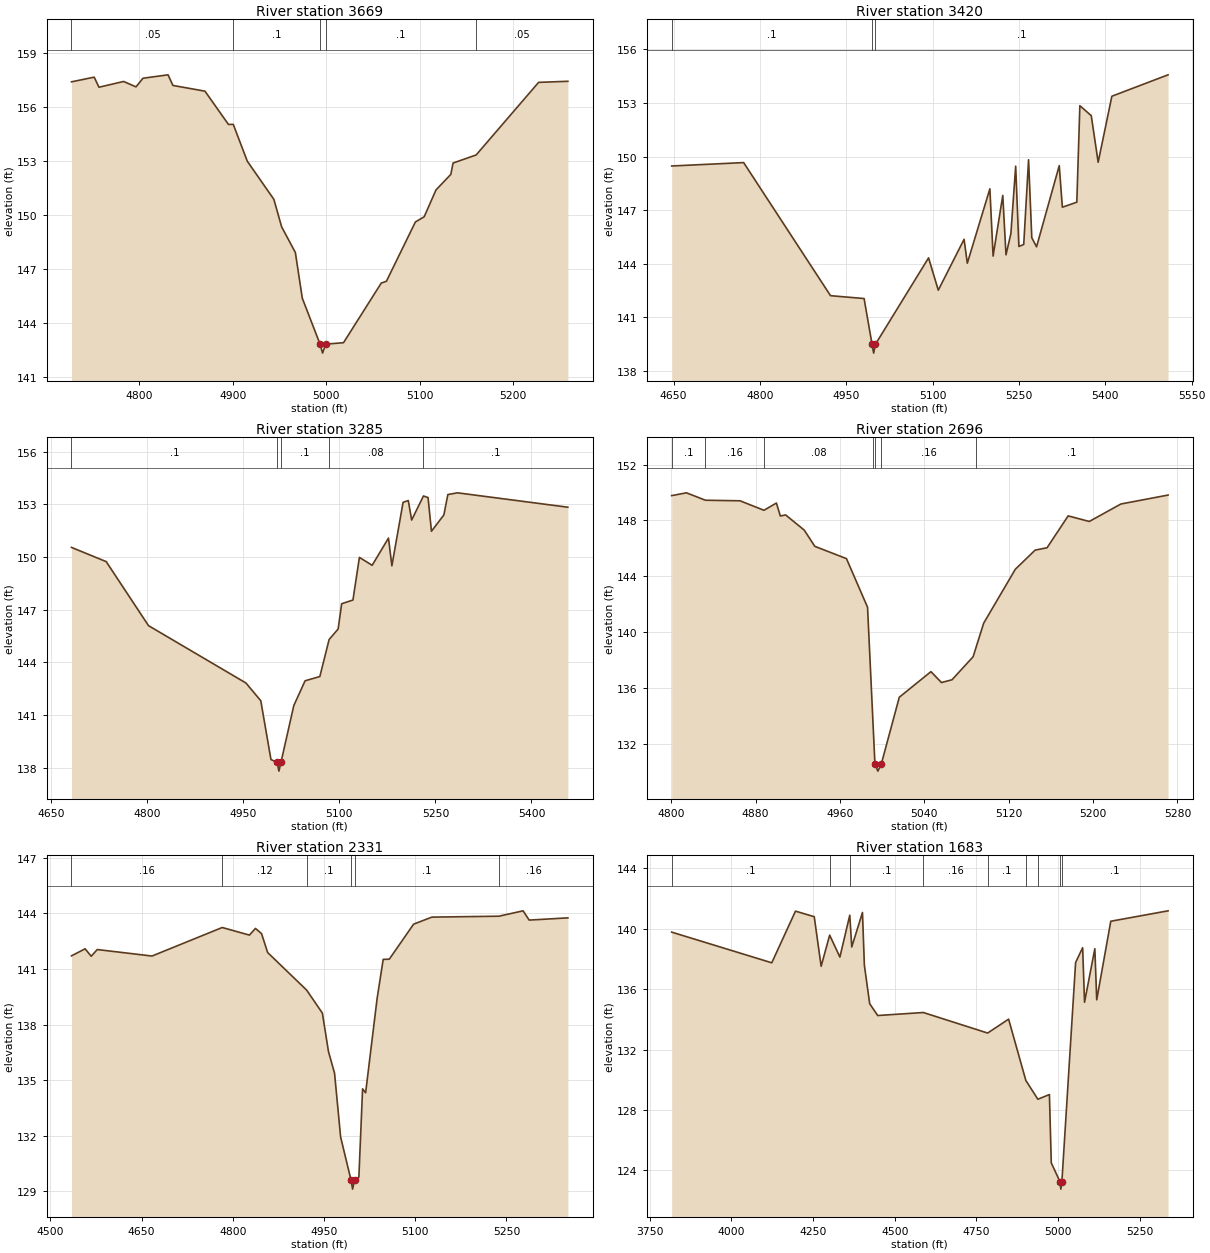
Type RM Length L Ch R = 1,3669,249,249,249
BEGIN DESCRIPTION:
UNT002 IN SUCR 7.0
END DESCRIPTION:
XS GIS Cut Line= 4
      2230413.98     13339074.11      2230578.90     13339119.68
      2230795.91     13339019.85      2230861.03     13338917.83
#Sta/Elev= 30
  4727.6  157.41  4751.9  157.67  4757.0  157.11  4783.4  157.43  4796.6  157.13
  4804.1  157.61  4830.9  157.80  4836.1  157.21  4870.4  156.89  4895.5  155.04
  4900.7  155.04  4915.7  152.99  4944.1  150.87  4952.4  149.34  4967.1  147.91
  4974.5  145.37  4993.5  142.81  4996.2  142.31  4999.5  142.81  5018.6  142.89
  5059.0  146.21  5064.5  146.31  5095.5  149.61  5104.9  149.90  5117.5  151.39
  5133.4  152.26  5135.8  152.89  5160.5  153.34  5227.3  157.38  5258.6  157.44
#Mann=5,-1,0
  4727.6    0.05       0  4900.7     0.1       0  4993.5    0.07       0
  4999.5     0.1       0  5160.5    0.05       0
Bank Sta=4993.5,4999.5
Exp/Cntr=0.3,0.1

Type RM Length L Ch R = 1,3420,135,135,135
BEGIN DESCRIPTION:
Mapping XS 0ac49da3
END DESCRIPTION:
XS GIS Cut Line= 4
      2230487.77     13339479.91      2230748.17     13339310.65
      2231045.48     13339163.08      2231251.64     13339087.13
#Sta/Elev= 30
  4646.8  149.47  4771.8  149.66  4922.7  142.20  4981.0  142.04  4994.8  139.48
  4997.6  138.98  5000.8  139.48  5093.0  144.32  5109.9  142.51  5154.7  145.36
  5160.3  144.02  5199.5  148.19  5205.1  144.42  5221.9  147.82  5227.5  144.49
  5236.0  145.68  5244.3  149.46  5249.9  144.96  5258.3  145.07  5266.7  149.82
  5272.3  145.45  5280.6  144.94  5320.0  149.49  5325.4  147.16  5350.5  147.44
  5355.8  152.85  5375.6  152.29  5387.6  149.68  5411.4  153.38  5509.0  154.58
#Mann=3,-1,0
  4646.8     0.1       0  4994.8    0.07       0  5000.8     0.1       0
Bank Sta=4994.8,5000.8
Exp/Cntr=0.3,0.1

Type RM Length L Ch R = 1,3285,589,589,589
BEGIN DESCRIPTION:
UNT002 IN SUCR 6.0
END DESCRIPTION:
XS GIS Cut Line= 4
      2230613.64     13339549.35      2230817.58     13339412.83
      2231004.25     13339328.01      2231310.23     13339219.51
#Sta/Elev= 30
  4681.7  150.55  4735.9  149.74  4802.0  146.09  4954.2  142.82  4977.3  141.81
  4993.2  138.46  5002.8  138.30  5005.6  137.80  5008.8  138.30  5028.9  141.54
  5046.5  142.95  5069.5  143.19  5084.0  145.30  5098.1  145.90  5103.6  147.34
  5121.2  147.55  5131.3  149.98  5151.2  149.53  5176.7  151.08  5182.0  149.50
  5199.5  153.12  5207.6  153.22  5212.9  152.11  5231.3  153.48  5238.5  153.39
  5243.8  151.47  5263.2  152.40  5269.4  153.56  5284.4  153.66  5456.8  152.84
#Mann=5,-1,0
  4681.7     0.1       0  5002.8    0.07       0  5008.8     0.1       0
  5084.0    0.08       0  5231.3     0.1       0
Bank Sta=5002.8,5008.8
Exp/Cntr=0.3,0.1

Type RM Length L Ch R = 1,2696,365,365,365
BEGIN DESCRIPTION:
UNT002 IN SUCR 5.0
END DESCRIPTION:
XS GIS Cut Line= 3
      2230645.30     13339629.66      2230701.35     13339711.61
      2231072.35     13339726.88
#Sta/Elev= 30
  4800.5  149.78  4814.5  149.98  4832.5  149.45  4865.3  149.41  4888.0  148.73
  4899.8  149.25  4903.5  148.32  4908.5  148.40  4926.2  147.31  4936.2  146.15
  4966.2  145.27  4986.2  141.79  4991.1  133.93  4993.2  130.56  4996.0  130.06
  4999.2  130.56  5016.3  135.35  5046.3  137.18  5056.3  136.40  5066.3  136.60
  5086.3  138.25  5089.2  138.95  5096.3  140.65  5126.3  144.51  5145.1  145.88
  5156.4  146.05  5176.4  148.33  5196.4  147.93  5226.4  149.18  5271.1  149.82
#Mann=7,-1,0
  4800.5     0.1       0  4832.5    0.16       0  4888.0    0.08       0
  4991.1    0.16       0  4993.2    0.07       0  4999.2    0.16       0
  5089.2     0.1       0
Bank Sta=4993.2,4999.2
Exp/Cntr=0.3,0.1

Type RM Length L Ch R = 1,2331,648,648,648
BEGIN DESCRIPTION:
UNT002 IN SUCR 4.0
END DESCRIPTION:
XS GIS Cut Line= 2
      2230395.29     13340063.69      2231211.27     13340077.58
#Sta/Elev= 30
  4534.8  141.71  4557.2  142.09  4567.2  141.69  4577.2  142.05  4667.2  141.70
  4782.7  143.24  4827.3  142.83  4837.3  143.19  4847.3  142.91  4857.3  141.89
  4921.5  139.86  4947.3  138.62  4957.3  136.55  4967.3  135.38  4977.3  131.93
  4994.3  129.62  4997.0  129.12  5000.3  129.62  5007.3  129.77  5013.4  134.53
  5018.4  134.32  5037.3  139.41  5047.3  141.52  5057.3  141.53  5097.3  143.42
  5127.3  143.80  5237.5  143.85  5277.3  144.14  5287.3  143.64  5350.9  143.76
#Mann=6,-1,0
  4534.8    0.16       0  4782.7    0.12       0  4921.5     0.1       0
  4994.3    0.07       0  5000.3     0.1       0  5237.5    0.16       0
Bank Sta=4994.3,5000.3
Exp/Cntr=0.3,0.1

Type RM Length L Ch R = 1,1683,493,493,493
BEGIN DESCRIPTION:
UNT002 IN SUCR 3.0
END DESCRIPTION:
XS GIS Cut Line= 6
      2230225.17     13341337.12      2230542.01     13340846.68
      2230724.30     13340807.61      2230837.14     13340699.11
      2230845.83     13340599.28      2231271.14     13340351.90
#Sta/Elev= 30
  3817.5  139.77  4123.8  137.74  4196.4  141.16  4253.8  140.79  4274.9  137.51
  4301.0  139.57  4332.3  138.12  4362.5  140.89  4368.6  138.79  4401.4  141.07
  4407.2  137.58  4423.5  135.03  4448.1  134.25  4587.6  134.45  4784.5  133.09
  4848.6  134.01  4901.4  129.95  4938.2  128.71  4973.5  129.02  4979.2  124.50
  5005.7  123.26  5008.5  122.76  5011.7  123.26  5053.7  137.76  5075.2  138.74
  5081.0  135.13  5112.5  138.67  5118.3  135.29  5161.3  140.49  5336.6  141.18
#Mann=9,-1,0
  3817.5     0.1       0  4301.0    0.12       0  4362.5     0.1       0
  4587.6    0.16       0  4784.5     0.1       0  4901.4    0.16       0
  4938.2     0.1       0  5005.7    0.07       0  5011.7     0.1       0
Bank Sta=5005.7,5011.7
Exp/Cntr=0.3,0.1

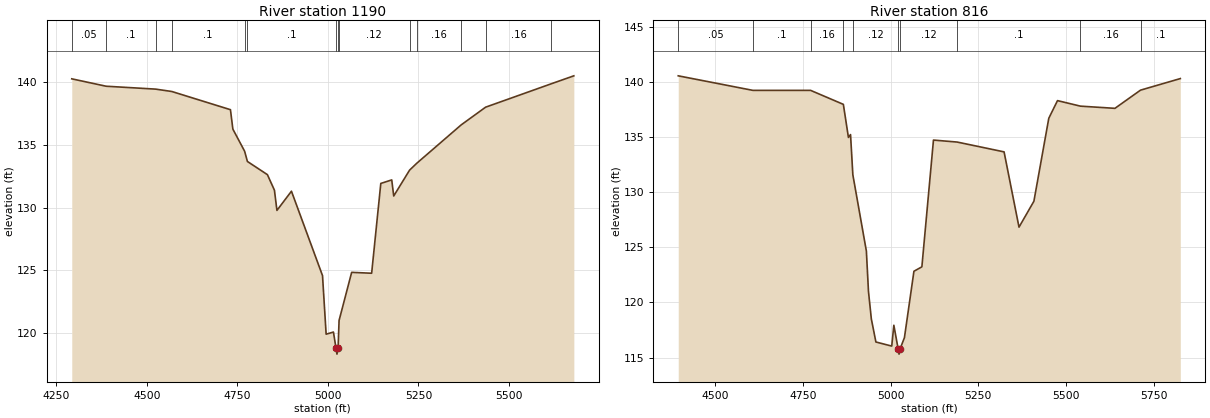
Type RM Length L Ch R = 1,1190,374,374,374
BEGIN DESCRIPTION:
UNT002 IN SUCR 2.0
END DESCRIPTION:
XS GIS Cut Line= 5
      2230366.68     13341394.62      2230727.77     13340995.33
      2230762.49     13340936.30      2231043.74     13340905.05
      2231286.57     13340471.43
#Sta/Elev= 30
  4292.3  140.26  4387.3  139.67  4523.9  139.44  4568.7  139.25  4730.6  137.80
  4737.3  136.25  4769.7  134.49  4777.5  133.67  4832.7  132.62  4852.1  131.38
  4859.0  129.77  4899.1  131.30  4984.9  124.57  4994.9  119.90  5015.1  120.07
  5022.0  118.81  5024.8  118.31  5028.0  118.81  5030.6  120.99  5065.4  124.83
  5120.6  124.76  5145.9  131.92  5176.1  132.20  5181.6  130.92  5225.4  132.98
  5245.3  133.53  5368.0  136.59  5435.4  138.00  5617.2  139.87  5679.1  140.50
#Mann=14,-1,0
  4292.3    0.05       0  4387.3     0.1       0  4523.9    0.05       0
  4568.7     0.1       0  4769.7    0.12       0  4777.5     0.1       0
  5022.0    0.07       0  5028.0     0.1       0  5030.6    0.12       0
  5225.4     0.1       0  5245.3    0.16       0  5368.0     0.1       0
  5435.4    0.16       0  5617.2     0.1       0
Bank Sta=5022,5028
Exp/Cntr=0.3,0.1

Type RM Length L Ch R = 1,816,0,0,0
BEGIN DESCRIPTION:
UNT002 IN SUCR 1.0
END DESCRIPTION:
XS GIS Cut Line= 4
      2230529.48     13341499.86      2231137.72     13341096.85
      2231387.72     13340846.85      2231378.49     13340500.87
#Sta/Elev= 30
  4395.6  140.56  4608.2  139.24  4772.5  139.24  4865.7  137.97  4880.1  134.97
  4886.1  135.23  4892.7  131.58  4931.2  124.66  4937.2  120.99  4945.3  118.51
  4958.3  116.41  5003.4  116.04  5009.4  117.93  5021.5  115.81  5024.2  115.31
  5027.5  115.81  5039.5  116.80  5066.6  122.83  5089.2  123.23  5122.2  134.73
  5189.8  134.55  5323.2  133.66  5365.7  126.83  5408.1  129.18  5450.5  136.71
  5475.3  138.31  5540.4  137.81  5638.8  137.61  5711.6  139.26  5824.9  140.31
#Mann=10,-1,0
  4395.6    0.05       0  4608.2     0.1       0  4772.5    0.16       0
  4865.7     0.1       0  4892.7    0.12       0  5021.5    0.07       0
  5027.5    0.12       0  5189.8     0.1       0  5540.4    0.16       0
  5711.6     0.1       0
Bank Sta=5021.5,5027.5
Exp/Cntr=0.3,0.1

Chan Stop Cuts=-1