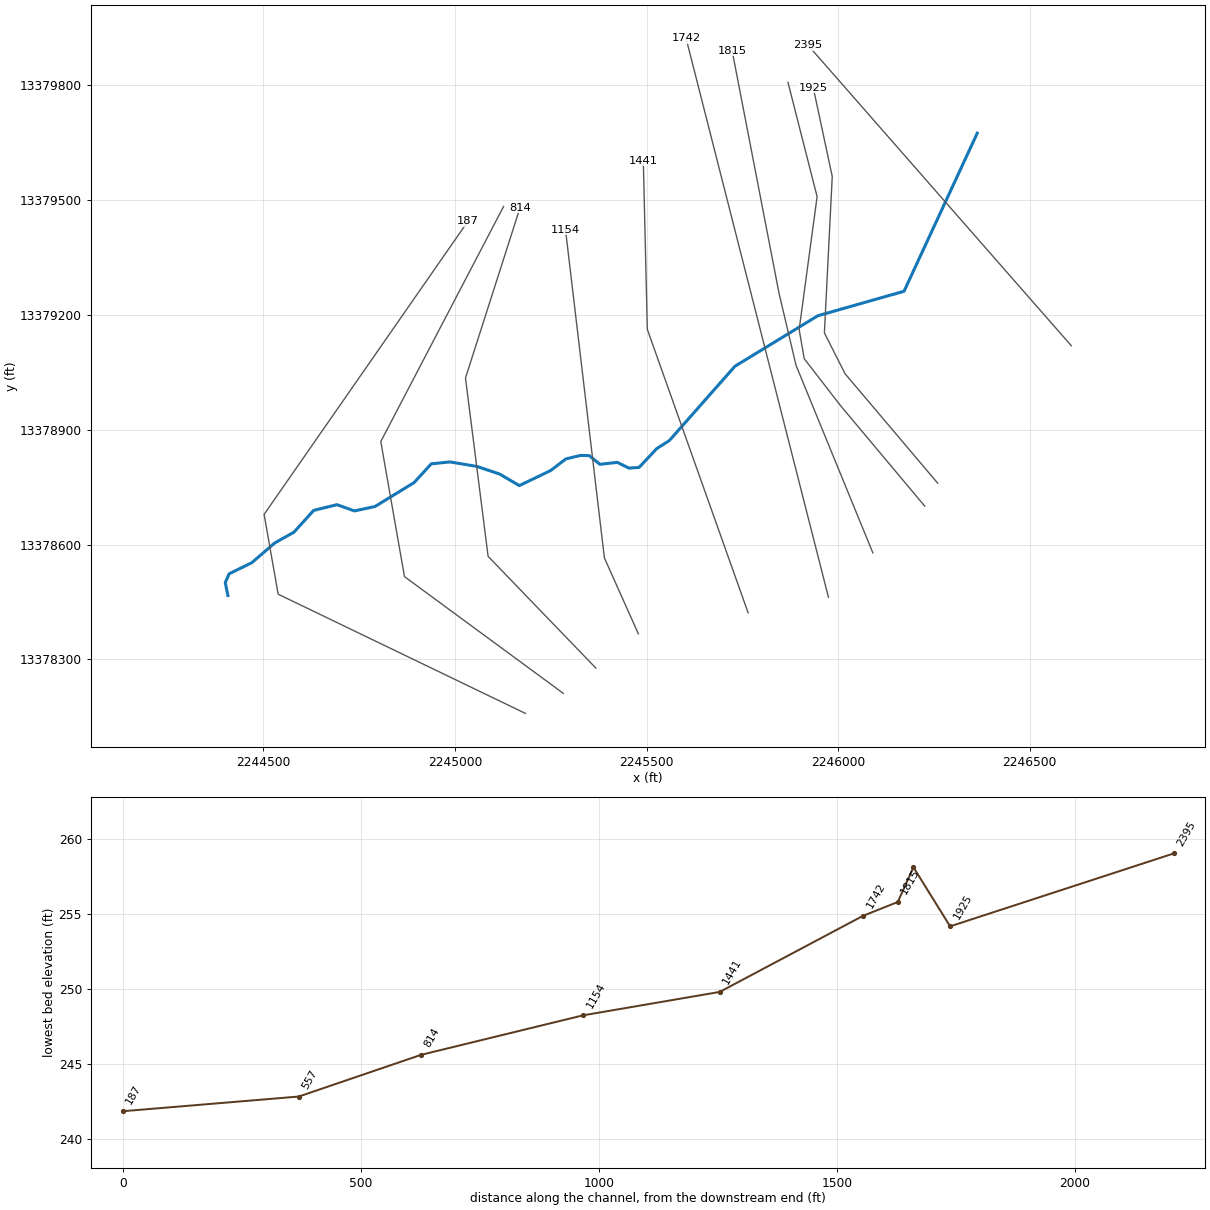
--- UNT004 IN SUCR.prj (project) ---

Proj Title=UNT004 IN SUCR Base Level Engineering
Current Plan=p01
Default Exp/Contr=0.3,0.1
English Units
Geom File=g01
Flow File=f01
Plan File=p01
BEGIN DESCRIPTION:
UNT004 IN SUCR
END DESCRIPTION:

--- UNT004 IN SUCR.p01 (plan) ---

Plan Title=Multiple Run
Short Identifier=Multiple
Geom File=g01
Flow File=f01
Subcritical Flow
K Sum by GR= 0
Std Step Tol= 0.01
Critical Tol= 0.01
Num of Std Step Trials= 20
Max Error Tol= 0.3
Flow Tol Ratio= 0.001
Split Flow NTrial= 30
Split Flow Tol= 0.02
Split Flow Ratio= 0.02
Log Output Level= 0
Friction Slope Method= 1
Unsteady Friction Slope Method= 2
Unsteady Bridges Friction Slope Method= 1
Parabolic Critical Depth
Global Vel Dist=  1 , 1 , 1
Global Log Level= 0
CheckData=True
Encroach Param= -1, 0, 0, 0
BEGIN DESCRIPTION:
Multiple Run
END DESCRIPTION:

--- UNT004 IN SUCR.f01 (steady flow) ---

Flow Title=Multiple
Number of Profiles=7
Profile Names=10-year,25-year,50-year,1pct_min,100-year,1pct_plu,500-year
River Rch & RM= UNT004 IN SUCR,Reach-1,2395
     183     249     303     271     367     496     545
Boundary for River Rch & Prof#=UNT004 IN SUCR,Reach-1,1
Up Type=0
Dn Type=3
Dn Slope=0.005
Boundary for River Rch & Prof#=UNT004 IN SUCR,Reach-1,2
Up Type=0
Dn Type=3
Dn Slope=0.005
Boundary for River Rch & Prof#=UNT004 IN SUCR,Reach-1,3
Up Type=0
Dn Type=3
Dn Slope=0.005
Boundary for River Rch & Prof#=UNT004 IN SUCR,Reach-1,4
Up Type=0
Dn Type=3
Dn Slope=0.005
Boundary for River Rch & Prof#=UNT004 IN SUCR,Reach-1,5
Up Type=0
Dn Type=3
Dn Slope=0.005
Boundary for River Rch & Prof#=UNT004 IN SUCR,Reach-1,6
Up Type=0
Dn Type=3
Dn Slope=0.005
Boundary for River Rch & Prof#=UNT004 IN SUCR,Reach-1,7
Up Type=0
Dn Type=3
Dn Slope=0.005

--- UNT004 IN SUCR.g01 (geometry) ---

Geom Title=Existing Conditions

River Reach=UNT004 IN SUCR,Reach-1
Reach XY= 30
      2246362.82     13379673.01      2246171.85     13379260.68
      2245946.90     13379196.85      2245730.57     13379065.00
      2245559.55     13378871.21      2245526.72     13378850.30
      2245480.52     13378801.08      2245454.30     13378799.31
      2245423.71     13378814.26      2245378.43     13378809.23
      2245350.35     13378831.90      2245327.46     13378832.34
      2245289.51     13378823.26      2245249.90     13378792.99
      2245168.06     13378753.67      2245116.65     13378783.86
      2245056.46     13378803.92      2244987.14     13378815.44
      2244938.39     13378810.50      2244893.64     13378761.57
      2244791.34     13378699.01      2244737.82     13378687.60
      2244692.41     13378703.90      2244631.61     13378688.99
      2244580.01     13378632.11      2244529.63     13378603.80
      2244470.04     13378552.53      2244410.89     13378523.45
      2244400.87     13378500.65      2244407.72     13378466.86

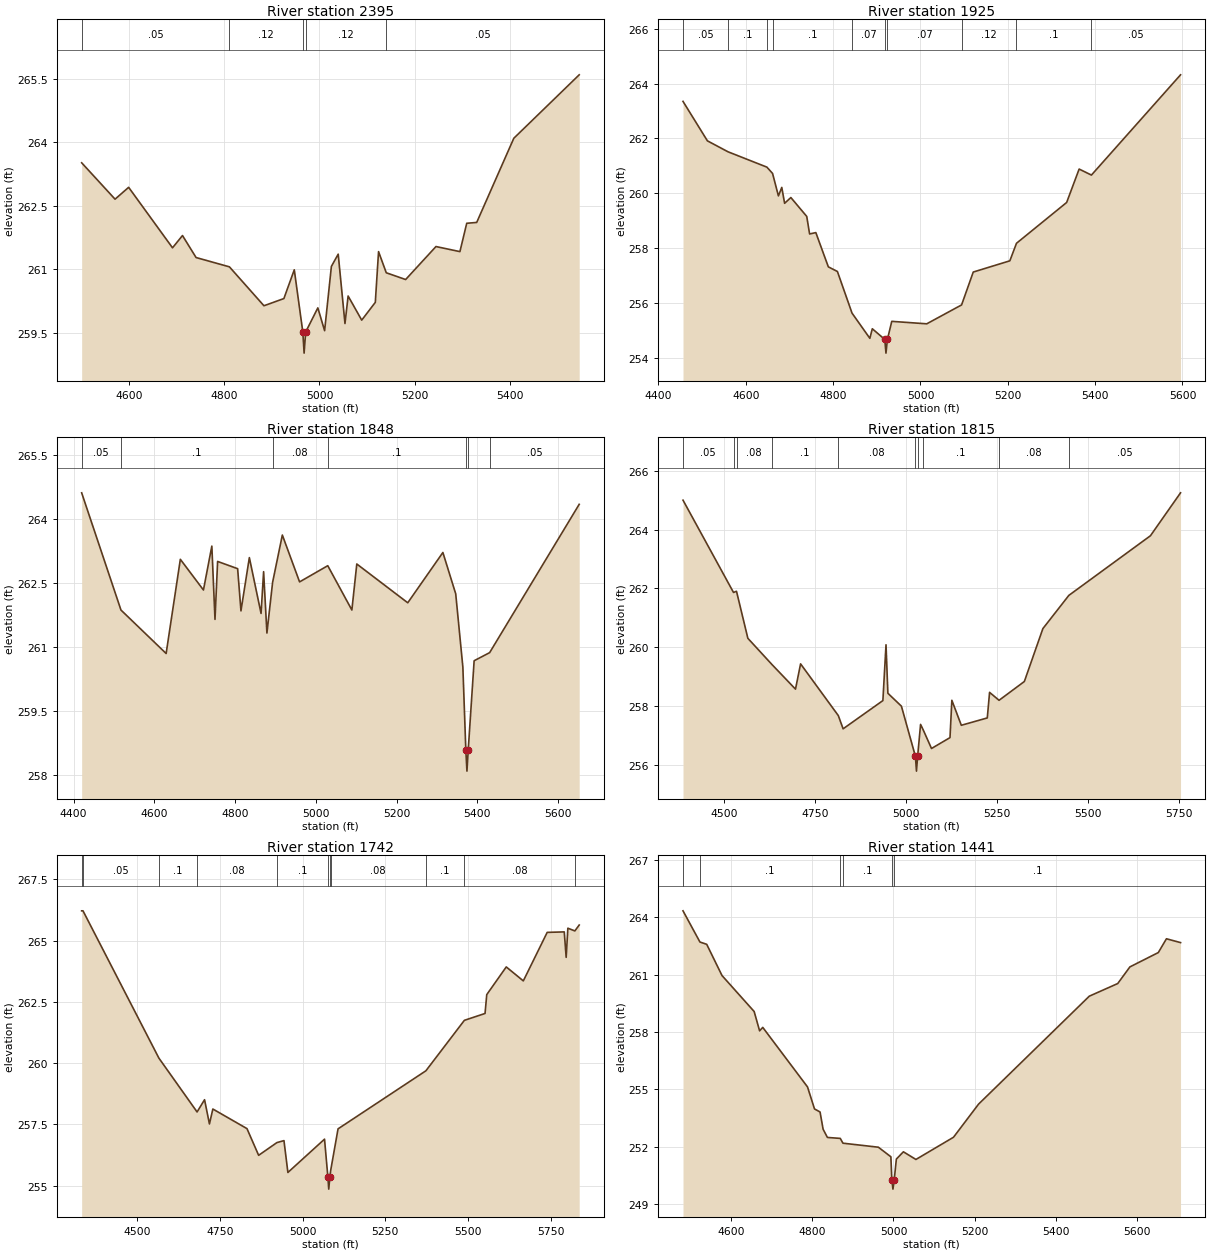
Type RM Length L Ch R = 1,2395,470,470,470
BEGIN DESCRIPTION:
UNT004 IN SUCR 4.0
END DESCRIPTION:
XS GIS Cut Line= 2
      2246608.31     13379118.62      2245920.87     13379903.28
#Sta/Elev= 30
  4501.4  263.52  4571.4  262.66  4599.9  262.94  4691.9  261.51  4712.8  261.80
  4741.3  261.28  4811.2  261.06  4883.6  260.14  4925.4  260.31  4947.2  260.99
  4965.1  259.52  4967.8  259.02  4971.1  259.52  4996.6  260.09  5010.8  259.55
  5025.0  261.07  5039.3  261.36  5053.5  259.72  5060.1  260.37  5088.6  259.80
  5117.1  260.22  5123.9  261.42  5140.1  260.92  5180.7  260.76  5244.3  261.54
  5294.5  261.42  5308.8  262.09  5329.7  262.11  5407.5  264.10  5544.6  265.60
#Mann=5,-1,0
  4501.4    0.05       0  4811.2    0.12       0  4965.1    0.07       0
  4971.1    0.12       0  5140.1    0.05       0
Bank Sta=4965.1,4971.1
Exp/Cntr=0.3,0.1

Type RM Length L Ch R = 1,1925,77,77,77
BEGIN DESCRIPTION:
Mapping XS 6906184a
END DESCRIPTION:
XS GIS Cut Line= 5
      2246259.57     13378760.06      2246018.19     13379045.32
      2245964.07     13379152.11      2245984.55     13379560.24
      2245934.92     13379792.35
#Sta/Elev= 30
  4456.2  263.35  4512.1  261.91  4559.3  261.51  4648.3  260.95  4661.3  260.72
  4674.7  259.90  4682.4  260.21  4688.9  259.63  4703.2  259.84  4739.6  259.15
  4746.1  258.51  4760.4  258.56  4789.0  257.31  4809.8  257.14  4843.3  255.62
  4884.1  254.70  4889.7  255.05  4918.3  254.66  4921.0  254.16  4924.3  254.66
  4934.3  255.32  5014.4  255.23  5094.2  255.92  5120.9  257.12  5204.7  257.53
  5219.9  258.17  5334.8  259.66  5363.4  260.88  5391.5  260.66  5595.6  264.32
#Mann=10,-1,0
  4456.2    0.05       0  4559.3     0.1       0  4648.3    0.12       0
  4661.3     0.1       0  4843.3    0.07       0  4918.3    0.07       0
  4924.3    0.07       0  5094.2    0.12       0  5219.9     0.1       0
  5391.5    0.05       0
Bank Sta=4918.3,4924.3
Exp/Cntr=0.3,0.1

Type RM Length L Ch R = 1,1848,33,33,33
BEGIN DESCRIPTION:
Mapping XS 984335ee
END DESCRIPTION:
XS GIS Cut Line= 6
      2246225.92     13378700.08      2246006.49     13378961.94
      2245911.41     13379084.82      2245898.24     13379160.88
      2245945.05     13379507.58      2245868.98     13379806.03
#Sta/Elev= 30
  4419.9  264.62  4517.2  261.87  4629.1  260.85  4664.3  263.06  4721.5  262.34
  4742.3  263.37  4750.1  261.65  4756.6  263.01  4806.2  262.84  4814.4  261.85
  4835.2  263.10  4864.2  261.79  4870.5  262.77  4878.7  261.33  4892.8  262.52
  4916.9  263.63  4959.6  262.53  5029.4  262.91  5089.1  261.87  5101.3  262.95
  5227.5  262.04  5314.5  263.22  5346.3  262.25  5364.0  260.53  5371.3  258.59
  5374.1  258.09  5377.3  258.59  5391.9  260.68  5430.3  260.87  5652.1  264.35
#Mann=7,-1,0
  4419.9    0.05       0  4517.2     0.1       0  4892.8    0.08       0
  5029.4     0.1       0  5371.3    0.07       0  5377.3     0.1       0
  5430.3    0.05       0
Bank Sta=5371.3,5377.3
Exp/Cntr=0.3,0.1

Type RM Length L Ch R = 1,1815,73,73,73
BEGIN DESCRIPTION:
Mapping XS c75cadc7
END DESCRIPTION:
XS GIS Cut Line= 4
      2246090.59     13378578.00      2245890.06     13379067.61
      2245845.79     13379255.11      2245723.39     13379887.94
#Sta/Elev= 30
  4387.4  265.00  4526.1  261.86  4534.3  261.90  4565.5  260.30  4631.5  259.41
  4696.3  258.57  4710.3  259.43  4813.9  257.67  4827.1  257.22  4936.3  258.18
  4944.9  260.08  4950.0  258.43  4987.2  257.99  5025.7  256.28  5028.5  255.78
  5031.7  256.28  5039.8  257.37  5046.8  257.19  5069.8  256.55  5120.6  256.92
  5125.7  258.19  5151.7  257.34  5223.0  257.59  5229.3  258.46  5255.3  258.19
  5324.8  258.83  5375.7  260.63  5447.0  261.76  5671.1  263.79  5753.7  265.25
#Mann=10,-1,0
  4387.4    0.05       0  4526.1     0.1       0  4534.3    0.08       0
  4631.5     0.1       0  4813.9    0.08       0  5025.7    0.07       0
  5031.7    0.08       0  5046.8     0.1       0  5255.3    0.08       0
  5447.0    0.05       0
Bank Sta=5025.7,5031.7
Exp/Cntr=0.3,0.1

Type RM Length L Ch R = 1,1742,301,301,301
BEGIN DESCRIPTION:
Mapping XS e600fb84
END DESCRIPTION:
XS GIS Cut Line= 2
      2245974.66     13378462.34      2245603.14     13379920.66
#Sta/Elev= 30
  4331.4  266.22  4335.4  266.22  4564.9  260.21  4680.5  258.01  4703.1  258.51
  4717.9  257.52  4728.2  258.13  4831.4  257.33  4866.7  256.24  4922.0  256.76
  4943.3  256.84  4955.2  255.54  5066.0  256.90  5076.1  255.36  5078.8  254.86
  5082.1  255.36  5084.7  255.63  5106.9  257.32  5372.6  259.69  5489.0  261.75
  5551.5  262.03  5556.7  262.80  5615.7  263.93  5667.3  263.36  5739.5  265.34
  5791.1  265.36  5796.9  264.32  5802.0  265.51  5823.2  265.40  5836.3  265.64
#Mann=11,-1,0
  4331.4    0.08       0  4335.4    0.05       0  4564.9     0.1       0
  4680.5    0.08       0  4922.0     0.1       0  5076.1    0.07       0
  5082.1     0.1       0  5084.7    0.08       0  5372.6     0.1       0
  5489.0    0.08       0  5823.2     0.1       0
Bank Sta=5076.1,5082.1
Exp/Cntr=0.3,0.1

Type RM Length L Ch R = 1,1441,287,287,287
BEGIN DESCRIPTION:
UNT004 IN SUCR 3.0
END DESCRIPTION:
XS GIS Cut Line= 3
      2245765.05     13378421.80      2245502.04     13379161.36
      2245491.62     13379601.50
#Sta/Elev= 30
  4481.8  264.33  4523.5  262.70  4540.2  262.58  4577.8  260.95  4657.0  259.07
  4670.4  258.06  4678.2  258.24  4788.4  255.13  4805.6  253.98  4819.3  253.82
  4826.8  252.92  4837.4  252.49  4869.1  252.44  4875.7  252.19  4962.9  251.98
  4993.7  251.48  4996.0  250.29  4998.8  249.79  5002.0  250.29  5007.2  251.36
  5024.5  251.74  5055.4  251.34  5147.9  252.50  5209.6  254.23  5482.3  259.87
  5552.3  260.53  5582.3  261.40  5652.3  262.15  5672.3  262.87  5707.0  262.67
#Mann=6,-1,0
  4481.8    0.05       0  4523.5     0.1       0  4869.1    0.16       0
  4875.7     0.1       0  4996.0    0.07       0  5002.0     0.1       0
Bank Sta=4996,5002
Exp/Cntr=0.3,0.1

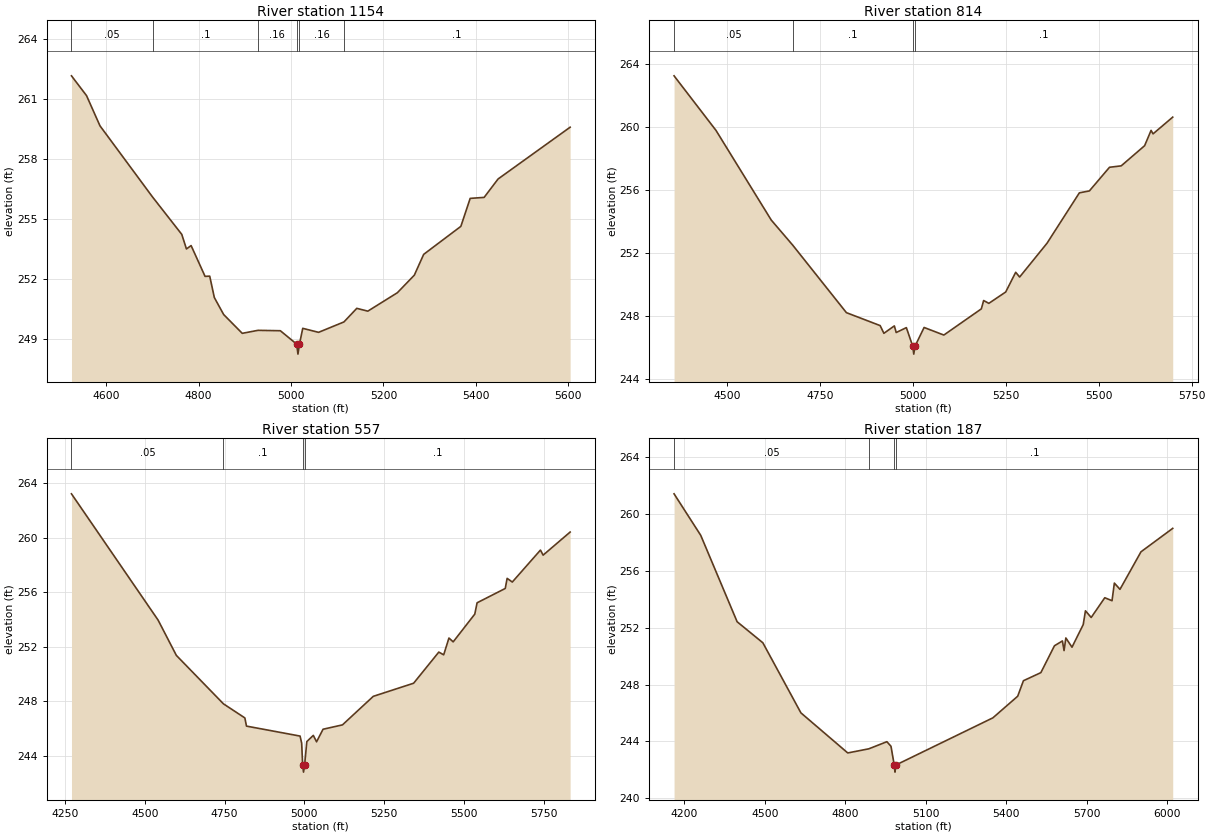
Type RM Length L Ch R = 1,1154,340,340,340
BEGIN DESCRIPTION:
UNT004 IN SUCR 2.0
END DESCRIPTION:
XS GIS Cut Line= 3
      2245478.60     13378367.08      2245390.06     13378565.01
      2245288.49     13379421.77
#Sta/Elev= 30
  4524.7  262.15  4557.3  261.16  4586.4  259.65  4700.2  256.09  4763.5  254.22
  4773.6  253.49  4783.7  253.66  4813.9  252.12  4824.0  252.13  4834.0  251.06
  4854.2  250.21  4894.4  249.27  4928.5  249.42  4976.9  249.40  5012.3  248.73
  5015.0  248.23  5018.3  248.73  5025.4  249.52  5059.7  249.32  5114.6  249.84
  5142.4  250.52  5166.3  250.38  5230.2  251.30  5267.0  252.18  5287.2  253.22
  5367.7  254.62  5387.9  256.02  5418.1  256.07  5448.3  256.99  5604.3  259.58
#Mann=6,-1,0
  4524.7    0.05       0  4700.2     0.1       0  4928.5    0.16       0
  5012.3    0.07       0  5018.3    0.16       0  5114.6     0.1       0
Bank Sta=5012.3,5018.3
Exp/Cntr=0.3,0.1

Type RM Length L Ch R = 1,814,257,257,257
BEGIN DESCRIPTION:
Mapping XS fda9050a
END DESCRIPTION:
XS GIS Cut Line= 4
      2245367.87     13378277.47      2245086.64     13378569.11
      2245027.62     13379034.38      2245169.97     13379478.79
#Sta/Elev= 30
  4358.3  263.25  4471.0  259.79  4619.7  254.10  4677.4  252.51  4821.7  248.23
  4912.4  247.41  4922.5  246.92  4950.6  247.39  4955.6  246.97  4982.9  247.28
  5000.1  246.10  5002.8  245.60  5006.1  246.10  5030.6  247.29  5083.7  246.81
  5184.5  248.47  5190.7  249.00  5204.7  248.82  5250.0  249.54  5276.9  250.79
  5287.5  250.49  5361.0  252.63  5448.1  255.83  5475.0  255.95  5529.1  257.45
  5560.6  257.54  5623.6  258.82  5640.9  259.79  5646.2  259.57  5699.1  260.63
#Mann=4,-1,0
  4358.3    0.05       0  4677.4     0.1       0  5000.1    0.07       0
  5006.1     0.1       0
Bank Sta=5000.1,5006.1
Exp/Cntr=0.3,0.1

Type RM Length L Ch R = 1,557,370,370,370
BEGIN DESCRIPTION:
Mapping XS 63ab9f26
END DESCRIPTION:
XS GIS Cut Line= 4
      2245282.78     13378211.69      2244868.46     13378516.14
      2244806.65     13378868.64      2245127.05     13379481.97
#Sta/Elev= 30
  4269.5  263.20  4541.3  253.95  4598.4  251.37  4746.2  247.82  4813.3  246.79
  4818.4  246.19  4986.5  245.46  4991.5  244.94  4994.6  243.32  4997.3  242.82
  5000.6  243.32  5007.7  245.06  5028.0  245.51  5038.2  245.04  5058.5  245.96
  5119.4  246.28  5216.1  248.37  5342.6  249.33  5421.6  251.61  5436.9  251.41
  5453.4  252.64  5466.7  252.36  5534.4  254.39  5541.7  255.22  5630.0  256.27
  5635.9  257.01  5652.1  256.74  5740.4  259.08  5748.8  258.71  5833.5  260.40
#Mann=4,-1,0
  4269.5    0.05       0  4746.2     0.1       0  4994.6    0.07       0
  5000.6     0.1       0
Bank Sta=4994.6,5000.6
Exp/Cntr=0.3,0.1

Type RM Length L Ch R = 1,187,0,0,0
BEGIN DESCRIPTION:
UNT004 IN SUCR 1.0
END DESCRIPTION:
XS GIS Cut Line= 4
      2245183.87     13378159.38      2244538.85     13378470.36
      2244502.22     13378678.65      2245034.54     13379444.08
#Sta/Elev= 30
  4161.3  261.42  4260.8  258.50  4396.5  252.42  4492.5  250.94  4634.4  246.01
  4809.1  243.19  4887.8  243.48  4955.0  243.98  4970.4  243.66  4982.5  242.34
  4985.3  241.84  4988.5  242.34  5350.5  245.66  5443.0  247.18  5464.3  248.27
  5529.4  248.84  5580.1  250.73  5609.8  251.07  5615.9  250.39  5622.6  251.28
  5645.5  250.63  5687.4  252.22  5695.7  253.19  5717.1  252.72  5767.8  254.11
  5794.8  253.90  5803.5  255.14  5824.5  254.70  5902.8  257.34  6021.2  258.99
#Mann=4,-1,0
  4161.3    0.05       0  4887.8     0.1       0  4982.5    0.07       0
  4988.5     0.1       0
Bank Sta=4982.5,4988.5
Exp/Cntr=0.3,0.1

Chan Stop Cuts=-1