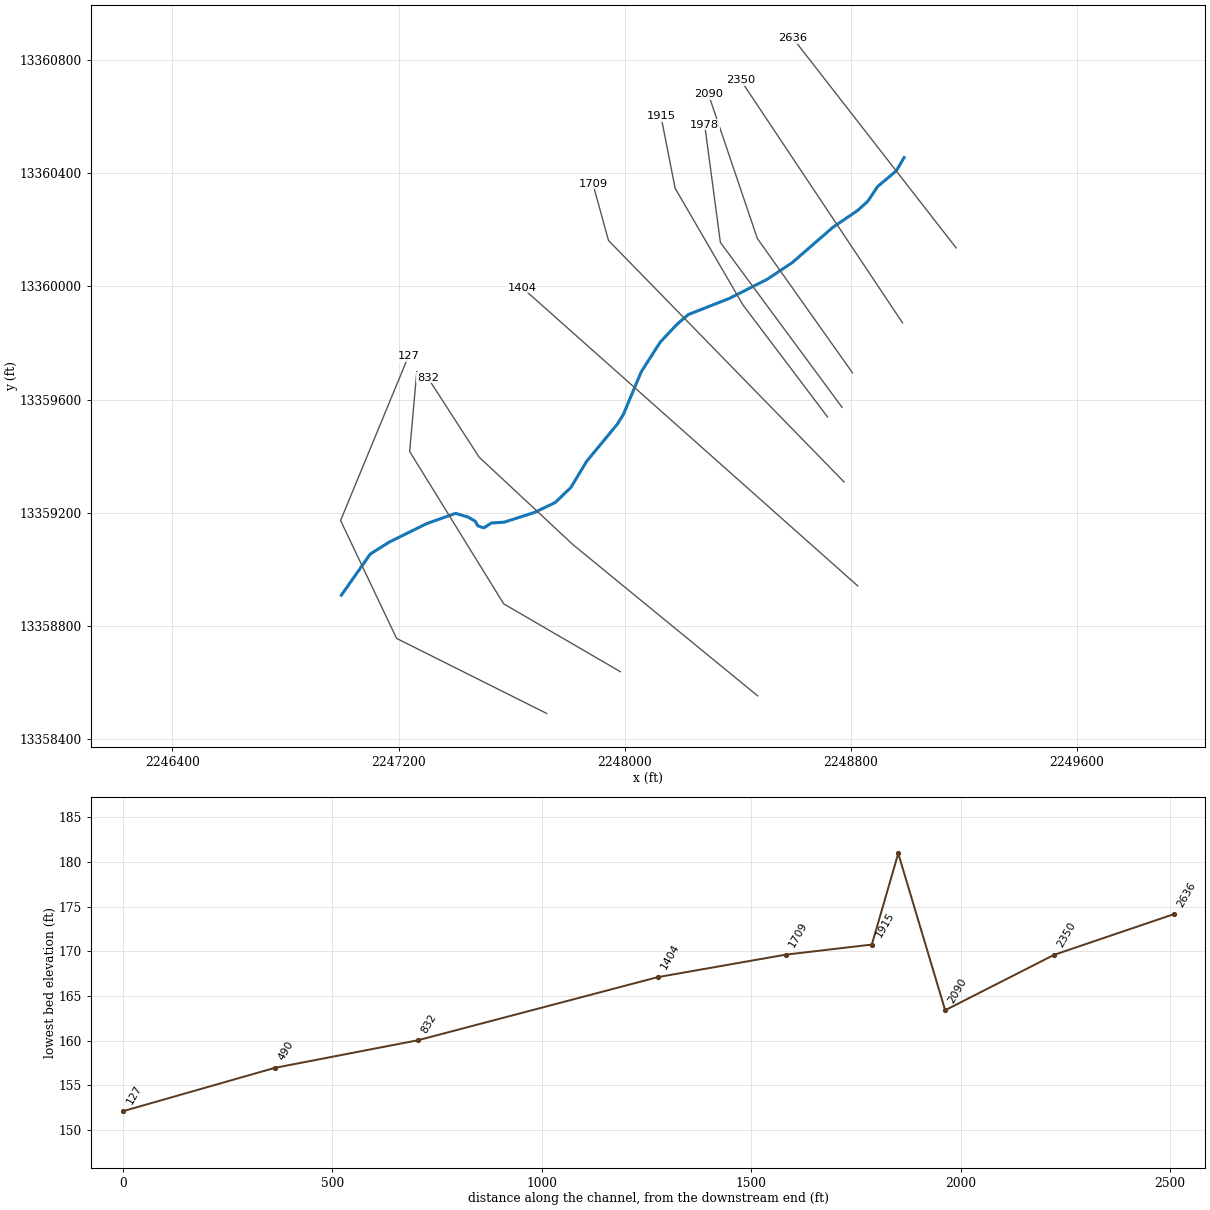
--- UNT005 IN SUCR.prj (project) ---

Proj Title=UNT005 IN SUCR Base Level Engineering
Current Plan=p01
Default Exp/Contr=0.3,0.1
English Units
Geom File=g01
Flow File=f01
Plan File=p01
BEGIN DESCRIPTION:
UNT005 IN SUCR
END DESCRIPTION:

--- UNT005 IN SUCR.p01 (plan) ---

Plan Title=Multiple Run
Short Identifier=Multiple
Geom File=g01
Flow File=f01
Subcritical Flow
K Sum by GR= 0
Std Step Tol= 0.01
Critical Tol= 0.01
Num of Std Step Trials= 20
Max Error Tol= 0.3
Flow Tol Ratio= 0.001
Split Flow NTrial= 30
Split Flow Tol= 0.02
Split Flow Ratio= 0.02
Log Output Level= 0
Friction Slope Method= 1
Unsteady Friction Slope Method= 2
Unsteady Bridges Friction Slope Method= 1
Parabolic Critical Depth
Global Vel Dist=  1 , 1 , 1
Global Log Level= 0
CheckData=True
Encroach Param= -1, 0, 0, 0
BEGIN DESCRIPTION:
Multiple Run
END DESCRIPTION:

--- UNT005 IN SUCR.f01 (steady flow) ---

Flow Title=Multiple
Number of Profiles=7
Profile Names=10-year,25-year,50-year,1pct_min,100-year,1pct_plu,500-year
River Rch & RM= UNT005 IN SUCR,Reach-1,2636
     230     318     391     354     478     647     727
River Rch & RM= UNT005 IN SUCR,Reach-1,832
     229     317     389     351     475     643     721
Boundary for River Rch & Prof#=UNT005 IN SUCR,Reach-1,1
Up Type=0
Dn Type=3
Dn Slope=0.005
Boundary for River Rch & Prof#=UNT005 IN SUCR,Reach-1,2
Up Type=0
Dn Type=3
Dn Slope=0.005
Boundary for River Rch & Prof#=UNT005 IN SUCR,Reach-1,3
Up Type=0
Dn Type=3
Dn Slope=0.005
Boundary for River Rch & Prof#=UNT005 IN SUCR,Reach-1,4
Up Type=0
Dn Type=3
Dn Slope=0.005
Boundary for River Rch & Prof#=UNT005 IN SUCR,Reach-1,5
Up Type=0
Dn Type=3
Dn Slope=0.005
Boundary for River Rch & Prof#=UNT005 IN SUCR,Reach-1,6
Up Type=0
Dn Type=3
Dn Slope=0.005
Boundary for River Rch & Prof#=UNT005 IN SUCR,Reach-1,7
Up Type=0
Dn Type=3
Dn Slope=0.005

--- UNT005 IN SUCR.g01 (geometry) ---

Geom Title=Existing Conditions

River Reach=UNT005 IN SUCR,Reach-1
Reach XY= 30
      2248988.95     13360456.11      2248961.17     13360409.24
      2248895.20     13360353.68      2248860.48     13360301.60
      2248824.02     13360268.61      2248737.21     13360209.58
      2248593.12     13360084.58      2248504.58     13360025.56
      2248370.90     13359957.85      2248225.06     13359900.56
      2248185.13     13359865.83      2248126.10     13359803.33
      2248058.40     13359697.43      2247995.90     13359548.12
      2247973.33     13359511.67      2247865.69     13359381.46
      2247810.13     13359289.44      2247754.58     13359235.62
      2247681.02     13359200.39      2247574.02     13359166.18
      2247528.13     13359162.95      2247502.28     13359146.07
      2247480.23     13359153.19      2247471.51     13359169.52
      2247447.28     13359183.54      2247402.15     13359197.43
      2247299.72     13359160.97      2247166.03     13359095.00
      2247100.06     13359053.33      2246997.75     13358907.79

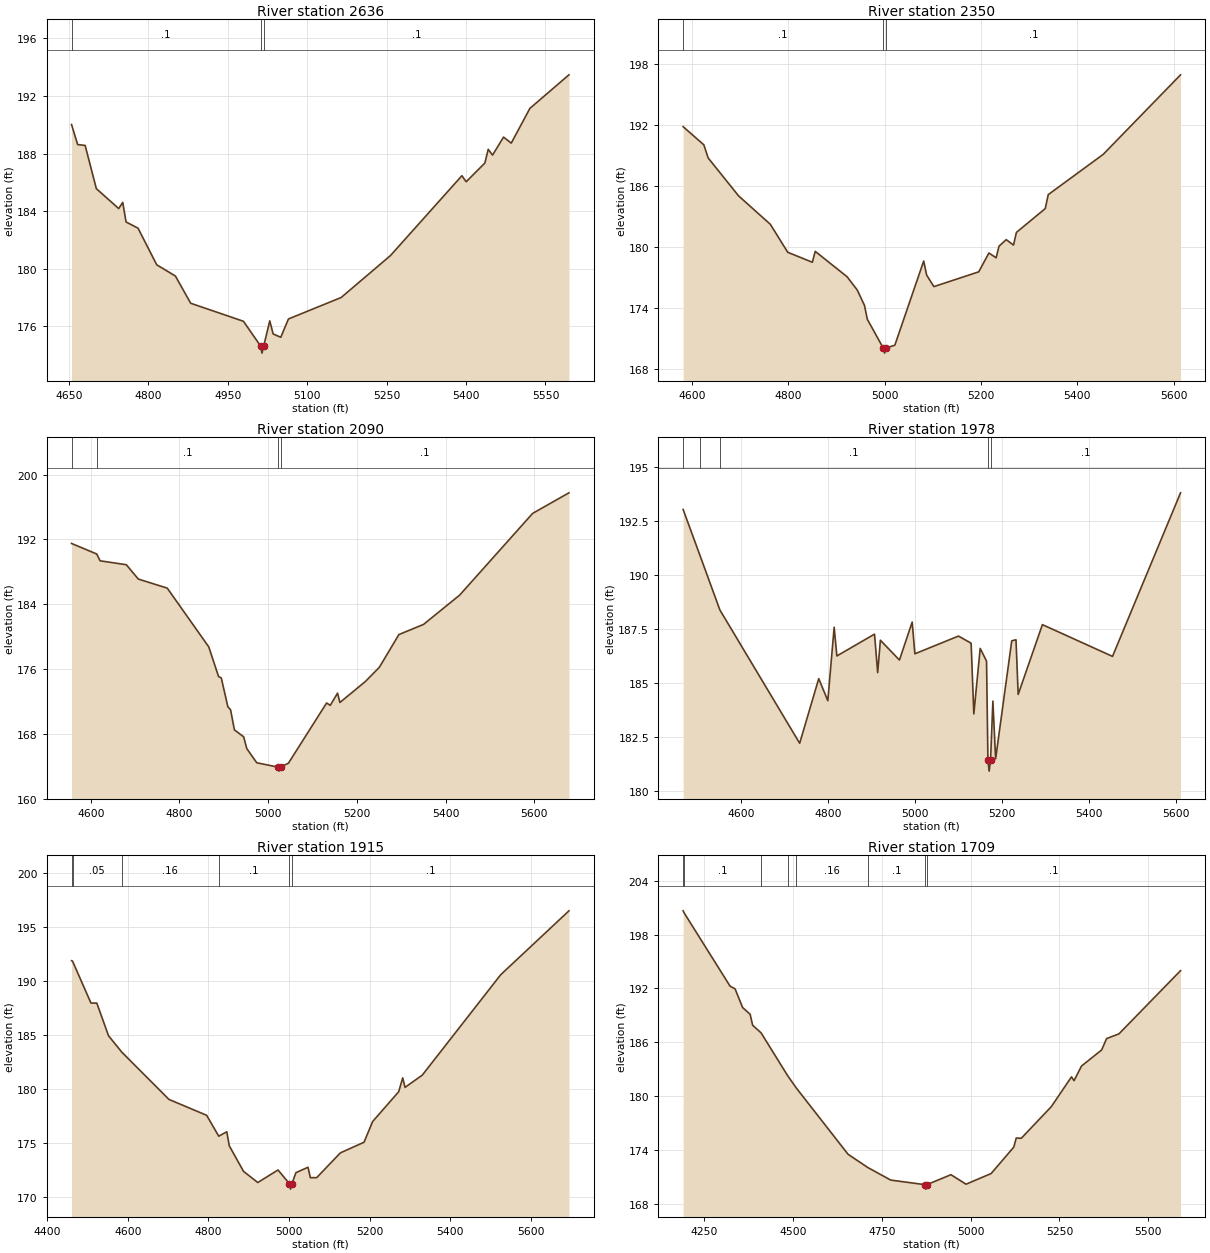
Type RM Length L Ch R = 1,2636,286,286,286
BEGIN DESCRIPTION:
UNT005 IN SUCR 4.0
END DESCRIPTION:
XS GIS Cut Line= 2
      2249172.86     13360136.57      2248595.78     13360877.94
#Sta/Elev= 30
  4654.8  190.01  4666.4  188.62  4680.5  188.56  4701.7  185.56  4743.9  184.18
  4751.5  184.61  4757.8  183.25  4780.4  182.82  4815.7  180.28  4851.0  179.50
  4879.9  177.61  4979.5  176.36  5011.8  174.65  5014.5  174.15  5017.8  174.65
  5029.2  176.39  5035.6  175.48  5050.0  175.25  5064.5  176.52  5164.1  178.01
  5257.2  180.92  5392.1  186.46  5400.2  186.04  5435.5  187.34  5441.8  188.29
  5450.0  187.89  5470.8  189.14  5485.3  188.72  5520.5  191.13  5594.3  193.46
#Mann=3,-1,0
  4654.8     0.1       0  5011.8    0.07       0  5017.8     0.1       0
Bank Sta=5011.8,5017.8
Exp/Cntr=0.3,0.1

Type RM Length L Ch R = 1,2350,260,260,260
BEGIN DESCRIPTION:
Mapping XS 66314312
END DESCRIPTION:
XS GIS Cut Line= 2
      2248983.29     13359871.21      2248410.40     13360730.55
#Sta/Elev= 30
  4581.8  191.83  4624.8  190.05  4633.8  188.76  4696.9  185.04  4763.0  182.24
  4799.0  179.50  4850.1  178.52  4856.1  179.59  4922.2  177.10  4943.3  175.80
  4958.3  174.29  4964.3  172.92  4997.3  170.10  5000.1  169.60  5003.3  170.10
  5021.4  170.38  5081.3  178.64  5087.5  177.25  5102.5  176.13  5195.6  177.58
  5216.7  179.43  5231.7  178.96  5237.7  180.10  5252.7  180.74  5267.8  180.21
  5273.8  181.45  5333.7  183.79  5339.9  185.16  5454.0  189.11  5614.6  196.92
#Mann=3,-1,0
  4581.8     0.1       0  4997.3    0.07       0  5003.3     0.1       0
Bank Sta=4997.3,5003.3
Exp/Cntr=0.3,0.1

Type RM Length L Ch R = 1,2090,112,112,112
BEGIN DESCRIPTION:
Mapping XS 3c5c8ddc
END DESCRIPTION:
XS GIS Cut Line= 3
      2248806.37     13359694.30      2248469.38     13360170.31
      2248296.66     13360680.02
#Sta/Elev= 30
  4556.8  191.50  4613.7  190.20  4621.2  189.36  4680.3  188.88  4707.3  187.11
  4772.6  185.99  4866.2  178.74  4888.3  175.08  4894.4  174.91  4909.2  171.36
  4915.3  170.99  4924.0  168.50  4944.9  167.64  4952.0  166.18  4974.4  164.44
  5021.9  163.91  5024.6  163.41  5027.9  163.91  5045.8  164.39  5131.9  171.82
  5140.0  171.52  5156.5  173.03  5161.8  171.88  5219.3  174.47  5250.7  176.22
  5294.8  180.26  5350.3  181.51  5432.0  185.14  5596.3  195.21  5678.2  197.75
#Mann=4,-1,0
  4556.8    0.05       0  4613.7     0.1       0  5021.9    0.07       0
  5027.9     0.1       0
Bank Sta=5021.9,5027.9
Exp/Cntr=0.3,0.1

Type RM Length L Ch R = 1,1978,63,63,63
BEGIN DESCRIPTION:
UNT005 IN SUCR 3.0
END DESCRIPTION:
XS GIS Cut Line= 3
      2248769.37     13359572.35      2248338.80     13360155.70
      2248283.28     13360572.07
#Sta/Elev= 30
  4466.2  193.05  4505.4  190.90  4550.8  188.40  4734.5  182.23  4778.4  185.22
  4799.3  184.20  4813.9  187.60  4820.1  186.27  4906.8  187.28  4914.1  185.50
  4920.3  187.00  4964.2  186.08  4993.5  187.84  4999.7  186.37  5100.0  187.19
  5129.2  186.86  5135.4  183.59  5150.1  186.62  5164.7  186.03  5167.9  181.44
  5170.7  180.94  5173.9  181.44  5179.3  184.18  5185.6  181.51  5222.7  186.97
  5232.5  187.02  5237.5  184.49  5293.3  187.72  5454.7  186.25  5611.3  193.82
#Mann=5,-1,0
  4466.2     0.1       0  4505.4    0.05       0  4550.8     0.1       0
  5167.9    0.07       0  5173.9     0.1       0
Bank Sta=5167.9,5173.9
Exp/Cntr=0.3,0.1

Type RM Length L Ch R = 1,1915,206,206,206
BEGIN DESCRIPTION:
Mapping XS 10445591
END DESCRIPTION:
XS GIS Cut Line= 4
      2248717.93     13359538.42      2248418.83     13359934.41
      2248178.73     13360347.22      2248128.41     13360603.00
#Sta/Elev= 30
  4460.2  191.85  4462.6  191.82  4508.4  187.94  4522.9  187.94  4552.0  184.92
  4585.1  183.40  4701.9  179.04  4795.5  177.57  4825.6  175.64  4845.5  176.05
  4851.7  174.75  4887.1  172.39  4922.5  171.36  4972.6  172.52  5001.1  171.25
  5003.8  170.75  5007.1  171.25  5017.1  172.27  5047.1  172.77  5052.9  171.81
  5068.6  171.81  5127.4  174.10  5186.1  175.08  5207.6  177.00  5272.2  179.75
  5282.1  181.03  5287.9  180.15  5330.9  181.29  5525.4  190.56  5694.7  196.46
#Mann=6,-1,0
  4460.2     0.1       0  4462.6    0.05       0  4585.1    0.16       0
  4825.6     0.1       0  5001.1    0.07       0  5007.1     0.1       0
Bank Sta=5001.1,5007.1
Exp/Cntr=0.3,0.1

Type RM Length L Ch R = 1,1709,305,305,305
BEGIN DESCRIPTION:
Mapping XS e8c098cb
END DESCRIPTION:
XS GIS Cut Line= 3
      2248776.28     13359308.50      2247942.96     13360162.65
      2247887.71     13360362.95
#Sta/Elev= 30
  4190.2  200.66  4194.0  200.37  4322.4  192.26  4336.6  191.95  4357.7  189.88
  4379.0  189.12  4386.0  187.90  4409.8  187.05  4484.2  182.30  4509.0  180.90
  4654.7  173.51  4710.4  172.03  4774.9  170.63  4870.9  170.12  4873.6  169.62
  4876.9  170.12  4944.6  171.23  4987.1  170.17  5057.8  171.36  5121.5  174.30
  5128.5  175.32  5142.7  175.29  5227.5  178.83  5284.1  182.14  5291.3  181.72
  5312.4  183.35  5369.0  185.14  5383.0  186.41  5417.9  186.94  5591.3  193.99
#Mann=8,-1,0
  4190.2    0.05       0  4194.0     0.1       0  4409.8    0.05       0
  4484.2    0.08       0  4509.0    0.16       0  4710.4     0.1       0
  4870.9    0.07       0  4876.9     0.1       0
Bank Sta=4870.9,4876.9
Exp/Cntr=0.3,0.1

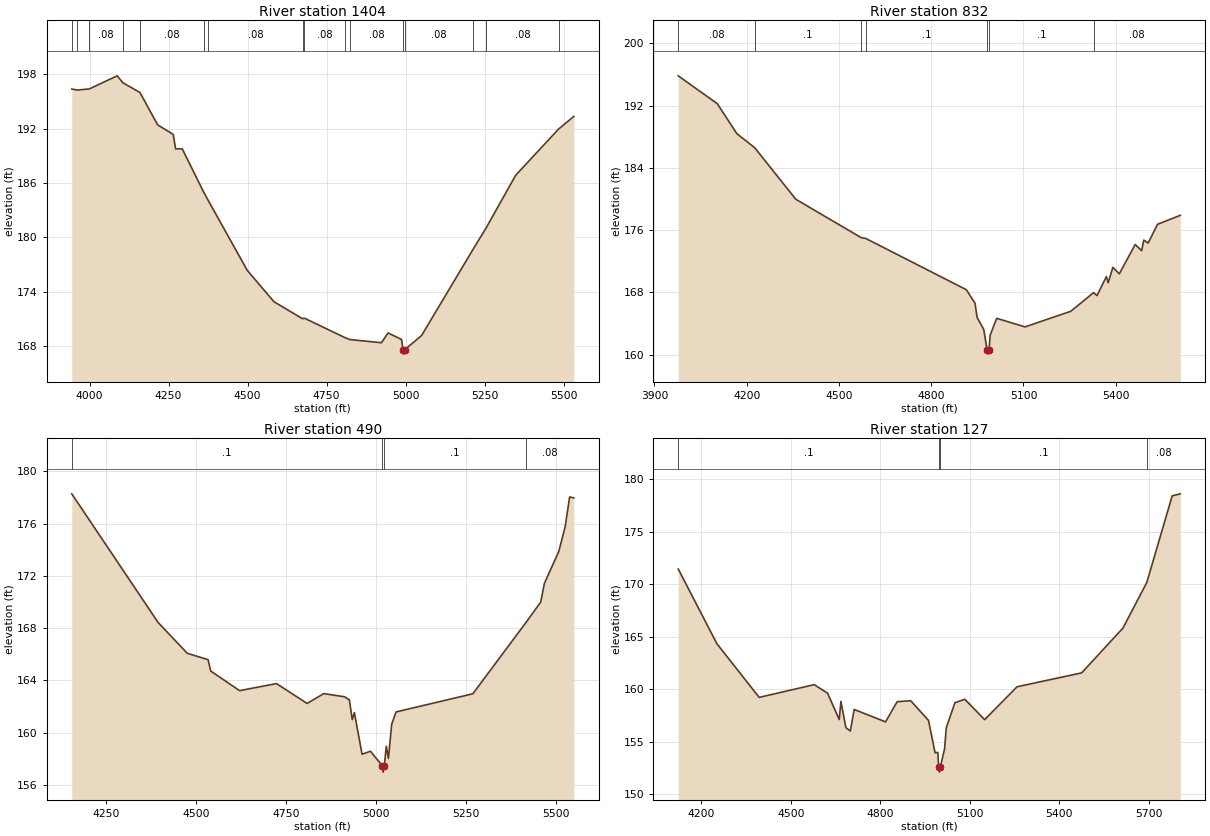
Type RM Length L Ch R = 1,1404,572,572,572
BEGIN DESCRIPTION:
UNT005 IN SUCR 2.0
END DESCRIPTION:
XS GIS Cut Line= 2
      2248824.88     13358940.45      2247637.39     13359996.00
#Sta/Elev= 30
  3943.6  196.39  3961.4  196.28  3998.9  196.40  4087.4  197.85  4105.1  197.09
  4159.4  196.01  4215.4  192.43  4264.7  191.38  4272.2  189.78  4293.1  189.79
  4360.9  185.01  4375.5  184.08  4498.8  176.37  4583.3  172.90  4673.9  171.02
  4679.9  171.08  4808.9  168.92  4823.7  168.72  4923.6  168.37  4944.5  169.45
  4987.2  168.73  4991.7  167.61  4994.5  167.11  4997.7  167.61  5050.7  169.17
  5213.9  178.71  5254.8  181.05  5348.4  186.87  5483.9  191.96  5532.4  193.37
#Mann=16,-1,0
  3943.6    0.08       0  3961.4    0.05       0  3998.9    0.08       0
  4105.1    0.05       0  4159.4    0.08       0  4360.9     0.1       0
  4375.5    0.08       0  4673.9     0.1       0  4679.9    0.08       0
  4808.9     0.1       0  4823.7    0.08       0  4991.7    0.07       0
  4997.7    0.08       0  5213.9     0.1       0  5254.8    0.08       0
  5483.9     0.1       0
Bank Sta=4991.7,4997.7
Exp/Cntr=0.3,0.1

Type RM Length L Ch R = 1,832,342,342,342
BEGIN DESCRIPTION:
Mapping XS cbfda6d7
END DESCRIPTION:
XS GIS Cut Line= 4
      2248470.76     13358551.52      2247818.22     13359085.72
      2247484.89     13359396.49      2247304.07     13359676.55
#Sta/Elev= 30
  3977.6  195.82  4104.4  192.25  4168.2  188.39  4225.8  186.60  4359.9  179.96
  4572.3  175.03  4587.5  174.92  4914.2  168.34  4942.5  166.61  4949.4  164.77
  4970.9  163.24  4982.0  160.56  4984.8  160.06  4988.0  160.56  4991.9  162.51
  5013.0  164.66  5105.2  163.56  5253.7  165.56  5328.1  167.96  5339.2  167.58
  5369.6  170.03  5375.5  169.23  5390.7  171.21  5411.8  170.38  5463.3  174.15
  5484.4  173.35  5491.3  174.71  5505.5  174.33  5535.9  176.74  5610.0  177.90
#Mann=7,-1,0
  3977.6    0.08       0  4225.8     0.1       0  4572.3    0.08       0
  4587.5     0.1       0  4982.0    0.07       0  4988.0     0.1       0
  5328.1    0.08       0
Bank Sta=4982,4988
Exp/Cntr=0.3,0.1

Type RM Length L Ch R = 1,490,363,363,363
BEGIN DESCRIPTION:
Mapping XS e3db0405
END DESCRIPTION:
XS GIS Cut Line= 4
      2247984.98     13358637.00      2247572.15     13358877.12
      2247239.37     13359416.30      2247264.64     13359698.48
#Sta/Elev= 30
  4155.5  178.28  4395.3  168.43  4476.3  166.07  4534.1  165.58  4541.5  164.71
  4621.7  163.21  4724.1  163.75  4809.1  162.23  4855.3  162.98  4913.3  162.74
  4926.6  162.50  4934.5  160.99  4940.4  161.53  4961.8  158.34  4985.3  158.57
  5017.6  157.47  5020.3  156.97  5023.6  157.47  5029.1  158.95  5035.0  158.02
  5044.1  160.64  5056.3  161.58  5269.5  162.97  5416.8  168.42  5458.0  169.99
  5468.1  171.41  5508.2  173.87  5525.9  175.76  5538.3  178.04  5550.0  177.97
#Mann=4,-1,0
  4155.5     0.1       0  5017.6    0.07       0  5023.6     0.1       0
  5416.8    0.08       0
Bank Sta=5017.6,5023.6
Exp/Cntr=0.3,0.1

Type RM Length L Ch R = 1,127,0,0,0
BEGIN DESCRIPTION:
UNT005 IN SUCR 1.0
END DESCRIPTION:
XS GIS Cut Line= 4
      2247723.76     13358489.60      2247193.04     13358754.96
      2246995.06     13359171.98      2247234.88     13359752.61
#Sta/Elev= 30
  4122.1  171.44  4251.8  164.33  4393.5  159.23  4578.0  160.44  4622.7  159.63
  4661.9  157.12  4667.4  158.85  4684.2  156.35  4699.0  156.03  4712.0  158.08
  4817.2  156.90  4856.0  158.82  4901.5  158.91  4961.1  157.04  4983.2  153.96
  4992.4  153.99  4994.9  152.62  4997.7  152.12  5000.9  152.62  5015.1  154.34
  5020.6  156.32  5049.6  158.72  5082.9  159.05  5149.3  157.11  5258.1  160.24
  5474.5  161.56  5613.0  165.82  5693.0  170.16  5778.1  178.40  5805.3  178.59
#Mann=4,-1,0
  4122.1     0.1       0  4994.9    0.07       0  5000.9     0.1       0
  5693.0    0.08       0
Bank Sta=4994.9,5000.9
Exp/Cntr=0.3,0.1

Chan Stop Cuts=-1