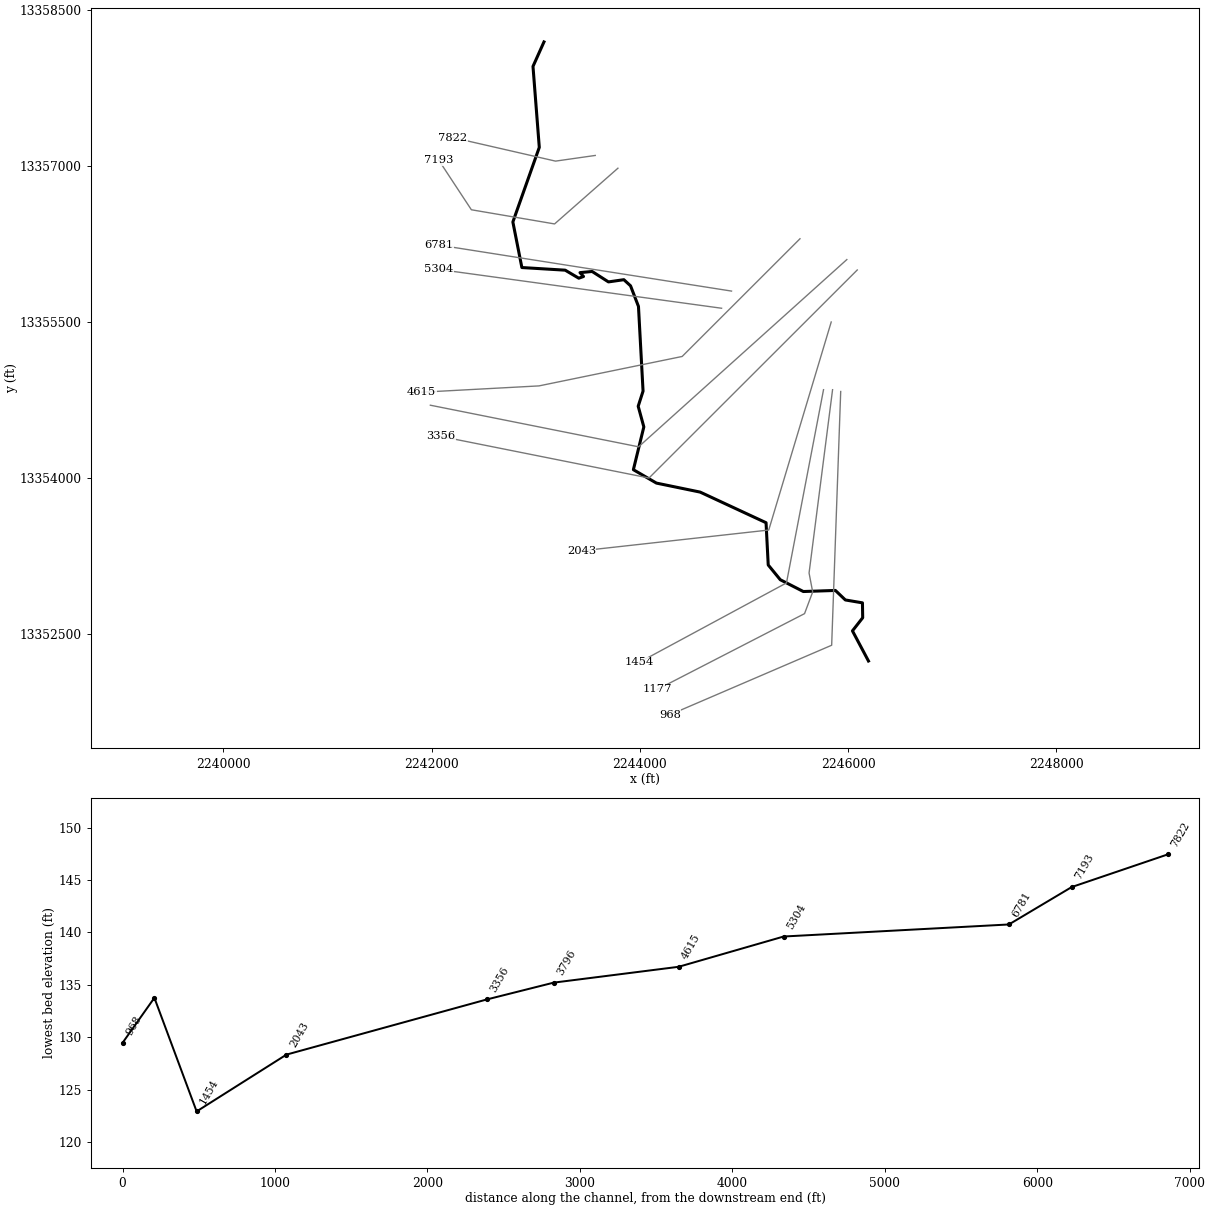
--- UNT007 IN SUCR.prj (project) ---

Proj Title=UNT007 IN SUCR Base Level Engineering
Current Plan=p01
Default Exp/Contr=0.3,0.1
English Units
Geom File=g01
Flow File=f01
Plan File=p01
Y Axis Title=Elevation
X Axis Title(PF)=Main Channel Distance
X Axis Title(XS)=Station
BEGIN DESCRIPTION:
UNT007 IN SUCR
END DESCRIPTION:
DSS Export Rating Curves= 0
DSS Export Rating Curve Sorted= 0
DSS Export Volume Flow Curves= 0
DXF OffsetX= 0
DXF OffsetY= 0
DXF ScaleX= 1
DXF ScaleY= 10

--- UNT007 IN SUCR.p01 (plan) ---

Plan Title=Multiple Run
Short Identifier=Multiple
Geom File=g01
Flow File=f01
Subcritical Flow
K Sum by GR= 0
Std Step Tol= 0.01
Critical Tol= 0.01
Num of Std Step Trials= 20
Max Error Tol= 0.3
Flow Tol Ratio= 0.001
Split Flow NTrial= 30
Split Flow Tol= 0.02
Split Flow Ratio= 0.02
Log Output Level= 0
Friction Slope Method= 1
Unsteady Friction Slope Method= 2
Unsteady Bridges Friction Slope Method= 1
Parabolic Critical Depth
Global Vel Dist=  1 , 1 , 1
Global Log Level= 0
CheckData=True
Encroach Param= -1, 0, 0, 0
BEGIN DESCRIPTION:
Multiple Run
END DESCRIPTION:

--- UNT007 IN SUCR.f01 (steady flow) ---

Flow Title=Multiple
Program Version=4.10
Number of Profiles= 7
Profile Names=10-year,25-year,50-year,1pct_min,100-year,1pct_plu,500-year
River Rch & RM=UNT007 IN SUCR,Reach-1         ,7822
     181     246     299     267     362     489     538
River Rch & RM=UNT007 IN SUCR,Reach-1         ,5304
     245     338     415     375     507     685     766
Boundary for River Rch & Prof#=UNT007 IN SUCR,Reach-1         , 1
Up Type= 0
Dn Type= 3
Dn Slope=0.0208
Boundary for River Rch & Prof#=UNT007 IN SUCR,Reach-1         , 2
Up Type= 0
Dn Type= 3
Dn Slope=0.0208
Boundary for River Rch & Prof#=UNT007 IN SUCR,Reach-1         , 3
Up Type= 0
Dn Type= 3
Dn Slope=0.0208
Boundary for River Rch & Prof#=UNT007 IN SUCR,Reach-1         , 4
Up Type= 0
Dn Type= 3
Dn Slope=0.0208
Boundary for River Rch & Prof#=UNT007 IN SUCR,Reach-1         , 5
Up Type= 0
Dn Type= 3
Dn Slope=0.0208
Boundary for River Rch & Prof#=UNT007 IN SUCR,Reach-1         , 6
Up Type= 0
Dn Type= 3
Dn Slope=0.0208
Boundary for River Rch & Prof#=UNT007 IN SUCR,Reach-1         , 7
Up Type= 0
Dn Type= 3
Dn Slope=0.0208
DSS Import GetInterval= 0
DSS Import GetPeak= 0
DSS Import FillOption= 0

--- UNT007 IN SUCR.g01 (geometry) ---

Geom Title=Existing Conditions
Program Version=4.10

River Reach=UNT007 IN SUCR  ,Reach-1
Reach XY= 30
      2243079.01      13358189.1      2242973.56     13357953.61
      2243034.09     13357175.42      2242780.33     13356458.37
      2242866.83     13356020.22      2243282.89     13355994.86
      2243413.32     13355917.74       2243458.9     13355934.08
      2243424.88     13355971.36      2243541.45     13355982.42
      2243698.28     13355882.09      2243846.22     13355903.47
      2243910.58     13355844.36      2243986.56      13355646.4
      2244030.64     13354832.35      2243983.88     13354686.77
      2244038.12     13354488.28      2243937.72     13354076.86
      2244159.13     13353948.02      2244579.07     13353861.47
      2245211.88      13353567.2      2245232.72     13353160.95
       2245348.6     13353019.02      2245569.96     13352905.74
      2245877.83     13352916.11      2245973.43     13352824.66
      2246137.72     13352796.85      2246139.95     13352653.53
      2246041.63     13352527.59      2246195.49     13352237.73

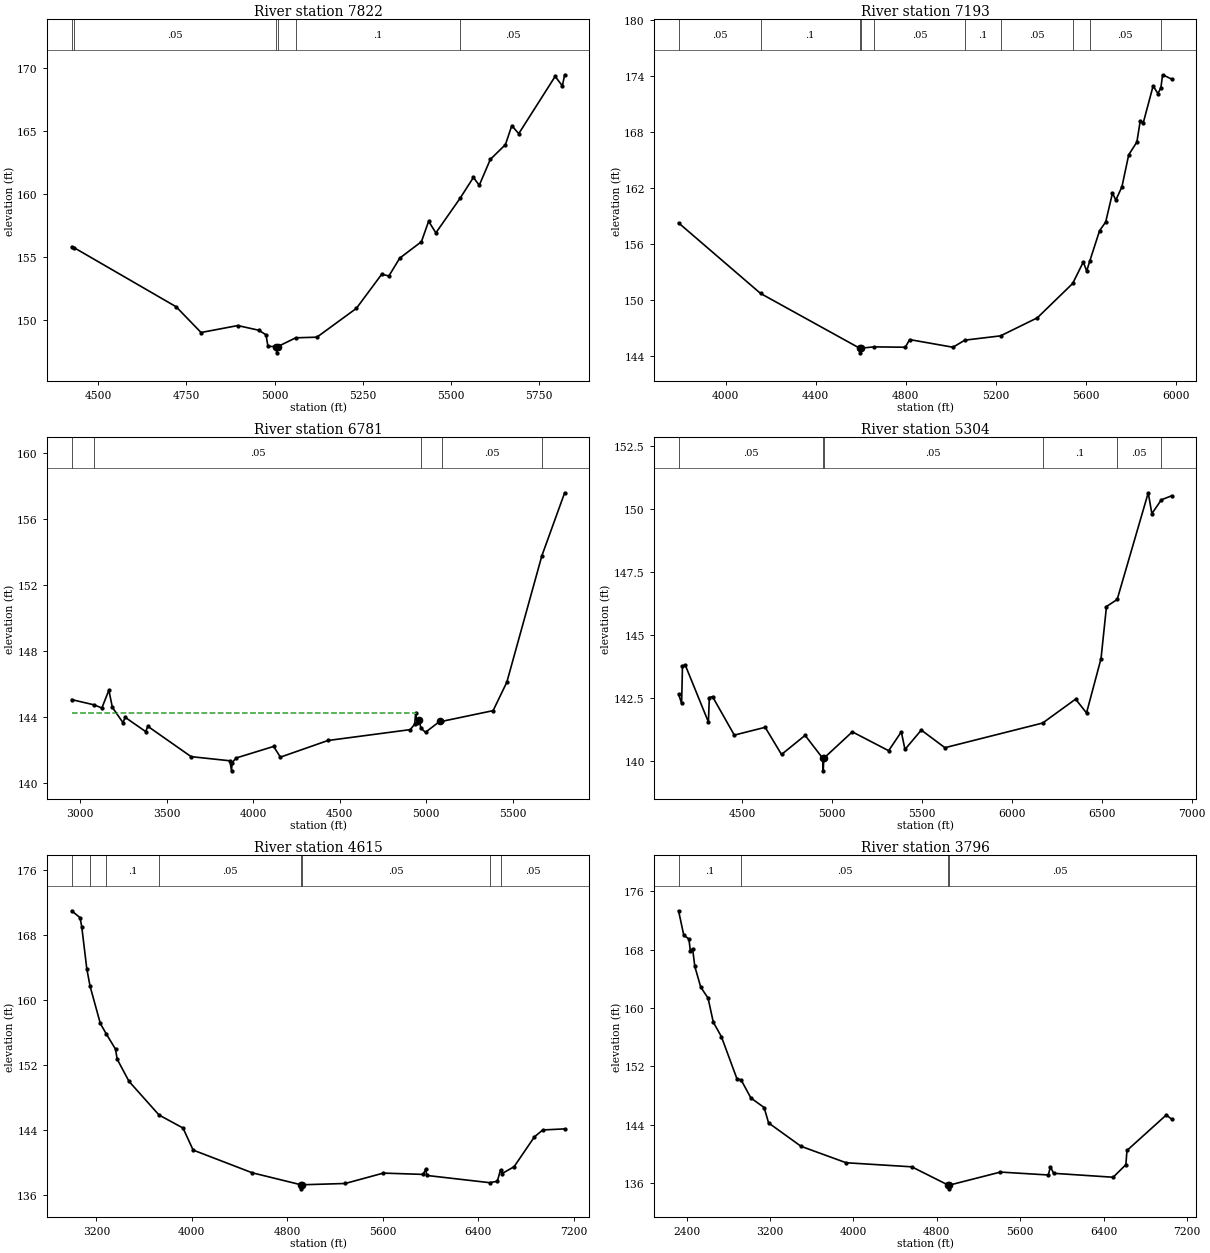
Type RM Length L Ch R = 1 ,7822    ,629,629,629
BEGIN DESCRIPTION:
UNT007 IN SUCR 9.0
END DESCRIPTION:
XS GIS Cut Line= 3
      2243571.38     13357097.77      2243189.98     13357043.28
      2242201.42     13357270.02
#Sta/Elev= 30
    4424  155.83    4432  155.74  4720.6  151.08  4791.4  149.04  4895.6  149.59
  4955.2  149.22  4975.7  148.86  4981.3  147.94  5003.5  147.93  5006.3  147.43
  5009.5  147.93  5060.1  148.62  5120.3  148.67  5232.2  150.95  5304.1  153.65
  5324.6  153.52  5355.4  154.93  5416.9  156.23  5437.4  157.85  5457.9  156.93
  5526.9  159.68  5564.5  161.32  5581.1   160.7  5612.5  162.75  5655.4  163.92
  5673.4  165.42  5693.2  164.79  5796.5  169.32    5817  168.57  5823.5  169.45
#Mann= 6 ,-1 , 0
    4424      .1       0    4432     .05       0  5003.5    .035       0
  5009.5     .05       0  5060.1      .1       0  5526.9     .05       0
Bank Sta=5003.5,5009.5
XS Rating Curve= 0 ,0
Exp/Cntr=0.3,0.1

Type RM Length L Ch R = 1 ,7193    ,412,412,412
BEGIN DESCRIPTION:
UNT007 IN SUCR 7.0
END DESCRIPTION:
XS GIS Cut Line= 4
      2243789.34      13356975.2       2243180.9     13356439.41
      2242381.79     13356575.62      2242068.68     13357052.09
#Sta/Elev= 30
    3790  158.24  4154.6  150.68  4594.7  144.82  4597.4  144.32  4600.7  144.82
  4658.7  144.96  4797.8  144.92    4817  145.74  5009.7  144.92  5062.5  145.68
  5221.3  146.14  5384.5  148.07  5541.8  151.75    5589  154.05  5604.1  153.08
    5618  154.17  5661.4  157.41  5688.4  158.33  5718.6  161.42  5733.7  160.69
  5760.7  162.11  5790.9  165.54  5827.1   166.9  5842.2  169.19  5855.6  168.97
  5899.4  172.92  5920.5   172.1  5933.7  172.69  5941.5  174.11  5981.5  173.65
#Mann= 10 ,-1 , 0
    3790     .05       0  4154.6      .1       0  4594.7    .035       0
  4600.7      .1       0  4658.7     .05       0  5062.5      .1       0
  5221.3     .05       0  5541.8      .1       0    5618     .05       0
  5933.7      .1       0
Bank Sta=4594.7,4600.7
XS Rating Curve= 0 ,0
Exp/Cntr=0.3,0.1

Type RM Length L Ch R = 1 ,6781    ,1477,1477,1477
BEGIN DESCRIPTION:
Mapping XS 84a3b850
END DESCRIPTION:
XS GIS Cut Line= 2
      2244880.16     13355793.88      2242067.69     13356236.58
#Sta/Elev= 30
  2951.6  145.07  3081.4  144.75  3126.2  144.56  3166.7  145.64  3186.9   144.6
  3247.6  143.68  3261.5  143.99  3379.2  143.13  3391.6  143.45  3641.7  141.61
  3865.1  141.36    3875  140.75  3878.3  141.25  3901.9  141.53  4118.2  142.23
  4157.1  141.58    4432  142.59  4907.8  143.25  4932.7  143.59  4938.2  144.23
  4948.3  143.64  4958.4  143.86  4968.6  143.33  4995.2  143.09  5079.9  143.77
  5089.8  143.75  5385.5   144.4  5464.6  146.12  5667.1  153.79  5798.7  157.61
#Mann= 5 ,-1 , 0
  2951.6      .1       0  3081.4     .05       0  4968.6    .035       0
  5089.8     .05       0  5667.1     .05       0
#XS Ineff= 2 , 0
         4938.92  144.25
Permanent Ineff=
       F       F
Bank Sta=4958.4,5079.9
XS Rating Curve= 0 ,0
Exp/Cntr=0.3,0.1

Type RM Length L Ch R = 1 ,5304    ,689,689,689
BEGIN DESCRIPTION:
Mapping XS 31f812b3
END DESCRIPTION:
XS GIS Cut Line= 2
      2244784.71     13355628.94      2242069.02     13356002.03
#Sta/Elev= 30
  4147.3  142.65  4164.1  142.28  4169.1  143.77  4184.6   143.8  4313.2  141.54
  4318.3  142.51    4336  142.55  4457.2  141.02  4628.8  141.33  4719.6  140.25
  4850.8  141.01  4948.8   140.1  4951.5   139.6  4954.8   140.1  5113.3  141.15
  5315.2   140.4  5385.8  141.15    5406  140.45  5496.8  141.22  5628.1  140.52
  6171.6   141.5  6354.8  142.45  6415.4   141.9  6496.1  144.06  6526.4  146.13
  6585.9  146.41  6758.6  150.65  6778.8  149.82  6831.4  150.37  6888.5  150.53
#Mann= 6 ,-1 , 0
  4147.3     .05       0  4948.8    .035       0  4954.8     .05       0
  6171.6      .1       0  6585.9     .05       0  6831.4      .1       0
Bank Sta=4948.8,4954.8
XS Rating Curve= 0 ,0
Exp/Cntr=0.3,0.1

Type RM Length L Ch R = 1 ,4615    ,819,819,819
BEGIN DESCRIPTION:
UNT007 IN SUCR 6.0
END DESCRIPTION:
XS GIS Cut Line= 4
      2245537.74     13356296.88      2244406.25     13355165.39
      2243031.23     13354882.42      2241904.67     13354821.75
#Sta/Elev= 30
  2992.4  170.99  3063.1  170.14  3077.3  169.01  3119.7  163.82    3147  161.69
  3232.8   157.1  3281.9  155.83  3360.1  153.93  3374.3  152.69  3473.3  149.96
    3725  145.81  3925.8  144.21  4010.7  141.49  4505.6  138.69  4914.8  137.21
  4917.5  136.71  4920.8  137.21  5285.3  137.37  5604.6  138.65  5938.7  138.49
  5959.1  139.12  5969.4  138.36  6495.5  137.47  6560.3  137.64  6587.1  139.06
  6600.8   138.6  6700.9  139.44  6871.2  143.12  6941.5  143.97  7124.6   144.1
#Mann= 8 ,-1 , 0
  2992.4      .1       0    3147     .05       0  3281.9      .1       0
    3725     .05       0  4914.8    .035       0  4920.8     .05       0
  6495.5      .1       0  6587.1     .05       0
Bank Sta=4914.8,4920.8
XS Rating Curve= 0 ,0
Exp/Cntr=0.3,0.1

Type RM Length L Ch R = 1 ,3796    ,440,440,440
BEGIN DESCRIPTION:
UNT007 IN SUCR 5.0
END DESCRIPTION:
XS GIS Cut Line= 3
      2245987.71     13356096.85      2243987.72     13354296.85
      2241987.74     13354696.85
#Sta/Elev= 30
  2322.1  173.34  2371.8  169.99  2421.1  169.47  2435.3  167.82  2456.6  168.15
  2477.9   165.7  2534.7  162.87    2605  161.36  2655.1  158.06  2732.8  156.08
  2881.5  150.32  2922.7  150.12  3016.1  147.66  3143.1  146.35  3185.7  144.24
  3497.4  141.03  3929.4  138.78  4559.5  138.22  4910.8   135.7  4913.5   135.2
  4916.8   135.7  5410.5   137.5  5869.5   137.1  5889.8  138.23  5920.4  137.33
  6491.5  136.79  6613.9  138.52  6624.1  140.46  7001.4  145.33  7052.4  144.76
#Mann= 4 ,-1 , 0
  2322.1      .1       0  2922.7     .05       0  4910.8    .035       0
  4916.8     .05       0
Bank Sta=4910.8,4916.8
XS Rating Curve= 0 ,0
Exp/Cntr=0.3,0.1

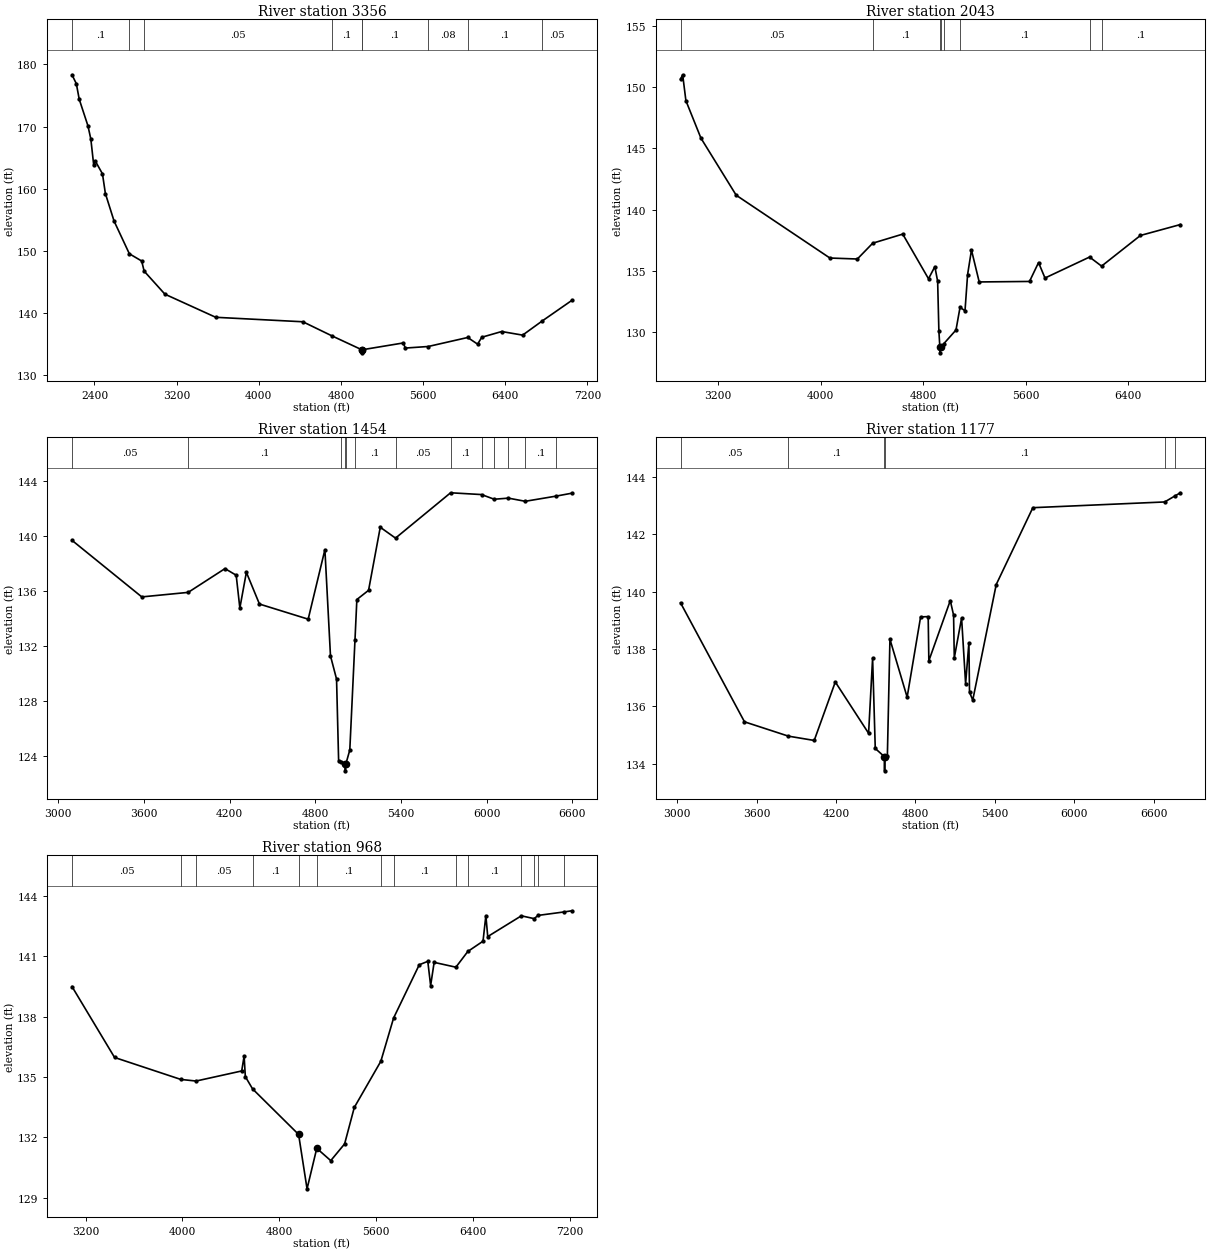
Type RM Length L Ch R = 1 ,3356    ,1313,1313,1313
BEGIN DESCRIPTION:
UNT007 IN SUCR 4.0
END DESCRIPTION:
XS GIS Cut Line= 3
      2246087.72     13355996.85      2244087.72     13353996.85
      2242087.75     13354396.85
#Sta/Elev= 30
  2180.9  178.34  2223.3  176.91  2251.6   174.4  2336.5  170.12  2364.7  167.98
    2393  163.75  2407.2  164.48  2477.9   162.4  2506.2  159.23    2591  154.79
  2739.8  149.53  2859.7  148.37  2883.7  146.74    3086  143.03    3581  139.31
  4429.5  138.59    4709  136.35  5002.8  134.09  5005.5  133.59  5008.8  134.09
    5407  135.18  5427.4  134.36    5650  134.61  6034.7  136.06  6131.1  134.99
  6171.9   136.1  6365.7  137.02  6569.6  136.44  6758.8   138.7  7048.9  142.03
#Mann= 9 ,-1 , 0
  2180.9      .1       0  2739.8     .08       0  2883.7     .05       0
    4709      .1       0  5002.8     .07       0  5008.8      .1       0
    5650     .08       0  6034.7      .1       0  6758.8     .05       0
Bank Sta=5002.8,5008.8
XS Rating Curve= 0 ,0
Exp/Cntr=0.3,0.1

Type RM Length L Ch R = 1 ,2043    ,589,589,589
BEGIN DESCRIPTION:
UNT007 IN SUCR 3.0
END DESCRIPTION:
XS GIS Cut Line= 3
      2245837.72     13355496.84      2245237.72     13353496.85
      2243437.74     13353296.86
#Sta/Elev= 30
  2907.5  150.65    2924     151  2949.2  148.89  3066.7  145.83  3341.6  141.18
  4072.4  136.06  4286.5  135.98  4406.5  137.27  4640.6  138.01  4841.6  134.37
  4891.1  135.36  4912.9  134.16  4922.5  130.11  4929.9  128.83  4932.7  128.33
  4935.9  128.83  4960.4  129.07  5055.9  130.19  5087.5  132.04  5126.3  131.76
  5146.5  134.71  5176.7  136.71    5237  134.11  5629.4  134.15  5699.9  135.69
  5750.2  134.43  6097.9  136.14  6191.6   135.4  6494.7   137.9  6806.6  138.79
#Mann= 8 ,-1 , 0
  2907.5     .05       0  4406.5      .1       0  4929.9     .07       0
  4935.9      .1       0  4960.4     .07       0  5087.5      .1       0
  6097.9     .08       0  6191.6      .1       0
Bank Sta=4929.9,4935.9
XS Rating Curve= 0 ,0
Exp/Cntr=0.3,0.1

Type RM Length L Ch R = 1 ,1454    ,277,277,277
BEGIN DESCRIPTION:
UNT007 IN SUCR 2.0
END DESCRIPTION:
XS GIS Cut Line= 3
      2245763.87     13354845.95      2245407.97     13352988.32
      2243993.03     13352224.42
#Sta/Elev= 30
  3097.2  139.69  3585.9  135.57  3910.7   135.9  4168.3  137.63  4246.8  137.15
  4272.4  134.76  4318.1  137.36  4409.7  135.05  4750.8  133.95  4867.9  139.01
  4906.9  131.28  4949.4  129.59    4964  123.62  4983.5  123.58  5008.6  123.41
  5011.4  122.91  5014.6  123.41  5042.2  124.43  5078.6  132.47  5091.6  135.38
  5173.5  136.05  5255.4  140.64  5362.2  139.85  5747.9  143.15  5964.4  143.02
  6053.1  142.68  6152.4  142.76  6270.4  142.53  6488.1  142.91  6596.6  143.12
#Mann= 13 ,-1 , 0
  3097.2     .05       0  3910.7      .1       0  4983.5     .07       0
  5008.6     .07       0  5014.6     .07       0  5078.6      .1       0
  5362.2     .05       0  5747.9      .1       0  5964.4     .05       0
  6053.1      .1       0  6152.4     .05       0  6270.4      .1       0
  6488.1     .05       0
Bank Sta=5008.6,5014.6
XS Rating Curve= 0 ,0
Exp/Cntr=0.3,0.1

Type RM Length L Ch R = 1 ,1177    ,209,209,209
BEGIN DESCRIPTION:
Mapping XS 60a651b7
END DESCRIPTION:
XS GIS Cut Line= 5
      2245850.68     13354845.97      2245624.98      13353083.8
      2245659.71     13352901.51      2245581.58     13352693.18
      2244166.64     13351964.01
#Sta/Elev= 30
  3025.7  139.61  3508.7  135.46  3840.6  134.96  4035.5  134.81  4194.8  136.85
  4446.3  135.06  4476.6  137.68  4496.7  134.53  4564.3  134.25  4567.1  133.75
  4570.3  134.25  4588.2  134.28  4607.6  138.34  4737.5  136.32  4839.2  139.12
  4896.5  139.13  4901.5  137.59  5063.5  139.69  5088.4  139.18  5093.7  137.69
  5148.9  139.08  5179.2  136.79  5204.1  138.22  5208.7  136.49  5233.3  136.22
  5410.6  140.25  5687.2  142.93  6683.3  143.13  6760.6  143.34  6802.1  143.45
#Mann= 6 ,-1 , 0
  3025.7     .05       0  3840.6      .1       0  4564.3     .07       0
  4570.3      .1       0  6683.3     .05       0  6760.6      .1       0
Bank Sta=4564.3,4570.3
XS Rating Curve= 0 ,0
Exp/Cntr=0.3,0.1

Type RM Length L Ch R = 1 ,968     ,0,0,0
BEGIN DESCRIPTION:
UNT007 IN SUCR 1.0
END DESCRIPTION:
XS GIS Cut Line= 3
       2245928.8     13354828.63        2245842.     13352389.36
      2244289.19     13351721.39
#Sta/Elev= 30
  3087.4  139.49  3439.4  135.97  3986.8  134.88  4113.1   134.8  4490.1   135.3
  4510.1  136.04  4520.1  135.02    4580  134.41  4960.4  132.15  5030.2  129.45
  5110.5  131.46  5226.1  130.85  5340.6  131.68  5420.7  133.49    5640  135.78
  5745.6  137.93  5957.5  140.57  6028.1  140.74  6051.6  139.54  6080.6  140.69
  6260.2  140.45  6358.8  141.23  6484.5  141.74    6508  143.01  6523.5  141.97
  6801.4     143    6907  142.86  6939.3  143.02  7151.4  143.19  7218.6  143.25
#Mann= 14 ,-1 , 0
  3087.4     .05       0  3986.8      .1       0  4113.1     .05       0
    4580      .1       0  4960.4     .03       0  5110.5      .1       0
    5640     .05       0  5745.6      .1       0  6260.2     .16       0
  6358.8      .1       0  6801.4     .05       0    6907      .1       0
  6939.3     .05       0  7151.4      .1       0
Bank Sta=4960.4,5110.5
XS Rating Curve= 0 ,0
Exp/Cntr=0.3,0.1

Chan Stop Cuts=-1
Use User Specified Reach Order=0
Composite Channel Slope=5