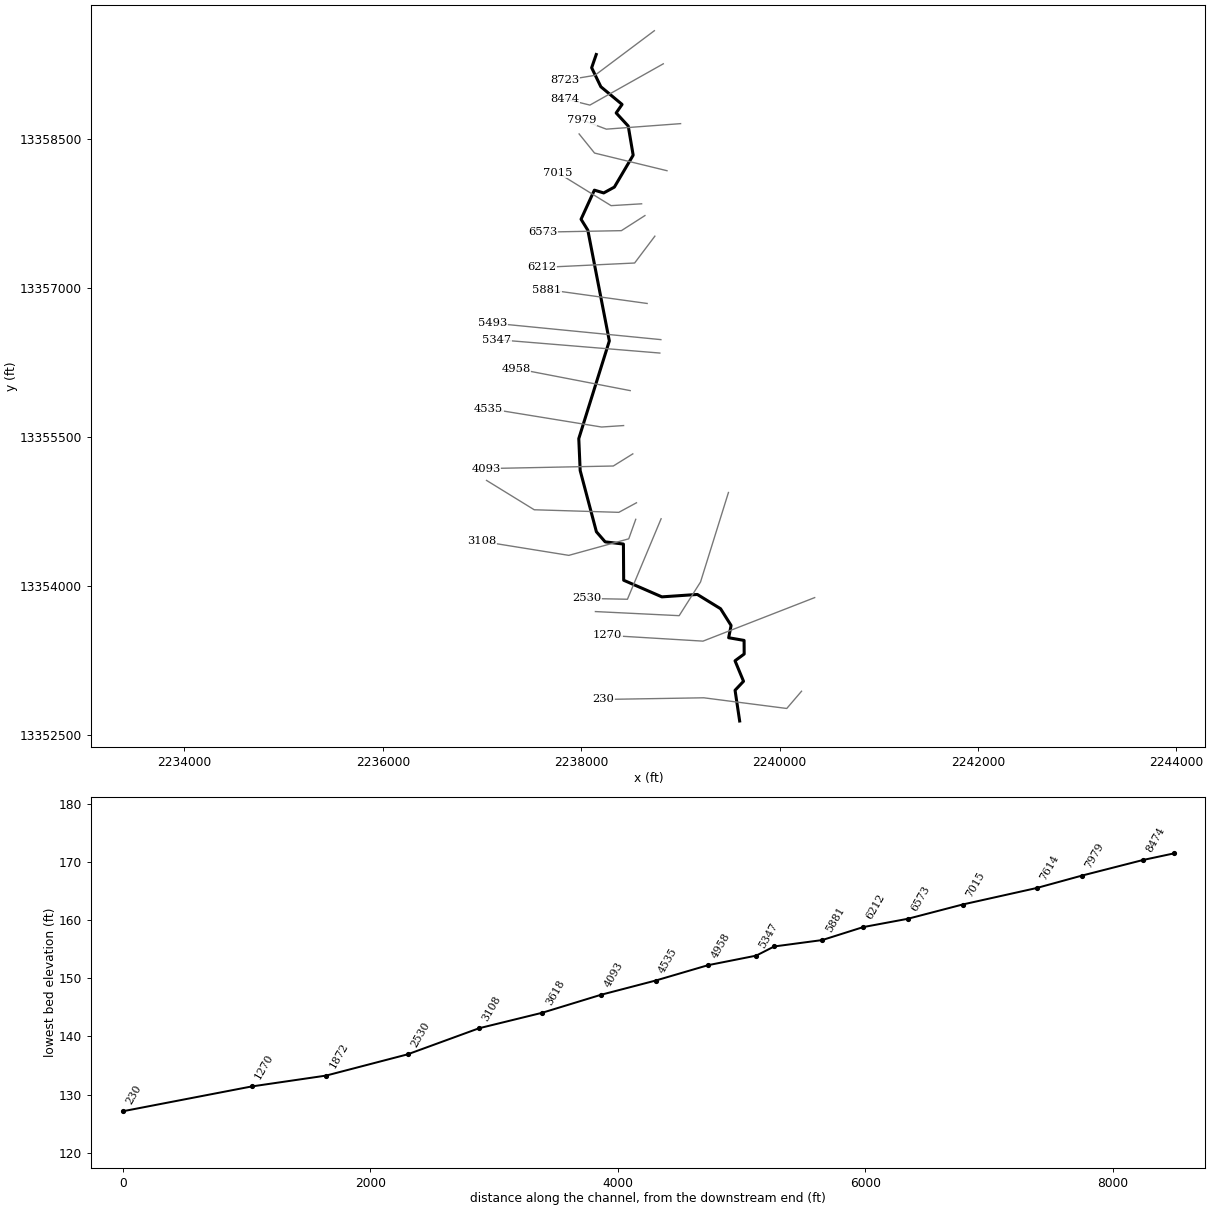
--- UNT009 IN SUCR.prj (project) ---

Proj Title=UNT009 IN SUCR Base Level Engineering
Current Plan=p01
Default Exp/Contr=0.3,0.1
English Units
Geom File=g01
Flow File=f01
Plan File=p01
Y Axis Title=Elevation
X Axis Title(PF)=Main Channel Distance
X Axis Title(XS)=Station
BEGIN DESCRIPTION:
UNT009 IN SUCR
END DESCRIPTION:
DSS Export Rating Curves= 0
DSS Export Rating Curve Sorted= 0
DSS Export Volume Flow Curves= 0
DXF OffsetX= 0
DXF OffsetY= 0
DXF ScaleX= 1
DXF ScaleY= 10

--- UNT009 IN SUCR.p01 (plan) ---

Plan Title=Multiple Run
Short Identifier=Multiple
Geom File=g01
Flow File=f01
Subcritical Flow
K Sum by GR= 0
Std Step Tol= 0.01
Critical Tol= 0.01
Num of Std Step Trials= 20
Max Error Tol= 0.3
Flow Tol Ratio= 0.001
Split Flow NTrial= 30
Split Flow Tol= 0.02
Split Flow Ratio= 0.02
Log Output Level= 0
Friction Slope Method= 1
Unsteady Friction Slope Method= 2
Unsteady Bridges Friction Slope Method= 1
Parabolic Critical Depth
Global Vel Dist=  1 , 1 , 1
Global Log Level= 0
CheckData=True
Encroach Param= -1, 0, 0, 0
BEGIN DESCRIPTION:
Multiple Run
END DESCRIPTION:

--- UNT009 IN SUCR.f01 (steady flow) ---

Flow Title=Multiple
Program Version=4.10
Number of Profiles= 7
Profile Names=10-year,25-year,50-year,1pct_min,100-year,1pct_plu,500-year
River Rch & RM=UNT009 IN SUCR,Reach-1         ,8723
     184     250     303     271     366     495     542
River Rch & RM=UNT009 IN SUCR,Reach-1         ,5347
     269     373     460     416     563     761     856
Boundary for River Rch & Prof#=UNT009 IN SUCR,Reach-1         , 1
Up Type= 0
Dn Type= 3
Dn Slope=0.005
Boundary for River Rch & Prof#=UNT009 IN SUCR,Reach-1         , 2
Up Type= 0
Dn Type= 3
Dn Slope=0.005
Boundary for River Rch & Prof#=UNT009 IN SUCR,Reach-1         , 3
Up Type= 0
Dn Type= 3
Dn Slope=0.005
Boundary for River Rch & Prof#=UNT009 IN SUCR,Reach-1         , 4
Up Type= 0
Dn Type= 3
Dn Slope=0.005
Boundary for River Rch & Prof#=UNT009 IN SUCR,Reach-1         , 5
Up Type= 0
Dn Type= 3
Dn Slope=0.005
Boundary for River Rch & Prof#=UNT009 IN SUCR,Reach-1         , 6
Up Type= 0
Dn Type= 3
Dn Slope=0.005
Boundary for River Rch & Prof#=UNT009 IN SUCR,Reach-1         , 7
Up Type= 0
Dn Type= 3
Dn Slope=0.005
DSS Import GetInterval= 0
DSS Import GetPeak= 0
DSS Import FillOption= 0

--- UNT009 IN SUCR.g01 (geometry) ---

Geom Title=Existing Conditions
Program Version=4.10

River Reach=UNT009 IN SUCR  ,Reach-1
Reach XY= 30
      2238151.57     13359356.93      2238105.45     13359223.46
      2238198.14     13359031.87      2238412.18     13358853.61
      2238352.58     13358767.67      2238474.26     13358635.39
      2238524.03     13358341.82      2238334.48     13358020.07
      2238227.08     13357961.19      2238132.94     13357989.29
      2237998.56     13357696.17      2238066.84     13357585.45
      2238283.69     13356469.09      2237975.64     13355483.99
      2237989.76     13355162.24      2238153.43     13354544.71
      2238241.55     13354443.13      2238425.76     13354420.91
      2238428.32     13354056.09      2238813.42     13353888.51
      2239170.94     13353912.84      2239405.44     13353768.76
      2239511.42     13353600.04      2239486.93     13353476.43
      2239642.39     13353449.41      2239643.37     13353312.22
      2239551.05     13353243.98      2239636.73     13353037.29
      2239551.44     13352946.63      2239597.72     13352636.85

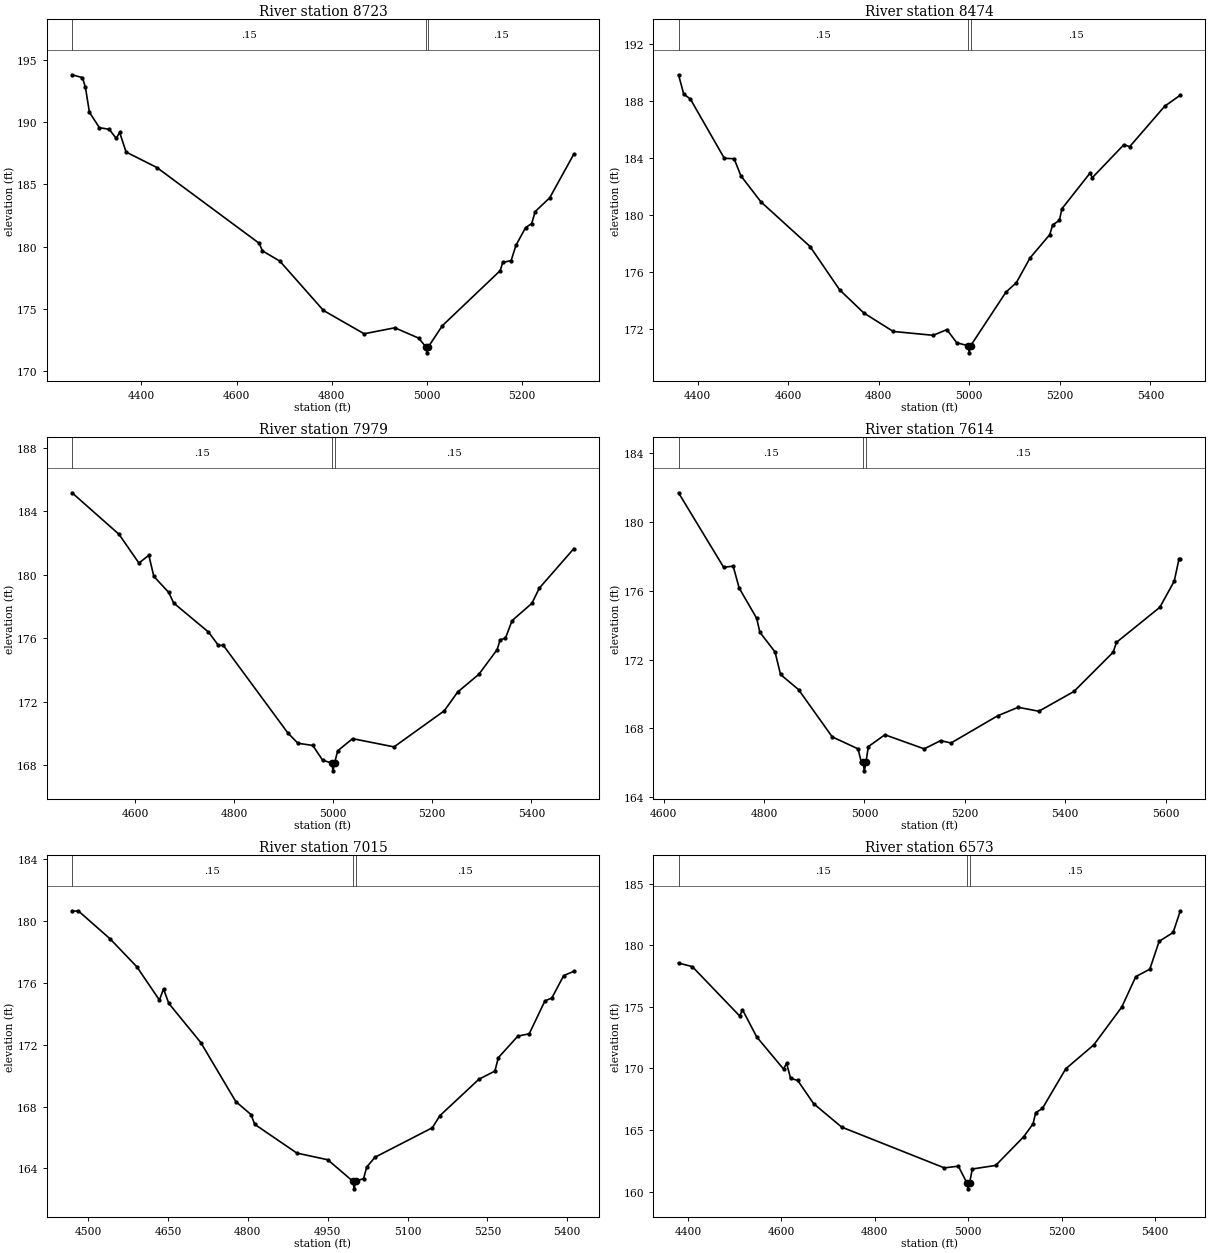
Type RM Length L Ch R = 1 ,8723    ,249,249,249
BEGIN DESCRIPTION:
UNT009 IN SUCR 18.0
END DESCRIPTION:
XS GIS Cut Line= 3
       2238737.7     13359596.84      2238137.72     13359146.85
      2237837.73     13359096.86
#Sta/Elev= 30
  4254.3  193.78  4276.1  193.55  4282.4  192.77  4290.7  190.78  4311.6  189.54
  4332.4   189.4    4347  188.68  4354.3  189.15  4367.8  187.58  4432.4  186.34
    4647  180.27  4654.3  179.65  4690.7  178.83  4782.4  174.87  4867.8     173
  4932.4  173.48  4982.4  172.65    4997  171.97  4999.8  171.47    5003  171.97
  5032.2  173.65  5153.8  178.07  5158.9  178.72  5176.6  178.87  5186.8   180.1
    5207  181.52  5219.7  181.84  5227.3  182.81  5257.7  183.91  5308.4  187.42
#Mann= 3 ,-1 , 0
  4254.3     .15       0    4997     .05       0    5003     .15       0
Bank Sta=4997,5003
XS Rating Curve= 0 ,0
Exp/Cntr=0.3,0.1

Type RM Length L Ch R = 1 ,8474    ,495,495,495
BEGIN DESCRIPTION:
UNT009 IN SUCR 17.0
END DESCRIPTION:
XS GIS Cut Line= 3
      2238827.78     13359263.14      2238087.72     13358846.85
       2237836.6     13358909.43
#Sta/Elev= 30
    4358  189.85  4369.5  188.49  4383.9  188.16  4459.1  183.99  4480.8  183.96
  4495.7  182.76    4540  180.93  4648.4   177.8  4713.7  174.76    4767  173.14
    4832  171.84  4920.3  171.57  4950.5  171.97  4972.2  171.05    4997  170.84
  4999.8  170.34    5003  170.84  5080.9   174.6  5103.8  175.26  5134.1     177
  5177.5  178.63  5184.2  179.32  5199.1  179.64  5204.2  180.44  5266.5  182.95
  5271.6  182.63  5341.1  184.94  5354.2  184.81  5431.6  187.65  5465.9  188.42
#Mann= 3 ,-1 , 0
    4358     .15       0    4997     .05       0    5003     .15       0
Bank Sta=4997,5003
XS Rating Curve= 0 ,0
Exp/Cntr=0.3,0.1

Type RM Length L Ch R = 1 ,7979    ,365,365,365
BEGIN DESCRIPTION:
UNT009 IN SUCR 16.0
END DESCRIPTION:
XS GIS Cut Line= 3
      2239002.22     13358659.87      2238253.29     13358604.26
      2238008.55     13358696.96
#Sta/Elev= 30
  4473.1  185.18  4567.9  182.56    4608  180.75    4628  181.24  4638.1  179.91
  4668.1   178.9  4678.2  178.23  4748.4   176.4  4768.4  175.56  4778.4  175.56
  4908.8  170.03  4928.9  169.39  4958.9  169.25    4979  168.31    4997  168.15
  4999.8  167.65    5003  168.15  5009.1  168.91  5039.2  169.68  5122.9  169.16
  5224.1  171.43  5251.4  172.62  5294.2  173.74  5330.9  175.29    5337  175.91
  5347.7  176.01  5361.1  177.12  5401.1  178.21  5416.1  179.17  5485.8  181.66
#Mann= 3 ,-1 , 0
  4473.1     .15       0    4997     .05       0    5003     .15       0
Bank Sta=4997,5003
XS Rating Curve= 0 ,0
Exp/Cntr=0.3,0.1

Type RM Length L Ch R = 1 ,7614    ,599,599,599
BEGIN DESCRIPTION:
UNT009 IN SUCR 15.0
END DESCRIPTION:
XS GIS Cut Line= 3
      2238865.11     13358185.27      2238134.64     13358363.25
       2237978.9     13358556.07
#Sta/Elev= 30
  4629.6  181.71  4719.5  177.37  4738.5  177.44  4750.4  176.16  4785.3   174.4
  4791.6  173.59  4821.9  172.44  4832.8  171.13  4868.7  170.25  4935.7   167.5
  4987.2   166.8  4993.8  166.02    4997  166.02  4999.8  165.52    5003  166.02
  5007.7  166.93  5040.7  167.62    5119   166.8  5151.8  167.28  5172.4  167.14
  5265.1  168.72  5306.2  169.22  5347.4  168.99  5417.3  170.14  5495.6  172.43
    5502     173  5588.4  175.04  5617.1  176.56  5626.6  177.84  5629.3  177.84
#Mann= 3 ,-1 , 0
  4629.6     .15       0    4997     .05       0    5003     .15       0
Bank Sta=4997,5003
XS Rating Curve= 0 ,0
Exp/Cntr=0.3,0.1

Type RM Length L Ch R = 1 ,7015    ,442,442,442
BEGIN DESCRIPTION:
UNT009 IN SUCR 14.0
END DESCRIPTION:
XS GIS Cut Line= 3
       2238609.2     13357851.57      2238301.49     13357833.03
      2237761.42     13358165.95
#Sta/Elev= 30
  4469.8  180.61  4481.3  180.65  4541.4  178.83  4591.5  177.03  4633.9  174.88
  4641.6   175.6  4651.6  174.66  4711.7  172.13  4777.4  168.32    4806  167.48
  4812.9  166.85  4892.1  164.99  4950.1  164.56    4997  163.18  4999.8  162.68
    5003  163.18  5017.4  163.34  5023.4  164.09  5038.8  164.72  5146.7  166.63
  5160.6   167.4    5234  169.76  5264.1  170.29  5270.7  171.16  5307.3  172.55
  5328.6   172.7  5358.1  174.82  5371.2  175.02  5393.4  176.46  5412.5  176.74
#Mann= 3 ,-1 , 0
  4469.8     .15       0    4997     .05       0    5003     .15       0
Bank Sta=4997,5003
XS Rating Curve= 0 ,0
Exp/Cntr=0.3,0.1

Type RM Length L Ch R = 1 ,6573    ,361,361,361
BEGIN DESCRIPTION:
UNT009 IN SUCR 13.0
END DESCRIPTION:
XS GIS Cut Line= 3
      2238642.57     13357732.89      2238405.31      13357580.9
      2237612.32     13357566.08
#Sta/Elev= 30
  4379.5  178.55    4409  178.26  4510.6  174.25  4516.5  174.76  4546.9  172.56
  4604.4  169.95  4610.9  170.42  4619.6  169.19  4634.7  169.03  4668.9  167.14
  4728.9  165.24  4948.9  161.93  4978.9  162.07    4997  160.73  4999.8  160.23
    5003  160.73  5008.9  161.84  5058.9  162.13  5118.9  164.46  5138.9   165.5
  5144.6  166.41  5158.9  166.75    5209  169.97    5269  171.91    5329  174.98
    5359  177.45    5389  178.05    5409  180.31    5439  181.03  5454.4  182.79
#Mann= 3 ,-1 , 0
  4379.5     .15       0    4997     .05       0    5003     .15       0
Bank Sta=4997,5003
XS Rating Curve= 0 ,0
Exp/Cntr=0.3,0.1

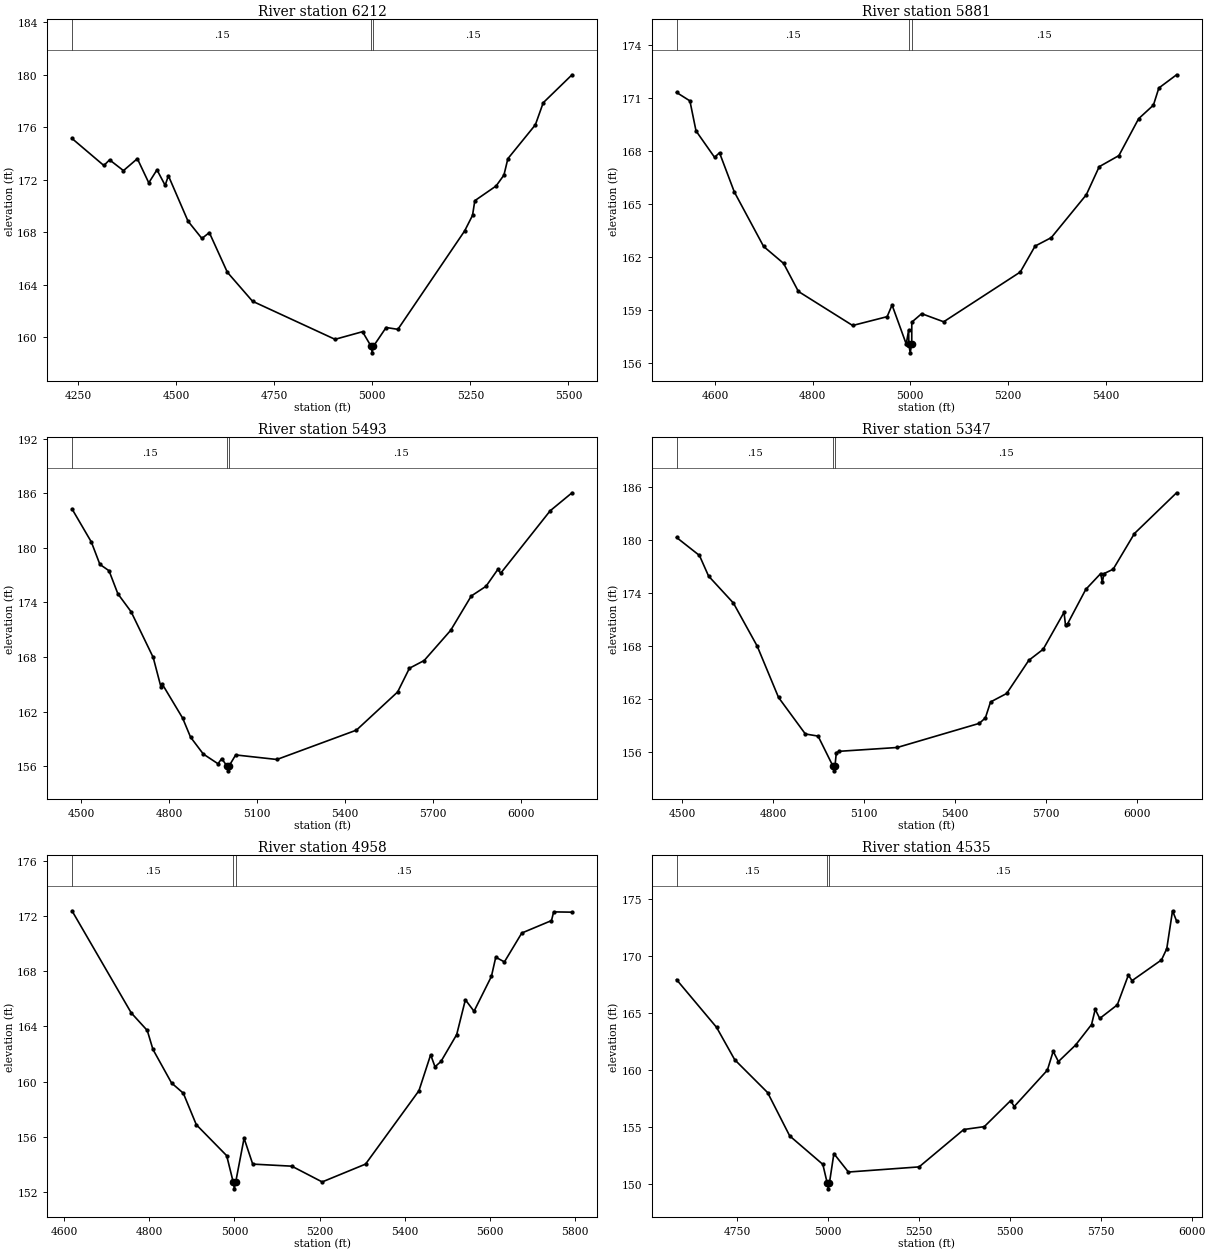
Type RM Length L Ch R = 1 ,6212    ,331,331,331
BEGIN DESCRIPTION:
UNT009 IN SUCR 12.0
END DESCRIPTION:
XS GIS Cut Line= 3
      2238742.71     13357525.27      2238538.79     13357254.61
      2237604.43     13357210.12
#Sta/Elev= 30
  4234.8  175.13    4316  173.07  4330.6   173.5    4366  172.68  4401.4  173.59
  4430.5  171.75  4451.4  172.74  4472.2  171.56  4480.5  172.29  4530.5  168.83
  4565.9  167.51  4584.8  167.96  4630.7  164.94  4694.9  162.73  4905.1  159.83
  4975.2  160.41    4997   159.3  4999.8   158.8    5003   159.3  5035.3  160.73
  5065.3  160.59  5235.5  168.09  5255.5  169.27  5261.4  170.39  5315.6  171.51
  5335.6  172.34  5345.6  173.59  5415.7  176.17  5435.7  177.85  5509.1  179.98
#Mann= 3 ,-1 , 0
  4234.8     .15       0    4997     .05       0    5003     .15       0
Bank Sta=4997,5003
XS Rating Curve= 0 ,0
Exp/Cntr=0.3,0.1

Type RM Length L Ch R = 1 ,5881    ,388,388,388
BEGIN DESCRIPTION:
UNT009 IN SUCR 11.0
END DESCRIPTION:
XS GIS Cut Line= 2
      2238664.87     13356846.75      2237650.78     13356987.39
#Sta/Elev= 30
  4521.4  171.33  4548.8  170.85  4561.3  169.15  4599.3  167.65  4609.4  167.91
  4639.7  165.69  4699.7   162.6  4740.6  161.64  4770.9  160.05    4882  158.12
  4952.6  158.62  4962.7  159.28  4991.7  157.07  4996.7  157.87    4997  157.07
  4999.8  156.57    5003  157.07  5003.1  158.31  5023.3  158.79  5068.4  158.33
  5225.2  161.15  5255.5  162.62  5288.7   163.1  5360.4  165.53  5386.8  167.12
  5427.1  167.75  5467.5  169.84  5497.8  170.61  5508.9  171.58  5545.2  172.33
#Mann= 3 ,-1 , 0
  4521.4     .15       0    4997     .05       0    5003     .15       0
Bank Sta=4997,5003
XS Rating Curve= 0 ,0
Exp/Cntr=0.3,0.1

Type RM Length L Ch R = 1 ,5493    ,146,146,146
BEGIN DESCRIPTION:
UNT009 IN SUCR 10.0
END DESCRIPTION:
XS GIS Cut Line= 2
      2238803.54     13356482.17       2237105.6     13356648.84
#Sta/Elev= 30
  4467.7   184.3  4533.8  180.65  4562.9  178.19  4594.1  177.49  4624.3  174.95
  4669.4  172.98  4744.8  167.95  4770.8  164.75  4775.8  165.01  4845.3  161.27
  4872.2  159.18  4915.7  157.32  4965.9  156.25  4978.7  156.82    4997  155.97
  4999.8  155.47    5003  155.97  5026.2  157.22  5166.9  156.72  5438.2  159.95
  5578.8  164.15    5619  166.76  5669.3  167.61  5759.7  170.93    5830  174.71
  5880.3  175.78  5920.5  177.63  5930.5  177.22  6099.3  184.09  6173.8  186.07
#Mann= 3 ,-1 , 0
  4467.7     .15       0    4997     .05       0    5003     .15       0
Bank Sta=4997,5003
XS Rating Curve= 0 ,0
Exp/Cntr=0.3,0.1

Type RM Length L Ch R = 1 ,5347    ,389,389,389
BEGIN DESCRIPTION:
Mapping XS 6c2c1ef1
END DESCRIPTION:
XS GIS Cut Line= 2
      2238793.07     13356346.76      2237149.23     13356482.01
#Sta/Elev= 30
  4480.5  180.29  4556.1  178.25  4586.2  175.92  4668.1  172.87  4746.7  167.99
    4817  162.19  4905.4  158.06  4947.4  157.82    4997  154.39  4999.8  153.89
    5003  154.39  5007.6  155.94  5017.7   156.1  5208.3  156.53  5479.2  159.26
  5499.3  159.88  5516.3  161.68  5569.5  162.64  5642.5  166.39  5689.9  167.64
  5758.7  171.82  5763.7  170.33  5770.2  170.51  5830.4  174.41  5879.8  176.21
  5884.9   175.2  5890.6   176.2  5920.7  176.69  5990.9  180.73  6129.9  185.34
#Mann= 3 ,-1 , 0
  4480.5     .15       0    4997     .05       0    5003     .15       0
Bank Sta=4997,5003
XS Rating Curve= 0 ,0
Exp/Cntr=0.3,0.1

Type RM Length L Ch R = 1 ,4958    ,423,423,423
BEGIN DESCRIPTION:
UNT009 IN SUCR 9.0
END DESCRIPTION:
XS GIS Cut Line= 2
      2238494.28       13355968.      2237341.92     13356190.32
#Sta/Elev= 30
  4618.7  172.37  4757.8  164.98  4795.4  163.71  4808.7  162.34  4852.4  159.91
    4880  159.17  4910.5  156.89  4981.8  154.65    4997  152.75  4999.8  152.25
    5003  152.75  5022.6  155.91  5042.9  154.04  5134.6  153.89  5205.9  152.75
  5307.7  154.04    5433  159.35  5460.5  161.95  5470.7  161.08  5484.8  161.47
  5521.6  163.41    5542  165.93  5562.3   165.1  5603.1  167.62  5613.3  169.01
  5633.6  168.67  5674.4  170.76  5744.1  171.66  5749.2  172.29  5792.3  172.27
#Mann= 3 ,-1 , 0
  4618.7     .15       0    4997     .05       0    5003     .15       0
Bank Sta=4997,5003
XS Rating Curve= 0 ,0
Exp/Cntr=0.3,0.1

Type RM Length L Ch R = 1 ,4535    ,442,442,442
BEGIN DESCRIPTION:
UNT009 IN SUCR 8.0
END DESCRIPTION:
XS GIS Cut Line= 3
      2238427.57     13355615.75      2238205.09     13355600.92
      2237066.77     13355786.31
#Sta/Elev= 30
  4582.2  167.91  4692.3  163.74  4742.4   160.9  4832.9  158.03  4893.7  154.24
  4984.9  151.75    4997  150.11  4999.8  149.61    5003  150.11  5015.3  152.69
  5055.3  151.08  5249.9  151.53  5372.9   154.8  5429.3  155.05  5501.6  157.32
  5511.7  156.81  5602.9  159.99  5618.9  161.64  5633.3  160.74  5680.4  162.18
  5724.5  163.98  5734.6  165.31    5747  164.51  5795.4   165.7  5825.8   168.3
    5836  167.82    5917  169.63  5931.5  170.61  5947.4  173.93  5958.5  173.04
#Mann= 3 ,-1 , 0
  4582.2     .15       0    4997     .05       0    5003     .15       0
Bank Sta=4997,5003
XS Rating Curve= 0 ,0
Exp/Cntr=0.3,0.1

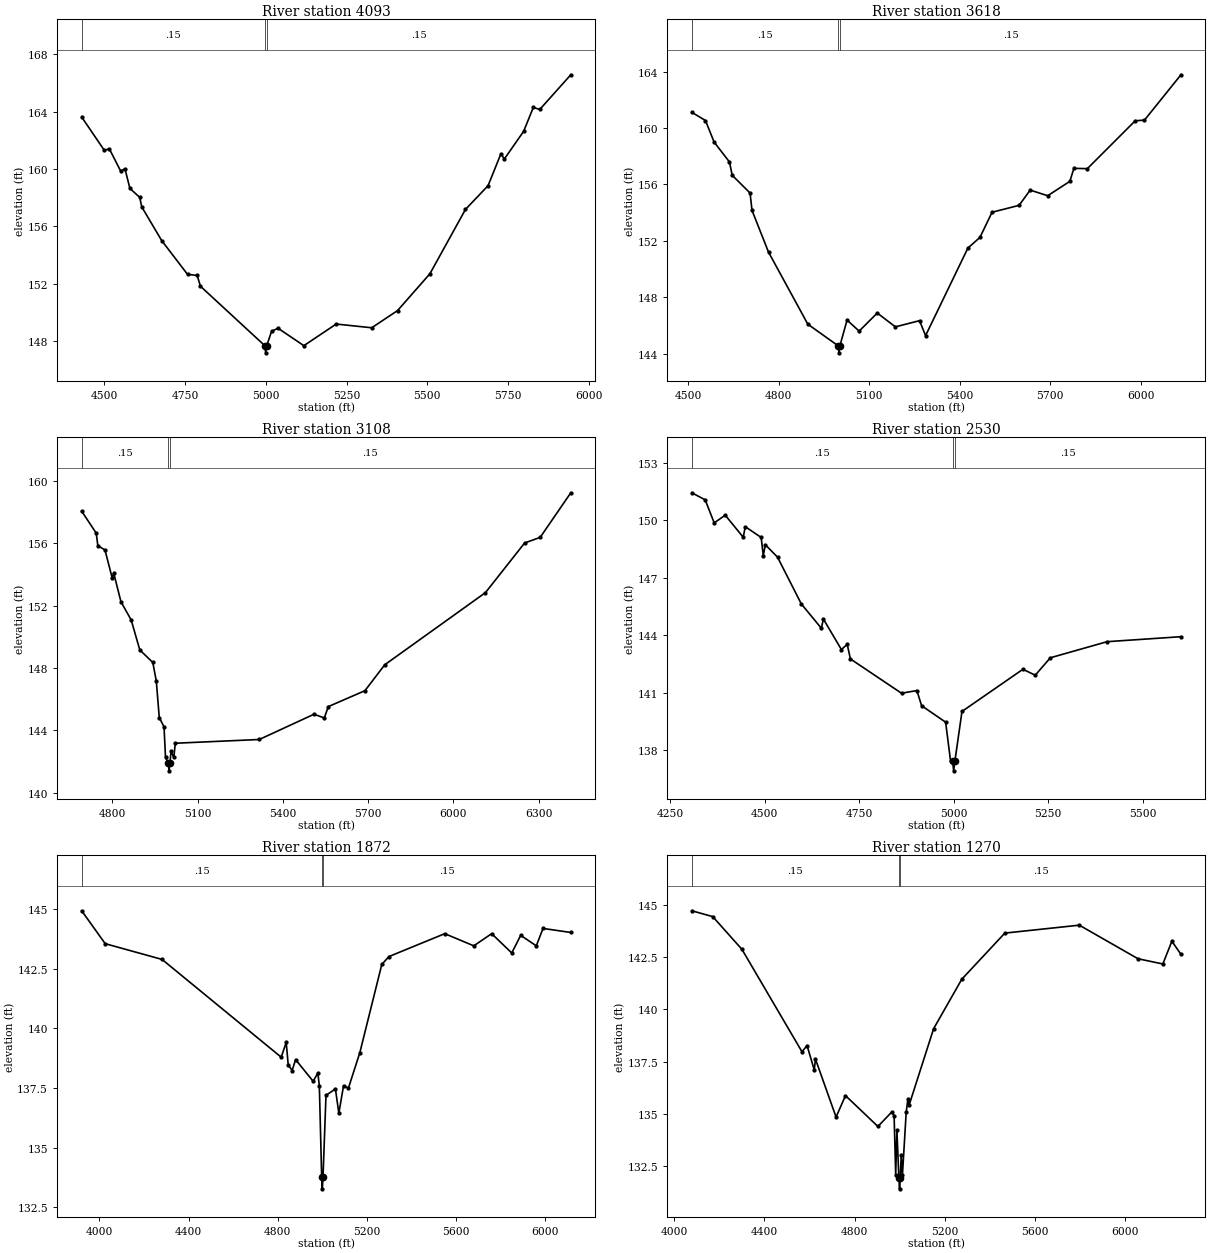
Type RM Length L Ch R = 1 ,4093    ,475,475,475
BEGIN DESCRIPTION:
UNT009 IN SUCR 7.0
END DESCRIPTION:
XS GIS Cut Line= 3
      2238520.23     13355330.23      2238323.74     13355207.89
      2237041.76     13355181.96
#Sta/Elev= 30
  4430.3  163.62  4500.5  161.29  4515.7  161.41  4551.1  159.84  4564.2  160.01
  4579.5  158.64    4610  158.01  4616.1  157.35  4677.8     155  4757.8  152.64
  4787.8  152.56  4797.8  151.81    4997  147.66  4999.8  147.16    5003  147.66
  5017.9  148.66  5037.9  148.88  5117.9  147.66  5217.9  149.17  5327.9  148.91
  5407.9  150.11    5508  152.68    5618  157.17    5688  158.83    5728  161.07
    5738  160.68    5798  162.62    5828  164.29    5848  164.15    5944  166.57
#Mann= 3 ,-1 , 0
  4430.3     .15       0    4997     .05       0    5003     .15       0
Bank Sta=4997,5003
XS Rating Curve= 0 ,0
Exp/Cntr=0.3,0.1

Type RM Length L Ch R = 1 ,3618    ,510,510,510
BEGIN DESCRIPTION:
UNT009 IN SUCR 6.0
END DESCRIPTION:
XS GIS Cut Line= 4
      2238557.37     13354837.13      2238379.35     13354740.71
      2237526.55     13354766.66      2237045.66     13355062.59
#Sta/Elev= 30
  4512.5  161.11  4557.6  160.53  4586.3     159  4637.2  157.59  4646.2  156.65
  4705.4  155.39  4711.8  154.16  4766.6   151.2  4896.7   146.1    4997  144.57
  4999.8  144.07    5003  144.57  5026.7  146.39  5066.7  145.61  5126.8  146.89
  5186.8  145.91  5266.8  146.35  5286.8  145.29  5426.9  151.49  5466.9  152.25
    5507  154.03  5596.6  154.52  5633.3   155.6  5691.3   155.2  5764.7  156.22
  5778.1  157.14  5822.7  157.12  5981.2  160.51    6012  160.56  6132.8  163.77
#Mann= 3 ,-1 , 0
  4512.5     .15       0    4997     .05       0    5003     .15       0
Bank Sta=4997,5003
XS Rating Curve= 0 ,0
Exp/Cntr=0.3,0.1

Type RM Length L Ch R = 1 ,3108    ,578,578,578
BEGIN DESCRIPTION:
UNT009 IN SUCR 5.0
END DESCRIPTION:
XS GIS Cut Line= 4
      2238549.93      13354670.3      2238479.47     13354473.74
      2237875.09     13354306.89      2237001.43     13354447.56
#Sta/Elev= 30
  4692.5  158.06  4743.7  156.65  4749.3  155.85  4774.5  155.57  4799.9  153.77
  4805.2  154.09  4830.7  152.25  4866.7  151.08    4897  149.16  4942.7  148.36
    4955  147.17  4965.4  144.83  4982.2  144.23  4987.4  142.27    4997  141.91
  4999.8  141.41    5003  141.91  5006.9  142.66  5016.6  142.27  5021.8  143.18
  5317.3  143.42  5509.8  145.04  5545.9   144.8  5560.3  145.53    5689  146.55
  5758.6  148.21  6113.1  152.84  6250.7  156.02  6305.5  156.38  6413.2  159.24
#Mann= 3 ,-1 , 0
  4692.5     .15       0    4997     .05       0    5003     .15       0
Bank Sta=4997,5003
XS Rating Curve= 0 ,0
Exp/Cntr=0.3,0.1

Type RM Length L Ch R = 1 ,2530    ,658,658,658
BEGIN DESCRIPTION:
UNT009 IN SUCR 4.0
END DESCRIPTION:
XS GIS Cut Line= 3
       2238805.7     13354675.91       2238466.2     13353864.43
      2238052.42     13353872.71
#Sta/Elev= 30
  4307.4  151.43  4342.7  151.06  4366.5  149.86  4395.7  150.26  4443.3  149.11
  4448.7  149.66  4490.7   149.1  4496.3  148.15  4501.7  148.72    4534  148.07
  4596.9  145.63  4649.9  144.36  4655.3  144.84  4702.9  143.25  4718.3  143.52
  4726.7  142.76  4861.9  140.97  4902.6  141.11  4914.9  140.32  4978.5  139.46
  4991.7  137.42    4997  137.42  4999.8  136.92    5003  137.42  5021.8  140.02
    5183  142.22  5215.5  141.91  5255.5  142.82  5405.6  143.66  5600.9  143.92
#Mann= 3 ,-1 , 0
  4307.4     .15       0    4997     .05       0    5003     .15       0
Bank Sta=4997,5003
XS Rating Curve= 0 ,0
Exp/Cntr=0.3,0.1

Type RM Length L Ch R = 1 ,1872    ,602,602,602
BEGIN DESCRIPTION:
UNT009 IN SUCR 3.0
END DESCRIPTION:
XS GIS Cut Line= 4
      2239484.67     13354940.86      2239203.15     13354038.32
      2238987.86     13353698.83       2238143.3     13353740.23
#Sta/Elev= 30
    3921  144.93  4026.5  143.55  4281.4  142.89  4815.6  138.79    4838  139.41
    4847  138.47  4864.6  138.23    4880  138.69  4958.8  137.78    4980  138.13
  4986.6  137.58    4997  133.77  4999.8  133.27    5003  133.77  5016.4  137.19
  5058.7  137.46    5074  136.44  5095.2   137.6  5116.8  137.49  5168.1  138.98
  5266.6  142.68  5298.6  143.01  5548.9  143.97  5679.1  143.46  5759.2  143.97
  5849.3  143.16  5889.3   143.9  5959.4  143.46  5989.4  144.19    6114  144.02
#Mann= 3 ,-1 , 0
    3921     .15       0    4997     .05       0    5003     .15       0
Bank Sta=4997,5003
XS Rating Curve= 0 ,0
Exp/Cntr=0.3,0.1

Type RM Length L Ch R = 1 ,1270    ,1040,1040,1040
BEGIN DESCRIPTION:
UNT009 IN SUCR 2.0
END DESCRIPTION:
XS GIS Cut Line= 3
      2240354.13       13353881.      2239227.99     13353442.14
      2238267.47      13353500.1
#Sta/Elev= 30
    4078  144.73  4170.7  144.45  4300.4  142.88  4566.9  137.97  4589.3  138.27
  4621.3   137.1  4626.7  137.62  4718.1  134.84  4759.9  135.87  4903.9  134.39
    4965  135.08  4975.7   134.9  4982.8  132.08  4988.1   134.2    4997   131.9
  4999.8   131.4    5003   131.9  5007.3  133.03  5012.6  132.05  5029.3  135.06
  5037.1  135.72  5042.5  135.42  5151.2  139.08  5276.2  141.45  5467.2  143.66
  5797.8  144.04  6058.3  142.43  6168.5  142.18  6208.6  143.27  6248.9  142.64
#Mann= 3 ,-1 , 0
    4078     .15       0    4997     .05       0    5003     .15       0
Bank Sta=4997,5003
XS Rating Curve= 0 ,0
Exp/Cntr=0.3,0.1

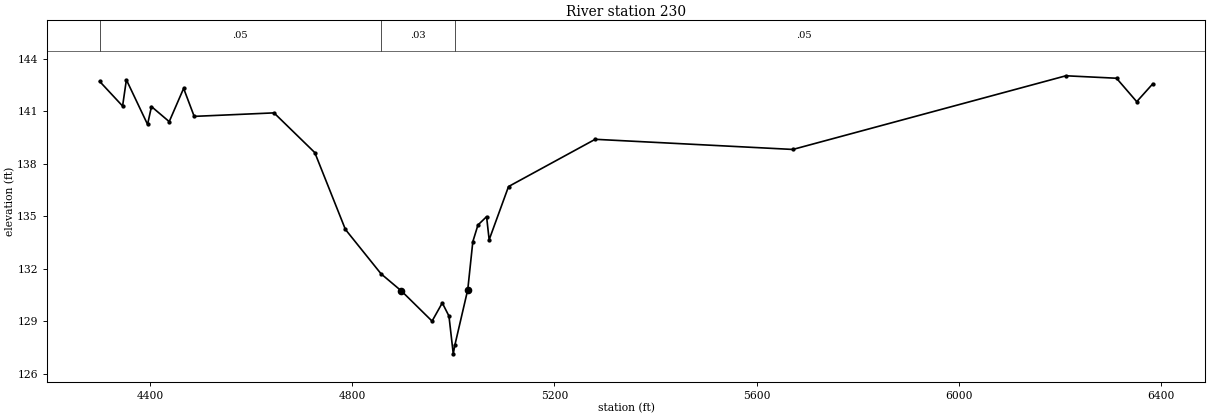
Type RM Length L Ch R = 1 ,230     ,0,0,0
BEGIN DESCRIPTION:
UNT009 IN SUCR 1.0
END DESCRIPTION:
XS GIS Cut Line= 4
      2240221.63     13352937.04      2240072.58     13352763.15
      2239236.27      13352870.8      2238226.04     13352854.24
#Sta/Elev= 30
  4300.5  142.71  4345.9   141.3  4353.4   142.8  4395.3  140.25    4403  141.27
  4438.1  140.41  4466.6  142.31  4487.5  140.71  4645.3  140.91    4726  138.64
  4786.5  134.25  4857.1  131.71  4897.4  130.73  4957.9  129.01  4978.1  130.05
  4991.3   129.3  4999.8  127.14    5003  127.64  5028.5  130.81  5038.5  133.55
  5048.6   134.5  5065.7  134.98  5070.8  133.66  5109.1   136.7  5280.5   139.4
  5671.3  138.82  6211.4  143.03  6311.4  142.89  6351.4  141.55  6383.1  142.57
#Mann= 3 ,-1 , 0
  4300.5     .05       0  4857.1     .03       0    5003     .05       0
Bank Sta=4897.4,5028.5
XS Rating Curve= 0 ,0
Exp/Cntr=0.3,0.1

Chan Stop Cuts=-1
Use User Specified Reach Order=0
Composite Channel Slope=5