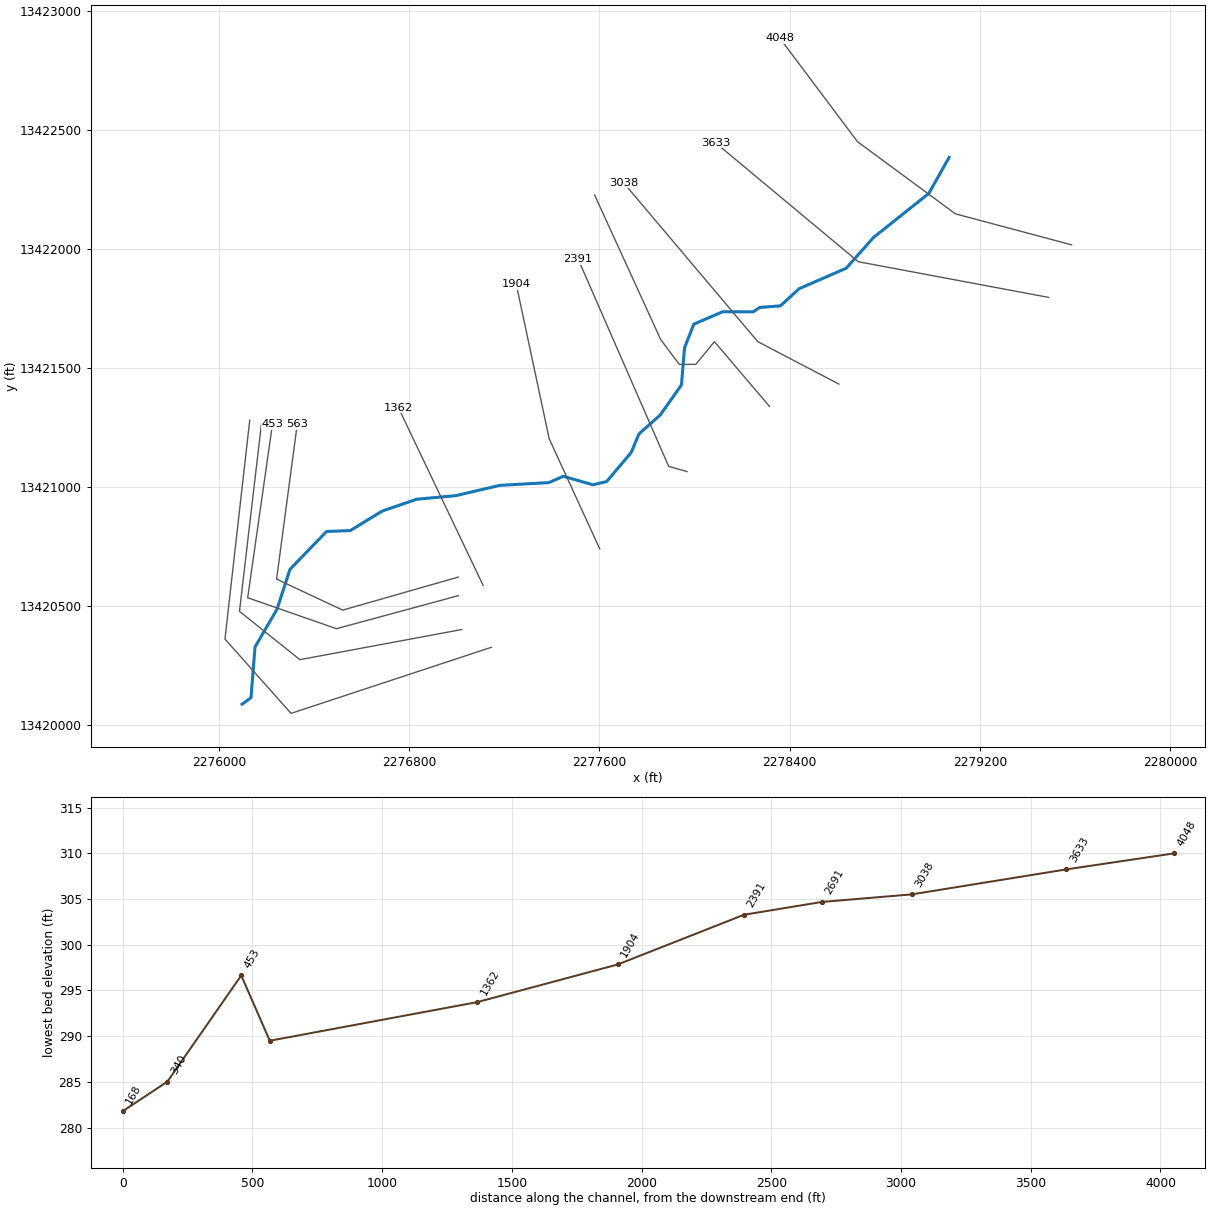
--- UNT010 IN SUCR.prj (project) ---

Proj Title=UNT010 IN SUCR Base Level Engineering
Current Plan=p01
Default Exp/Contr=0.3,0.1
English Units
Geom File=g01
Flow File=f01
Plan File=p01
Y Axis Title=Elevation
X Axis Title(PF)=Main Channel Distance
X Axis Title(XS)=Station
BEGIN DESCRIPTION:
UNT010 IN SUCR
END DESCRIPTION:
DSS Export Rating Curves= 0
DSS Export Rating Curve Sorted= 0
DSS Export Volume Flow Curves= 0
DXF OffsetX= 0
DXF OffsetY= 0
DXF ScaleX= 1
DXF ScaleY= 10

--- UNT010 IN SUCR.p01 (plan) ---

Plan Title=Multiple Run
Short Identifier=Multiple
Geom File=g01
Flow File=f01
Subcritical Flow
K Sum by GR= 0
Std Step Tol= 0.01
Critical Tol= 0.01
Num of Std Step Trials= 20
Max Error Tol= 0.3
Flow Tol Ratio= 0.001
Split Flow NTrial= 30
Split Flow Tol= 0.02
Split Flow Ratio= 0.02
Log Output Level= 0
Friction Slope Method= 1
Unsteady Friction Slope Method= 2
Unsteady Bridges Friction Slope Method= 1
Parabolic Critical Depth
Global Vel Dist=  1 , 1 , 1
Global Log Level= 0
CheckData=True
Encroach Param= -1, 0, 0, 0
BEGIN DESCRIPTION:
Multiple Run
END DESCRIPTION:

--- UNT010 IN SUCR.f01 (steady flow) ---

Flow Title=Multiple
Number of Profiles=7
Profile Names=10-year,25-year,50-year,1pct_min,100-year,1pct_plu,500-year
River Rch & RM= UNT010 IN SUCR,Reach-1,4048
     113     148     176     155     209     283     299
Boundary for River Rch & Prof#=UNT010 IN SUCR,Reach-1,1
Up Type=0
Dn Type=3
Dn Slope=0.005
Boundary for River Rch & Prof#=UNT010 IN SUCR,Reach-1,2
Up Type=0
Dn Type=3
Dn Slope=0.005
Boundary for River Rch & Prof#=UNT010 IN SUCR,Reach-1,3
Up Type=0
Dn Type=3
Dn Slope=0.005
Boundary for River Rch & Prof#=UNT010 IN SUCR,Reach-1,4
Up Type=0
Dn Type=3
Dn Slope=0.005
Boundary for River Rch & Prof#=UNT010 IN SUCR,Reach-1,5
Up Type=0
Dn Type=3
Dn Slope=0.005
Boundary for River Rch & Prof#=UNT010 IN SUCR,Reach-1,6
Up Type=0
Dn Type=3
Dn Slope=0.005
Boundary for River Rch & Prof#=UNT010 IN SUCR,Reach-1,7
Up Type=0
Dn Type=3
Dn Slope=0.005

--- UNT010 IN SUCR.g01 (geometry) ---

Geom Title=Existing Conditions
Program Version=4.10

River Reach=UNT010 IN SUCR  ,Reach-1
Reach XY= 30
      2279069.62     13422385.27      2278984.06     13422233.67
      2278751.95     13422048.89      2278636.81     13421919.28
      2278439.56      13421833.6      2278360.64     13421761.28
      2278273.57      13421754.7      2278246.24     13421736.14
      2278117.96     13421736.59      2277996.44      13421684.5
      2277957.37     13421584.68      2277944.56     13421428.93
      2277855.38     13421302.56      2277765.85      13421222.9
      2277732.74     13421144.19      2277629.78     13421022.49
      2277571.92     13421009.12      2277447.82     13421044.89
      2277387.18     13421018.35      2277181.13     13421006.81
      2276996.65     13420963.58      2276831.72     13420948.39
      2276686.32     13420898.48      2276552.43     13420816.68
      2276452.82     13420812.98      2276299.17     13420654.12
      2276244.48     13420486.15      2276152.04      13420327.3
      2276135.08      13420114.1      2276097.72     13420086.85

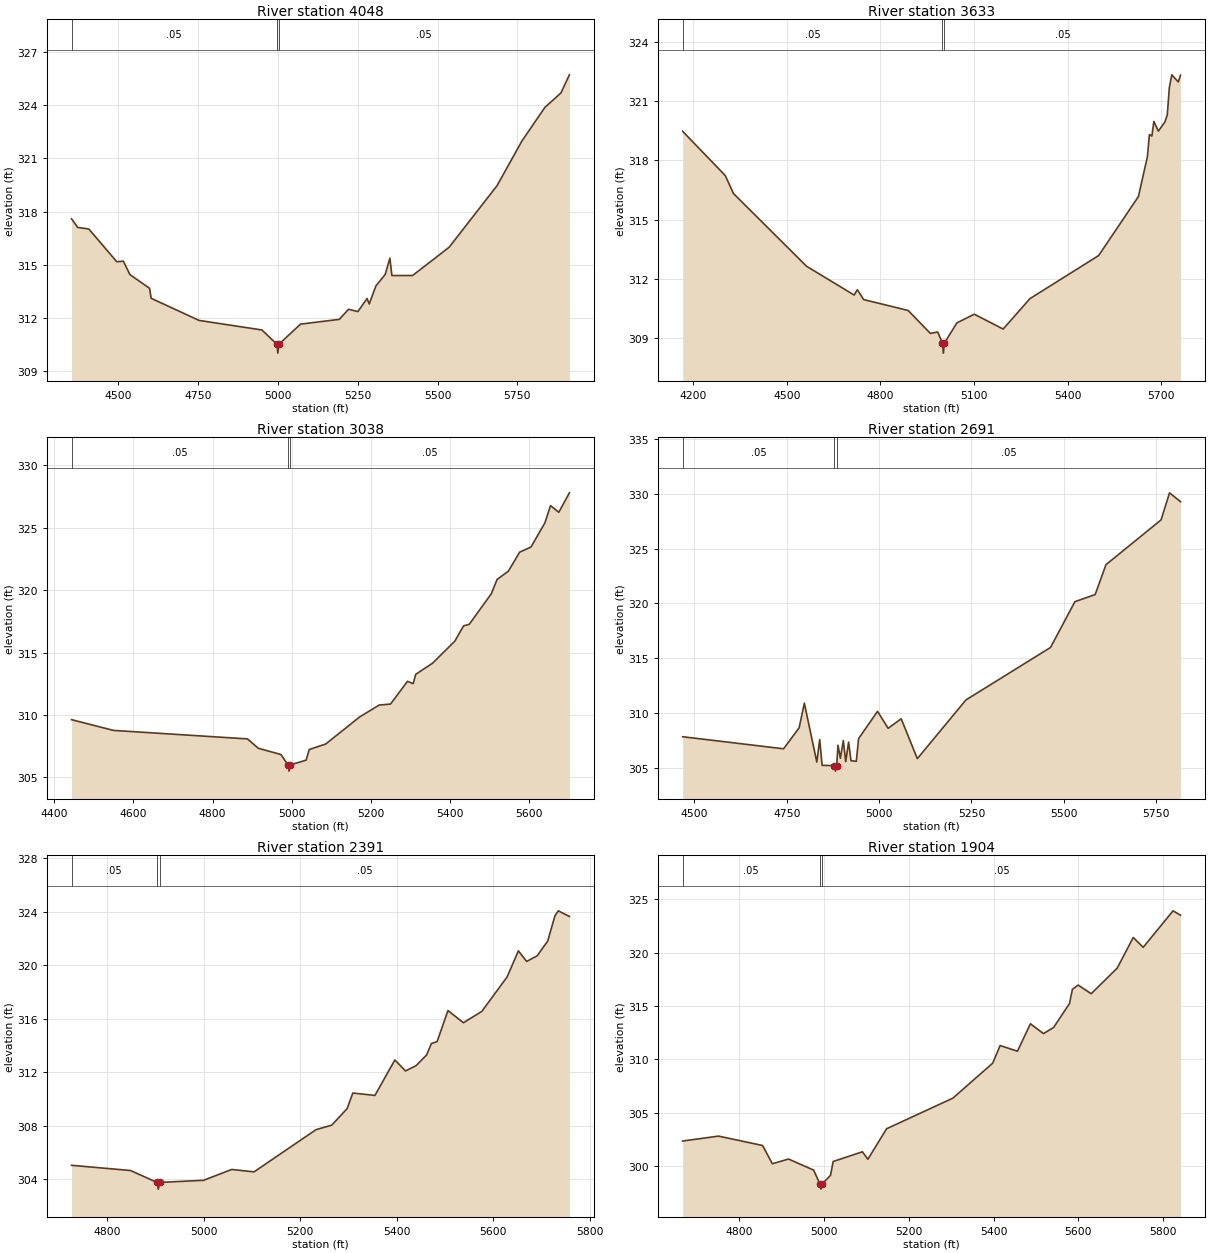
Type RM Length L Ch R = 1 ,4048    ,415,415,415
BEGIN DESCRIPTION:
UNT010 IN SUCR 7.0
END DESCRIPTION:
XS GIS Cut Line= 4
      2279584.56     13422017.77      2279096.28     13422147.98
      2278683.96      13422451.8      2278358.46     13422885.79
#Sta/Elev= 30
  4353.2  317.59  4372.4   317.1  4407.4  317.01  4494.8  315.16  4515.5  315.19
  4536.2  314.43  4597.5  313.66  4602.7  313.09  4752.8  311.84  4949.6   311.3
  4996.8  310.49  4999.5  309.99  5002.8  310.49  5070.7  311.63  5192.1   311.9
  5221.1  312.47  5250.4  312.34  5279.1  313.08  5285.9  312.77  5306.8  313.79
    5336  314.44  5350.7  315.36  5356.9  314.38  5421.8  314.38  5536.4  315.98
  5686.4  319.46  5764.5  321.99  5836.4  323.89  5886.4   324.7  5913.2  325.73
#Mann= 3 ,-1 , 0
  4353.2     .05       0  4996.8    .035       0  5002.8     .05       0
Bank Sta=4996.8,5002.8
XS Rating Curve= 0 ,0
Exp/Cntr=0.3,0.1

Type RM Length L Ch R = 1 ,3633    ,595,595,595
BEGIN DESCRIPTION:
UNT010 IN SUCR 6.0
END DESCRIPTION:
XS GIS Cut Line= 3
      2279487.71     13421796.86      2278687.72     13421946.85
      2278087.69     13422446.88
#Sta/Elev= 30
  4166.7  319.47  4303.2  317.23  4329.5  316.32  4563.5  312.64  4716.1  311.18
  4726.3  311.45  4746.6  310.95  4889.1   310.4  4960.3  309.24  4983.9  309.31
  4999.1  308.74  5001.9  308.24  5005.1  308.74  5045.1  309.77    5101  310.21
  5193.5  309.46  5279.4     311  5499.4  313.18  5626.9  316.17  5655.6  318.19
  5662.1  319.31  5669.9  319.23  5676.4  319.97  5690.7  319.48  5711.5  319.94
  5719.3   320.3  5725.9  321.69  5733.7  322.33  5754.5  321.97  5761.7  322.31
#Mann= 3 ,-1 , 0
  4166.7     .05       0  4999.1    .035       0  5005.1     .05       0
Bank Sta=4999.1,5005.1
XS Rating Curve= 0 ,0
Exp/Cntr=0.3,0.1

Type RM Length L Ch R = 1 ,3038    ,347,347,347
BEGIN DESCRIPTION:
UNT010 IN SUCR 5.0
END DESCRIPTION:
XS GIS Cut Line= 3
      2278606.26     13421432.57       2278265.3     13421610.82
      2277701.87     13422278.26
#Sta/Elev= 30
  4443.8  309.63  4549.8  308.77  4888.4  308.09  4915.8  307.34    4973  306.84
  4990.8  306.01  4993.5  305.51  4996.8  306.01  5036.7  306.39  5044.4  307.24
  5086.1  307.68  5171.9  309.85  5221.3   310.8  5249.9  310.88  5292.8   312.7
  5307.1  312.51  5313.6  313.26  5356.5  314.16  5412.5  315.92  5434.5  317.14
  5448.8  317.26  5504.8  319.72  5519.1  320.85  5547.7  321.52  5576.3  323.04
  5604.8  323.45    5640  325.38  5654.3  326.77  5675.1  326.23    5702  327.79
#Mann= 3 ,-1 , 0
  4443.8     .05       0  4990.8     .03       0  4996.8     .05       0
Bank Sta=4990.8,4996.8
XS Rating Curve= 0 ,0
Exp/Cntr=0.3,0.1

Type RM Length L Ch R = 1 ,2691    ,300,300,300
BEGIN DESCRIPTION:
Mapping XS 6a33b66f
END DESCRIPTION:
XS GIS Cut Line= 6
      2278314.64     13421338.78      2278083.01     13421610.82
      2278004.88     13421515.33      2277935.44     13421515.33
      2277857.31      13421619.5      2277579.55      13422227.1
#Sta/Elev= 30
    4468  307.82  4741.3  306.72  4783.4  308.63  4797.6  310.88  4831.3  305.51
  4839.2  307.56  4845.7  305.21  4879.1  305.18  4881.8  304.68  4885.1  305.18
  4888.7  307.04  4895.2  305.86  4903.1  307.47  4909.6  305.54  4917.4  307.33
  4923.9  305.63  4938.3  305.58  4944.5  307.65  4995.8  310.14  5024.5  308.59
  5059.9  309.46  5103.6  305.82  5235.2  311.18  5464.3  315.97  5530.3  320.15
  5585.2   320.8  5614.5  323.53  5763.7  327.62  5786.7  330.09  5816.4  329.28
#Mann= 3 ,-1 , 0
    4468     .05       0  4879.1     .03       0  4885.1     .05       0
Bank Sta=4879.1,4885.1
XS Rating Curve= 0 ,0
Exp/Cntr=0.3,0.1

Type RM Length L Ch R = 1 ,2391    ,487,487,487
BEGIN DESCRIPTION:
UNT010 IN SUCR 4.0
END DESCRIPTION:
XS GIS Cut Line= 3
      2277968.18     13421064.68      2277890.82     13421086.59
      2277510.09     13421958.05
#Sta/Elev= 30
  4726.3  305.06  4848.5  304.67  4903.3  303.78    4906  303.28  4909.3  303.78
  4999.9  303.94    5058  304.75  5104.4  304.57  5232.6  307.72  5265.3  308.06
  5297.1  309.29    5309  310.46  5354.8  310.28  5396.1  312.93  5418.1  312.11
  5439.9   312.5  5461.8   313.3  5471.8  314.16  5483.6   314.3  5506.1  316.62
  5538.1  315.71  5576.3  316.56  5628.6  319.13    5652  321.08  5669.1  320.29
  5690.9  320.71  5712.7  321.81  5727.6  323.69  5734.6  324.07  5757.7  323.65
#Mann= 3 ,-1 , 0
  4726.3     .05       0  4903.3     .03       0  4909.3     .05       0
Bank Sta=4903.3,4909.3
XS Rating Curve= 0 ,0
Exp/Cntr=0.3,0.1

Type RM Length L Ch R = 1 ,1904    ,542,542,542
BEGIN DESCRIPTION:
UNT010 IN SUCR 3.0
END DESCRIPTION:
XS GIS Cut Line= 3
      2277601.06     13420739.88      2277388.56     13421202.83
      2277249.88     13421852.91
#Sta/Elev= 30
  4666.7  302.35  4751.4  302.81  4855.2  301.93  4878.2  300.22  4916.4  300.66
  4975.7  299.62  4990.1  298.34  4992.9  297.84  4996.1  298.34  5015.5  299.14
  5021.6  300.43  5090.6  301.34  5103.5  300.64  5147.6   303.5    5304  306.37
  5397.9  309.65  5415.4   311.3  5456.3  310.77  5486.8  313.34  5517.6  312.42
  5541.4  312.99    5579  315.24  5585.8  316.57  5599.4  316.97  5630.1  316.16
  5691.5  318.56  5729.3  321.43  5752.8  320.51  5823.2  323.93  5840.8  323.52
#Mann= 3 ,-1 , 0
  4666.7     .05       0  4990.1     .03       0  4996.1     .05       0
Bank Sta=4990.1,4996.1
XS Rating Curve= 0 ,0
Exp/Cntr=0.3,0.1

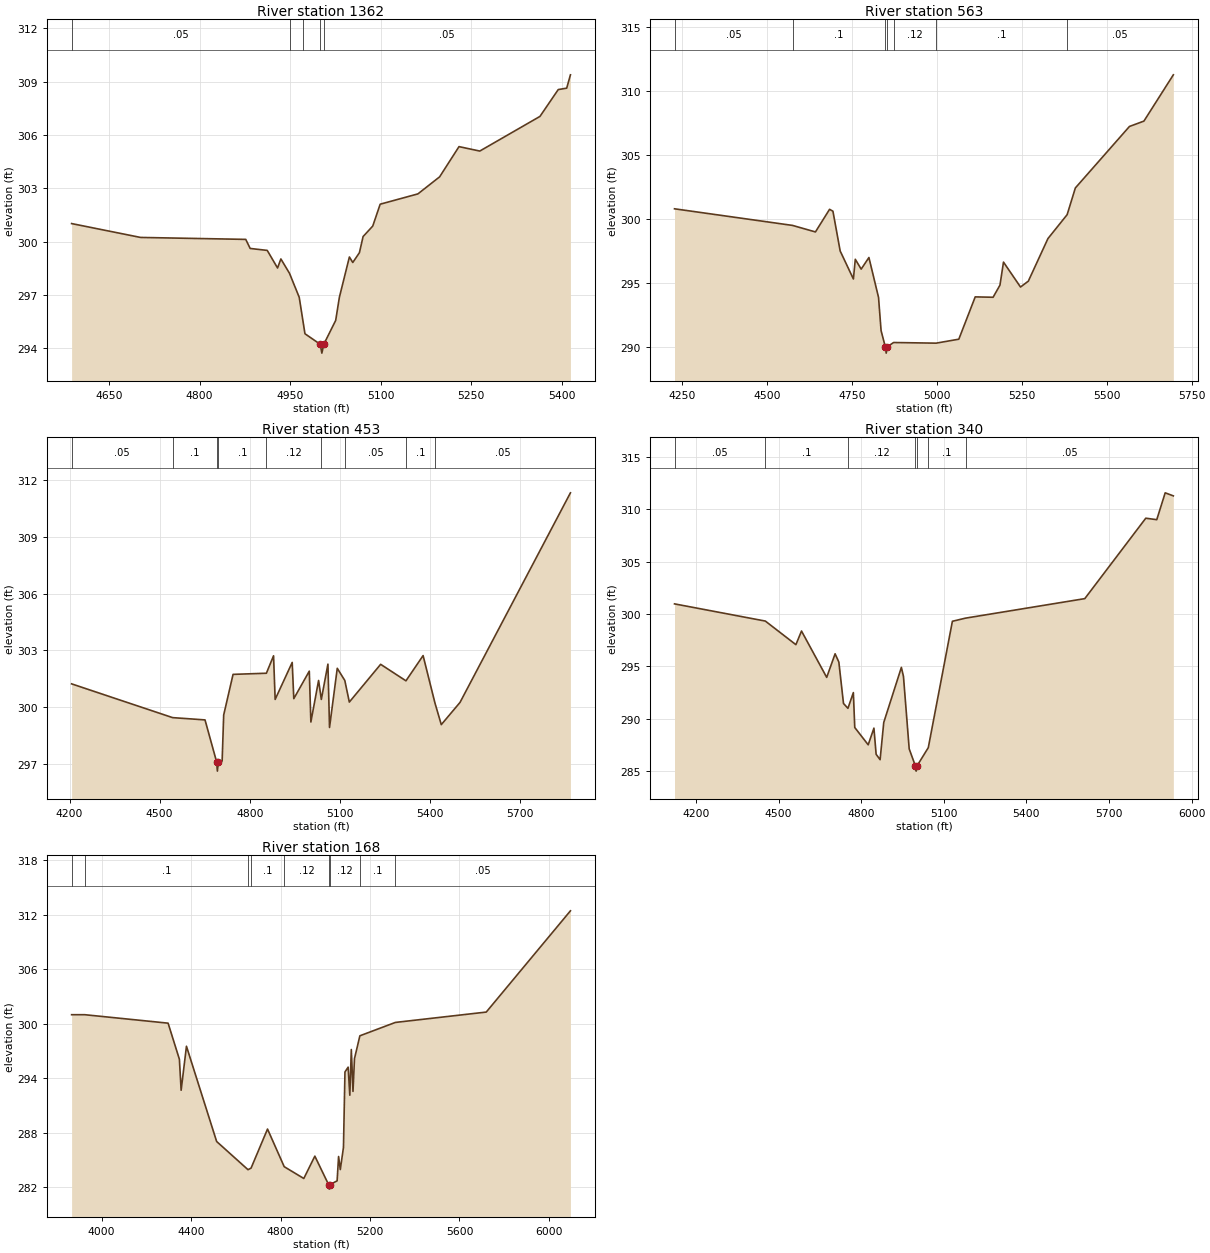
Type RM Length L Ch R = 1 ,1362    ,799,799,799
BEGIN DESCRIPTION:
Mapping XS 0be31142
END DESCRIPTION:
XS GIS Cut Line= 2
       2277110.8     13420586.47      2276755.17     13421332.43
#Sta/Elev= 30
  4587.9  301.01  4702.1  300.23  4876.4  300.12  4883.7  299.61    4912   299.5
  4929.1  298.51  4934.6  299.02  4948.9  298.21    4965  296.86  4970.6  295.65
  4974.5  294.81  4999.7  294.22  5002.5  293.72  5005.7  294.22  5025.4  295.56
  5031.5  296.86  5048.1  299.13  5053.7  298.82  5064.7  299.37  5070.8  300.28
  5086.8  300.87  5099.1   302.1  5161.6  302.68  5197.6  303.64  5229.7  305.34
  5264.1  305.09  5363.8  307.04  5394.1  308.55  5408.1  308.63  5414.3  309.38
#Mann= 5 ,-1 , 0
  4587.9     .05       0  4948.9      .1       0  4970.6     .05       0
  4999.7     .03       0  5005.7     .05       0
Bank Sta=4999.7,5005.7
XS Rating Curve= 0 ,0
Exp/Cntr=0.3,0.1

Type RM Length L Ch R = 1 ,563     ,110,110,110
BEGIN DESCRIPTION:
UNT010 IN SUCR 2.0
END DESCRIPTION:
XS GIS Cut Line= 4
      2277006.58     13420621.22      2276520.51     13420482.34
      2276242.73     13420612.55      2276329.42      13421262.7
#Sta/Elev= 30
  4227.9  300.79  4575.3  299.49  4642.7  298.98  4684.3  300.75  4694.2   300.6
  4715.5  297.49  4754.4   295.3    4760  296.84  4777.3  296.07  4800.1  296.98
  4828.4  293.86  4835.9  291.26  4848.3     290    4851   289.5  4854.3     290
  4872.7  290.33  4997.9  290.28  5064.7  290.59    5113   293.9  5165.6  293.87
  5185.8  294.82  5196.2  296.62  5246.3  294.67  5269.3  295.13    5327  298.46
  5383.5  300.33  5407.7  302.42  5566.9  307.23  5609.5  307.65  5696.1  311.27
#Mann= 7 ,-1 , 0
  4227.9     .05       0  4575.3      .1       0  4848.3     .07       0
  4854.3      .1       0  4872.7     .12       0  4997.9      .1       0
  5383.5     .05       0
Bank Sta=4848.3,4854.3
XS Rating Curve= 0 ,0
Exp/Cntr=0.3,0.1

Type RM Length L Ch R = 1 ,453     ,285,285,285
BEGIN DESCRIPTION:
Mapping XS 81ed7c83
END DESCRIPTION:
XS GIS Cut Line= 4
      2277006.59      13420543.1      2276494.47     13420404.22
       2276121.2     13420534.43      2276225.24     13421262.69
#Sta/Elev= 30
  4206.7  301.24  4543.2  299.46  4651.1  299.34  4689.5  297.14  4692.3  296.64
  4695.5  297.14  4708.1  297.17  4713.3   299.6  4744.5  301.74  4855.5   301.8
  4879.4  302.72  4884.7  300.42  4941.5  302.37  4946.8  300.46  4998.4  301.91
  5003.7  299.23  5029.4  301.42  5038.5  300.42  5060.5  302.28  5065.8  298.94
  5091.6  302.06  5116.7  301.42  5131.8  300.28  5236.1  302.27  5320.4   301.4
  5377.5  302.73  5417.2  300.22  5438.1  299.09  5500.4  300.26  5868.3  311.31
#Mann= 9 ,-1 , 0
  4206.7     .05       0  4543.2      .1       0  4689.5     .07       0
  4695.5      .1       0  4855.5     .12       0  5038.5      .1       0
  5116.7     .05       0  5320.4      .1       0  5417.2     .05       0
Bank Sta=4689.5,4695.5
XS Rating Curve= 0 ,0
Exp/Cntr=0.3,0.1

Type RM Length L Ch R = 1 ,340     ,172,172,172
BEGIN DESCRIPTION:
Mapping XS 81ed7c83
END DESCRIPTION:
XS GIS Cut Line= 4
      2277021.18     13420400.82      2276340.66     13420274.09
      2276086.75     13420477.22      2276179.19     13421266.24
#Sta/Elev= 30
  4122.1  300.97    4452  299.33    4563  297.08  4583.4  298.38  4674.9  293.96
  4705.4  296.21    4719  295.42  4735.9  291.47    4752  291.01  4771.7  292.51
  4776.8  289.18  4825.6  287.53  4846.4  289.12  4854.4  286.63  4868.8  286.11
  4882.1  289.66  4946.1  294.91  4953.7  294.05  4974.5  287.14    4997  285.52
  4999.8  285.02    5003  285.52  5043.9  287.26  5131.4  299.31  5179.2  299.61
  5612.3  301.47  5833.8  309.14  5873.7     309  5904.3  311.56  5933.9  311.27
#Mann= 7 ,-1 , 0
  4122.1     .05       0    4452      .1       0    4752     .12       0
    4997     .07       0    5003     .12       0  5043.9      .1       0
  5179.2     .05       0
Bank Sta=4997,5003
XS Rating Curve= 0 ,0
Exp/Cntr=0.3,0.1

Type RM Length L Ch R = 1 ,168     ,0,0,0
BEGIN DESCRIPTION:
UNT010 IN SUCR 1.0
END DESCRIPTION:
XS GIS Cut Line= 4
      2277145.47     13420326.08      2276303.49     13420048.32
      2276025.72     13420360.82      2276129.88     13421280.92
#Sta/Elev= 30
  3865.5  300.98  3924.5  300.98    4297  300.05  4347.5  296.08  4355.3  292.67
  4379.1  297.51  4514.1  287.03  4654.3  283.93    4668   284.1  4741.6   288.4
  4816.2  284.26  4903.9  282.96  4953.2  285.42  5014.6  282.29  5017.4  281.79
  5020.6  282.29  5052.8   282.7  5059.4  285.38    5067  283.94  5081.2  286.38
  5087.9  294.68  5102.1  295.21  5109.6  292.12  5116.3  297.15  5123.8  292.54
  5130.5  296.15  5154.6  298.66  5313.2  300.13  5719.7  301.27  6096.2  312.41
#Mann= 9 ,-1 , 0
  3865.5     .05       0  3924.5      .1       0  4654.3     .12       0
    4668      .1       0  4816.2     .12       0  5014.6     .07       0
  5020.6     .12       0  5154.6      .1       0  5313.2     .05       0
Bank Sta=5014.6,5020.6
XS Rating Curve= 0 ,0
Exp/Cntr=0.3,0.1

Chan Stop Cuts=-1
Use User Specified Reach Order=0
Composite Channel Slope=5