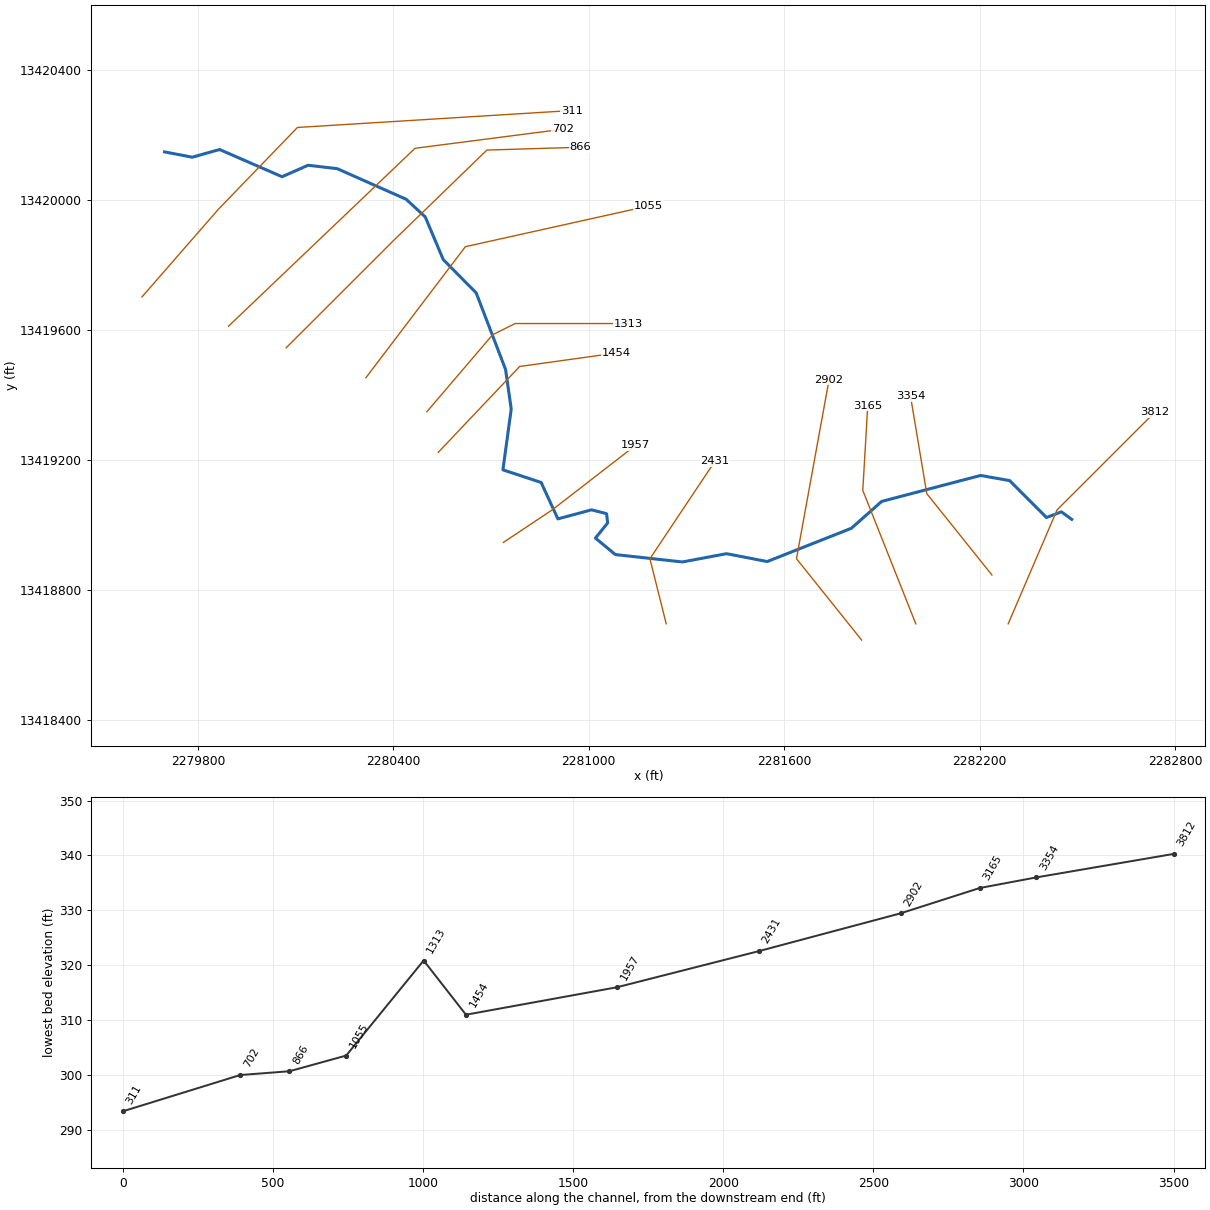
--- UNT011 IN SUCR.prj (project) ---

Proj Title=UNT011 IN SUCR Base Level Engineering
Current Plan=p01
Default Exp/Contr=0.3,0.1
English Units
Geom File=g01
Flow File=f01
Plan File=p01
BEGIN DESCRIPTION:
UNT011 IN SUCR
END DESCRIPTION:

--- UNT011 IN SUCR.p01 (plan) ---

Plan Title=Multiple Run
Short Identifier=Multiple
Geom File=g01
Flow File=f01
Subcritical Flow
K Sum by GR= 0
Std Step Tol= 0.01
Critical Tol= 0.01
Num of Std Step Trials= 20
Max Error Tol= 0.3
Flow Tol Ratio= 0.001
Split Flow NTrial= 30
Split Flow Tol= 0.02
Split Flow Ratio= 0.02
Log Output Level= 0
Friction Slope Method= 1
Unsteady Friction Slope Method= 2
Unsteady Bridges Friction Slope Method= 1
Parabolic Critical Depth
Global Vel Dist=  1 , 1 , 1
Global Log Level= 0
CheckData=True
Encroach Param= -1, 0, 0, 0
BEGIN DESCRIPTION:
Multiple Run
END DESCRIPTION:

--- UNT011 IN SUCR.f01 (steady flow) ---

Flow Title=Multiple
Number of Profiles=7
Profile Names=10-year,25-year,50-year,1pct_min,100-year,1pct_plu,500-year
River Rch & RM= UNT011 IN SUCR,Reach-1,3812
     143     192     232     206     279     378     410
Boundary for River Rch & Prof#=UNT011 IN SUCR,Reach-1,1
Up Type=0
Dn Type=3
Dn Slope=0.005
Boundary for River Rch & Prof#=UNT011 IN SUCR,Reach-1,2
Up Type=0
Dn Type=3
Dn Slope=0.005
Boundary for River Rch & Prof#=UNT011 IN SUCR,Reach-1,3
Up Type=0
Dn Type=3
Dn Slope=0.005
Boundary for River Rch & Prof#=UNT011 IN SUCR,Reach-1,4
Up Type=0
Dn Type=3
Dn Slope=0.005
Boundary for River Rch & Prof#=UNT011 IN SUCR,Reach-1,5
Up Type=0
Dn Type=3
Dn Slope=0.005
Boundary for River Rch & Prof#=UNT011 IN SUCR,Reach-1,6
Up Type=0
Dn Type=3
Dn Slope=0.005
Boundary for River Rch & Prof#=UNT011 IN SUCR,Reach-1,7
Up Type=0
Dn Type=3
Dn Slope=0.005

--- UNT011 IN SUCR.g01 (geometry) ---

Geom Title=Existing Conditions

River Reach=UNT011 IN SUCR,Reach-1
Reach XY= 30
      2282482.85     13419017.70      2282450.95     13419040.90
      2282405.13     13419023.45      2282292.31     13419136.85
      2282202.96     13419152.67      2281899.35     13419072.94
      2281806.18     13418990.33      2281547.86     13418888.16
      2281422.82     13418912.33      2281287.77     13418886.91
      2281081.59     13418909.55      2281020.48     13418960.25
      2281057.98     13419006.78      2281054.50     13419035.25
      2281008.67     13419047.05      2280905.20     13419019.28
      2280853.81     13419131.08      2280736.45     13419169.97
      2280761.93     13419356.77      2280744.57     13419478.30
      2280654.35     13419713.66      2280553.32     13419815.83
      2280497.90     13419947.08      2280439.25     13420001.44
      2280227.81     13420095.31      2280138.13     13420105.76
      2280058.39     13420070.58      2279866.48     13420154.20
      2279782.69     13420130.56      2279697.72     13420146.86

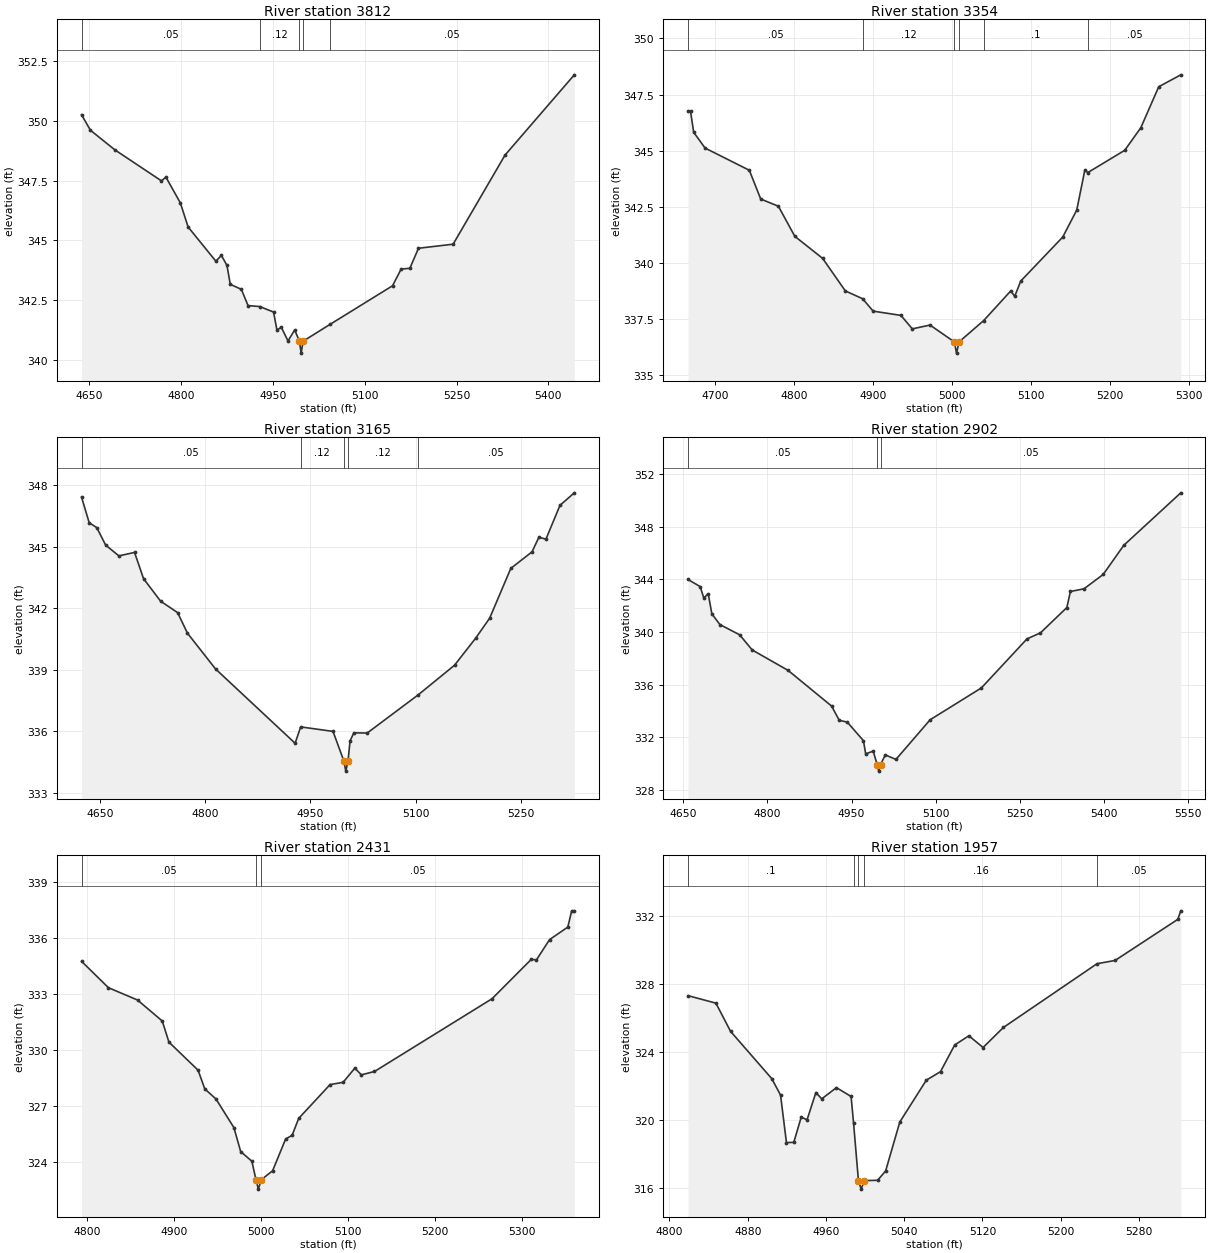
Type RM Length L Ch R = 1,3812,458,458,458
BEGIN DESCRIPTION:
UNT011 IN SUCR 8.0
END DESCRIPTION:
XS GIS Cut Line= 3
      2282287.71     13418696.84      2282437.72     13419046.85
      2282737.74     13419346.88
#Sta/Elev= 30
  4637.3  350.26  4651.8  349.61  4691.7  348.79  4767.9  347.49  4775.1  347.65
  4798.7  346.57  4811.4  345.56  4856.7  344.13  4865.8  344.37  4874.9  343.95
  4880.3  343.16  4898.4  342.95  4909.3  342.27  4928.3  342.23  4951.0  342.00
  4956.5  341.25  4963.7  341.36  4974.6  340.79  4985.5  341.25  4993.3  340.78
  4996.1  340.28  4999.3  340.78  5043.1  341.48  5145.4  343.10  5159.5  343.80
  5173.7  343.83  5187.8  344.67  5244.4  344.84  5329.2  348.57  5442.4  351.93
#Mann=5,-1,0
  4637.3    0.05       0  4928.3    0.12       0  4993.3    0.07       0
  4999.3    0.12       0  5043.1    0.05       0
Bank Sta=4993.3,4999.3
Exp/Cntr=0.3,0.1

Type RM Length L Ch R = 1,3354,189,189,189
BEGIN DESCRIPTION:
UNT011 IN SUCR 7.0
END DESCRIPTION:
XS GIS Cut Line= 3
      2282237.73     13418846.84      2282037.72     13419096.85
      2281987.72     13419396.84
#Sta/Elev= 30
  4665.2  346.75  4668.4  346.75  4672.4  345.82  4686.8  345.12  4742.9  344.13
  4757.3  342.85  4779.7  342.53  4800.5  341.19  4835.7  340.21  4864.5  338.76
  4886.5  338.41  4899.7  337.86  4934.9  337.67  4949.4  337.07  4971.8  337.24
  5002.6  336.49  5005.4  335.99  5008.6  336.49  5039.8  337.44  5074.1  338.76
  5079.1  338.52  5086.8  339.20  5140.0  341.16  5157.7  342.36  5167.9  344.13
  5171.8  344.03  5218.5  345.02  5238.8  346.02  5261.6  347.85  5289.5  348.38
#Mann=6,-1,0
  4665.2    0.05       0  4886.5    0.12       0  5002.6    0.07       0
  5008.6    0.12       0  5039.8     0.1       0  5171.8    0.05       0
Bank Sta=5002.6,5008.6
Exp/Cntr=0.3,0.1

Type RM Length L Ch R = 1,3165,263,263,263
BEGIN DESCRIPTION:
UNT011 IN SUCR 6.0
END DESCRIPTION:
XS GIS Cut Line= 3
      2282004.05     13418696.69      2281841.31     13419106.80
      2281856.50     13419367.23
#Sta/Elev= 30
  4623.8  347.43  4634.7  346.18  4645.5  345.94  4658.1  345.09  4677.0  344.56
  4699.3  344.73  4712.1  343.45  4736.4  342.35  4760.7  341.79  4774.6  340.79
  4814.7  339.04  4928.1  335.41  4936.0  336.21  4982.1  335.99  4997.5  334.55
  5000.3  334.05  5003.5  334.55  5006.4  335.53  5011.8  335.92  5030.8  335.91
  5103.3  337.77  5155.2  339.22  5185.3  340.54  5205.3  341.52  5235.4  343.95
  5265.7  344.76  5275.4  345.47  5285.5  345.38  5305.5  347.03  5325.9  347.64
#Mann=5,-1,0
  4623.8    0.05       0  4936.0    0.12       0  4997.5    0.07       0
  5003.5    0.12       0  5103.3    0.05       0
Bank Sta=4997.5,5003.5
Exp/Cntr=0.3,0.1

Type RM Length L Ch R = 1,2902,471,471,471
BEGIN DESCRIPTION:
UNT011 IN SUCR 6.1
END DESCRIPTION:
XS GIS Cut Line= 3
      2281837.75     13418646.82      2281637.72     13418896.85
      2281737.72     13419446.83
#Sta/Elev= 30
  4658.3  343.99  4680.0  343.45  4686.4  342.59  4694.4  342.90  4700.8  341.38
  4715.2  340.57  4750.4  339.79  4772.8  338.64  4836.8  337.09  4914.5  334.38
  4928.1  333.30  4942.5  333.16  4971.3  331.75  4975.3  330.75  4988.7  330.96
  4995.8  329.94  4998.6  329.44  5001.8  329.94  5010.3  330.67  5029.3  330.33
  5090.3  333.34  5181.8  335.76  5263.1  339.48  5287.2  339.94  5334.2  341.86
  5340.6  343.08  5364.7  343.28  5399.0  344.37  5435.9  346.59  5537.5  350.57
#Mann=3,-1,0
  4658.3    0.05       0  4995.8    0.03       0  5001.8    0.05       0
Bank Sta=4995.8,5001.8
Exp/Cntr=0.3,0.1

Type RM Length L Ch R = 1,2431,474,474,474
BEGIN DESCRIPTION:
UNT011 IN SUCR 5.0
END DESCRIPTION:
XS GIS Cut Line= 3
      2281237.72     13418696.85      2281187.72     13418896.85
      2281387.71     13419196.84
#Sta/Elev= 30
  4793.9  334.74  4824.8  333.33  4858.3  332.67  4886.7  331.55  4894.4  330.42
  4927.9  328.92  4935.6  327.92  4948.5  327.38  4969.1  325.85  4976.9  324.57
  4989.8  324.05  4994.5  323.06  4997.2  322.56  5000.5  323.06  5013.6  323.54
  5028.6  325.24  5036.1  325.44  5043.6  326.34  5079.7  328.15  5094.7  328.27
  5108.2  329.03  5115.7  328.67  5130.8  328.85  5266.0  332.74  5311.0  334.84
  5317.1  334.82  5332.1  335.90  5353.1  336.57  5357.6  337.44  5360.6  337.44
#Mann=3,-1,0
  4793.9    0.05       0  4994.5    0.03       0  5000.5    0.05       0
Bank Sta=4994.5,5000.5
Exp/Cntr=0.3,0.1

Type RM Length L Ch R = 1,1957,503,503,503
BEGIN DESCRIPTION:
UNT011 IN SUCR 4.0
END DESCRIPTION:
XS GIS Cut Line= 3
      2280737.74     13418946.87      2280887.72     13419046.85
      2281143.40     13419244.96
#Sta/Elev= 30
  4819.0  327.33  4847.5  326.89  4862.5  325.23  4904.6  322.45  4913.6  321.48
  4919.6  318.69  4927.1  318.70  4934.7  320.18  4940.7  320.03  4949.7  321.63
  4955.7  321.26  4970.7  321.92  4985.7  321.40  4988.2  319.85  4993.2  316.45
  4996.0  315.95  4999.2  316.45  5012.8  316.47  5021.0  317.02  5035.5  319.90
  5062.6  322.36  5077.1  322.86  5091.6  324.43  5106.1  324.97  5120.6  324.28
  5141.4  325.46  5237.1  329.21  5255.5  329.40  5319.7  331.82  5322.7  332.32
#Mann=5,-1,0
  4819.0     0.1       0  4988.2    0.16       0  4993.2    0.07       0
  4999.2    0.16       0  5237.1    0.05       0
Bank Sta=4993.2,4999.2
Exp/Cntr=0.3,0.1

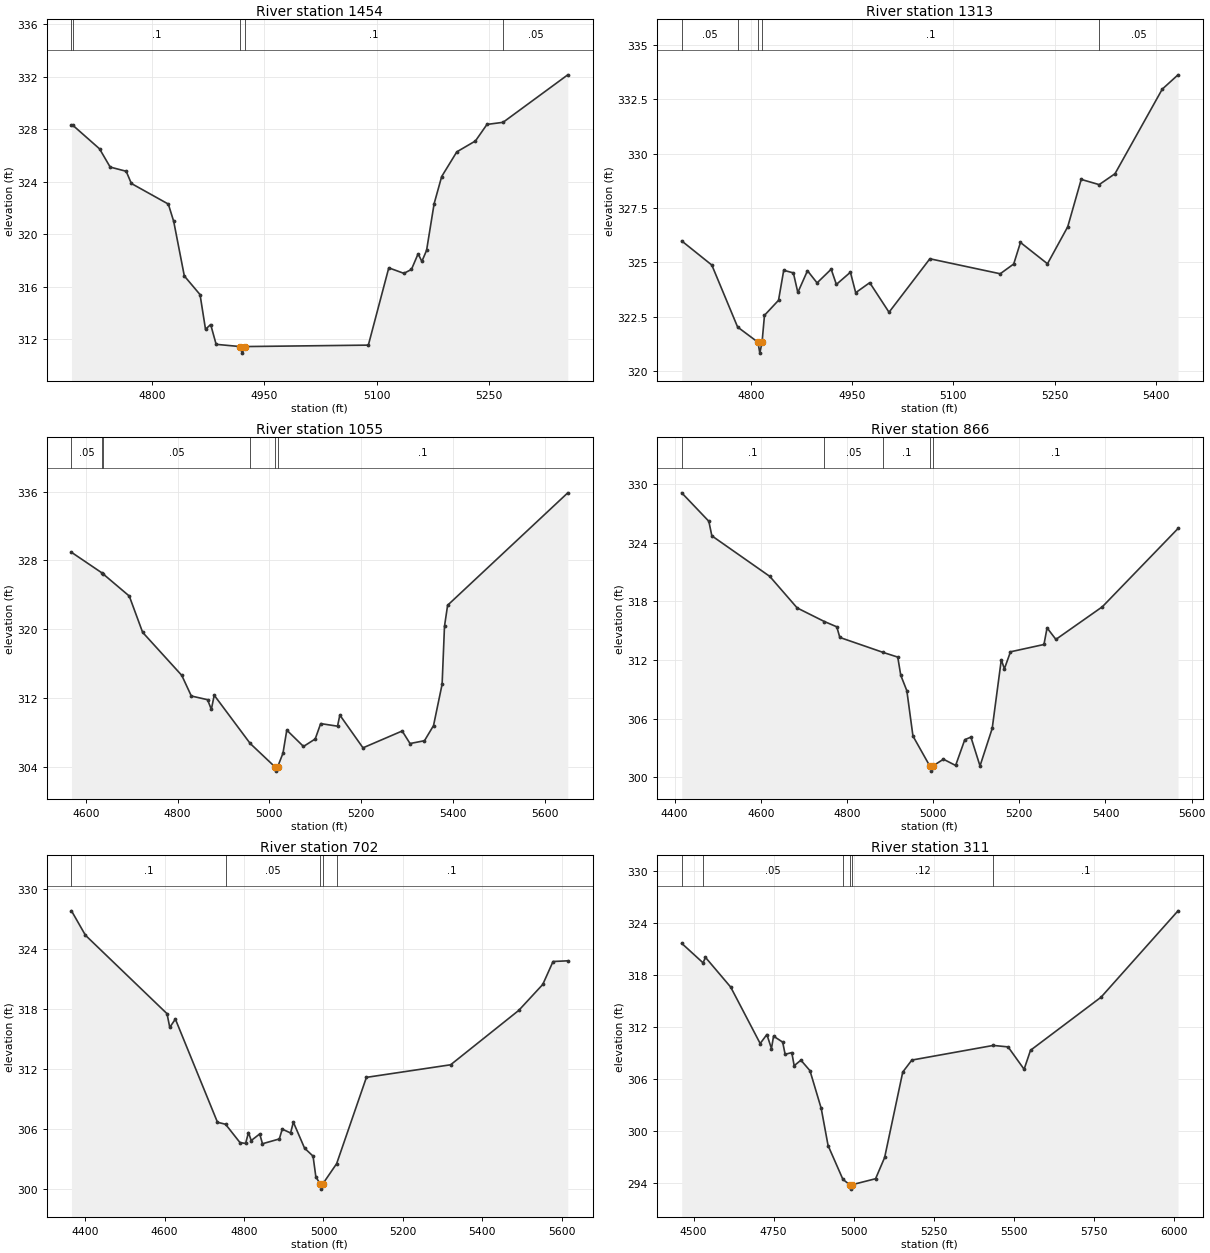
Type RM Length L Ch R = 1,1454,141,141,141
BEGIN DESCRIPTION:
Mapping XS 645b0c4e
END DESCRIPTION:
XS GIS Cut Line= 3
      2280537.84     13419223.63      2280787.87     13419487.55
      2281084.64     13419528.96
#Sta/Elev= 30
  4692.1  328.29  4694.2  328.29  4729.6  326.51  4743.8  325.12  4765.2  324.80
  4772.1  323.87  4821.5  322.30  4828.7  320.98  4842.9  316.82  4863.9  315.40
  4871.2  312.76  4878.1  313.12  4885.4  311.61  4917.6  311.44  4920.3  310.94
  4923.6  311.44  5088.8  311.55  5116.1  317.44  5136.3  317.02  5146.4  317.32
  5155.3  318.51  5160.3  317.93  5166.6  318.77  5176.7  322.33  5186.8  324.40
  5207.0  326.28  5231.9  327.11  5247.3  328.37  5268.8  328.53  5355.3  332.15
#Mann=5,-1,0
  4692.1    0.05       0  4694.2     0.1       0  4917.6    0.07       0
  4923.6     0.1       0  5268.8    0.05       0
Bank Sta=4917.6,4923.6
Exp/Cntr=0.3,0.1

Type RM Length L Ch R = 1,1313,258,258,258
BEGIN DESCRIPTION:
UNT011 IN SUCR 3.0
END DESCRIPTION:
XS GIS Cut Line= 4
      2280503.12     13419348.63      2280704.54     13419584.77
      2280773.98     13419619.50      2281121.17     13419619.50
#Sta/Elev= 30
  4697.5  325.99  4742.1  324.88  4780.3  322.03  4810.5  321.33  4813.2  320.83
  4816.5  321.33  4820.1  322.57  4840.9  323.26  4848.6  324.64  4862.9  324.52
  4869.5  323.62  4883.8  324.62  4898.0  324.06  4918.9  324.69  4926.6  323.99
  4947.4  324.55  4955.2  323.61  4976.0  324.07  5004.6  322.71  5065.1  325.17
  5169.3  324.48  5189.3  324.93  5199.3  325.92  5239.3  324.94  5269.3  326.64
  5289.3  328.82  5315.9  328.58  5339.3  329.08  5409.3  332.97  5432.7  333.63
#Mann=5,-1,0
  4697.5    0.05       0  4780.3     0.1       0  4810.5    0.07       0
  4816.5     0.1       0  5315.9    0.05       0
Bank Sta=4810.5,4816.5
Exp/Cntr=0.3,0.1

Type RM Length L Ch R = 1,1055,189,189,189
BEGIN DESCRIPTION:
UNT011 IN SUCR 2.0
END DESCRIPTION:
XS GIS Cut Line= 3
      2280315.66     13419452.85      2280621.20     13419855.61
      2281183.26     13419980.51
#Sta/Elev= 30
  4569.0  328.95  4636.3  326.52  4638.2  326.42  4694.9  323.86  4724.0  319.64
  4809.3  314.63  4830.1  312.23  4865.5  311.80  4873.7  310.67  4880.0  312.32
  4958.3  306.71  5012.2  303.99  5015.0  303.49  5018.2  303.99  5029.8  305.58
  5038.1  308.26  5074.5  306.36  5100.0  307.23  5111.9  309.02  5148.6  308.72
  5153.7  310.01  5204.1  306.20  5289.5  308.16  5306.6  306.70  5338.1  307.03
  5357.8  308.79  5376.5  313.60  5381.7  320.35  5388.5  322.79  5650.3  335.87
#Mann=6,-1,0
  4569.0    0.05       0  4636.3     0.1       0  4638.2    0.05       0
  4958.3     0.1       0  5012.2    0.07       0  5018.2     0.1       0
Bank Sta=5012.2,5018.2
Exp/Cntr=0.3,0.1

Type RM Length L Ch R = 1,866,164,164,164
BEGIN DESCRIPTION:
Mapping XS 125bed
END DESCRIPTION:
XS GIS Cut Line= 4
      2280070.85     13419544.84      2280400.72     13419874.70
      2280687.17     13420152.48      2280973.22     13420161.15
#Sta/Elev= 30
  4416.7  329.11  4479.6  326.20  4486.6  324.71  4621.0  320.56  4684.6  317.33
  4747.7  315.94  4776.5  315.40  4783.6  314.31  4884.7  312.77  4918.0  312.30
  4925.0  310.44  4939.1  308.86  4953.3  304.22  4992.7  301.13  4995.5  300.63
  4998.7  301.13  5024.0  301.85  5052.3  301.21  5073.6  303.85  5087.8  304.11
  5108.9  301.16  5137.2  305.00  5158.3  312.03  5165.5  311.10  5179.6  312.84
  5257.3  313.59  5264.5  315.29  5285.0  314.11  5392.8  317.45  5568.4  325.46
#Mann=5,-1,0
  4416.7     0.1       0  4747.7    0.05       0  4884.7     0.1       0
  4992.7    0.07       0  4998.7     0.1       0
Bank Sta=4992.7,4998.7
Exp/Cntr=0.3,0.1

Type RM Length L Ch R = 1,702,391,391,391
BEGIN DESCRIPTION:
Mapping XS 125bed3e
END DESCRIPTION:
XS GIS Cut Line= 3
      2279893.72     13419611.09      2280466.61     13420157.94
      2280920.15     13420216.53
#Sta/Elev= 30
  4365.7  327.78  4400.8  325.34  4606.2  317.49  4613.1  316.12  4627.2  316.95
  4733.2  306.63  4753.5  306.43  4789.8  304.60  4804.0  304.51  4811.2  305.60
  4818.2  304.80  4839.5  305.46  4846.5  304.48  4888.9  304.96  4896.2  305.94
  4917.2  305.56  4924.2  306.64  4952.4  304.04  4973.8  303.24  4980.8  301.18
  4991.9  300.44  4994.7  299.94  4997.9  300.44  5033.2  302.49  5108.1  311.12
  5320.1  312.38  5491.6  317.82  5552.1  320.42  5577.9  322.71  5615.0  322.78
#Mann=5,-1,0
  4365.7     0.1       0  4753.5    0.05       0  4991.9   0.035       0
  4997.9    0.05       0  5033.2     0.1       0
Bank Sta=4991.9,4997.9
Exp/Cntr=0.3,0.1

Type RM Length L Ch R = 1,311,0,0,0
BEGIN DESCRIPTION:
UNT011 IN SUCR 1.0
END DESCRIPTION:
XS GIS Cut Line= 4
      2279628.15     13419701.10      2279862.52     13419970.19
      2280105.58     13420221.93      2280947.60     13420274.01
#Sta/Elev= 30
  4462.9  321.68  4529.5  319.43  4537.1  320.06  4615.9  316.63  4708.0  310.12
  4728.9  311.16  4743.2  309.54  4749.8  310.97  4778.3  310.28  4785.9  308.88
  4806.8  309.07  4814.2  307.56  4835.2  308.20  4863.5  306.99  4898.7  302.63
  4920.1  298.35  4966.4  294.45  4987.8  293.82  4990.6  293.32  4993.8  293.82
  5068.5  294.52  5096.8  296.97  5153.4  306.83  5181.8  308.21  5436.2  309.90
  5482.4  309.73  5532.5  307.15  5552.5  309.34  5773.0  315.47  6013.3  325.43
#Mann=6,-1,0
  4462.9     0.1       0  4529.5    0.05       0  4966.4    0.12       0
  4987.8   0.035       0  4993.8    0.12       0  5436.2     0.1       0
Bank Sta=4987.8,4993.8
Exp/Cntr=0.3,0.1

Chan Stop Cuts=-1