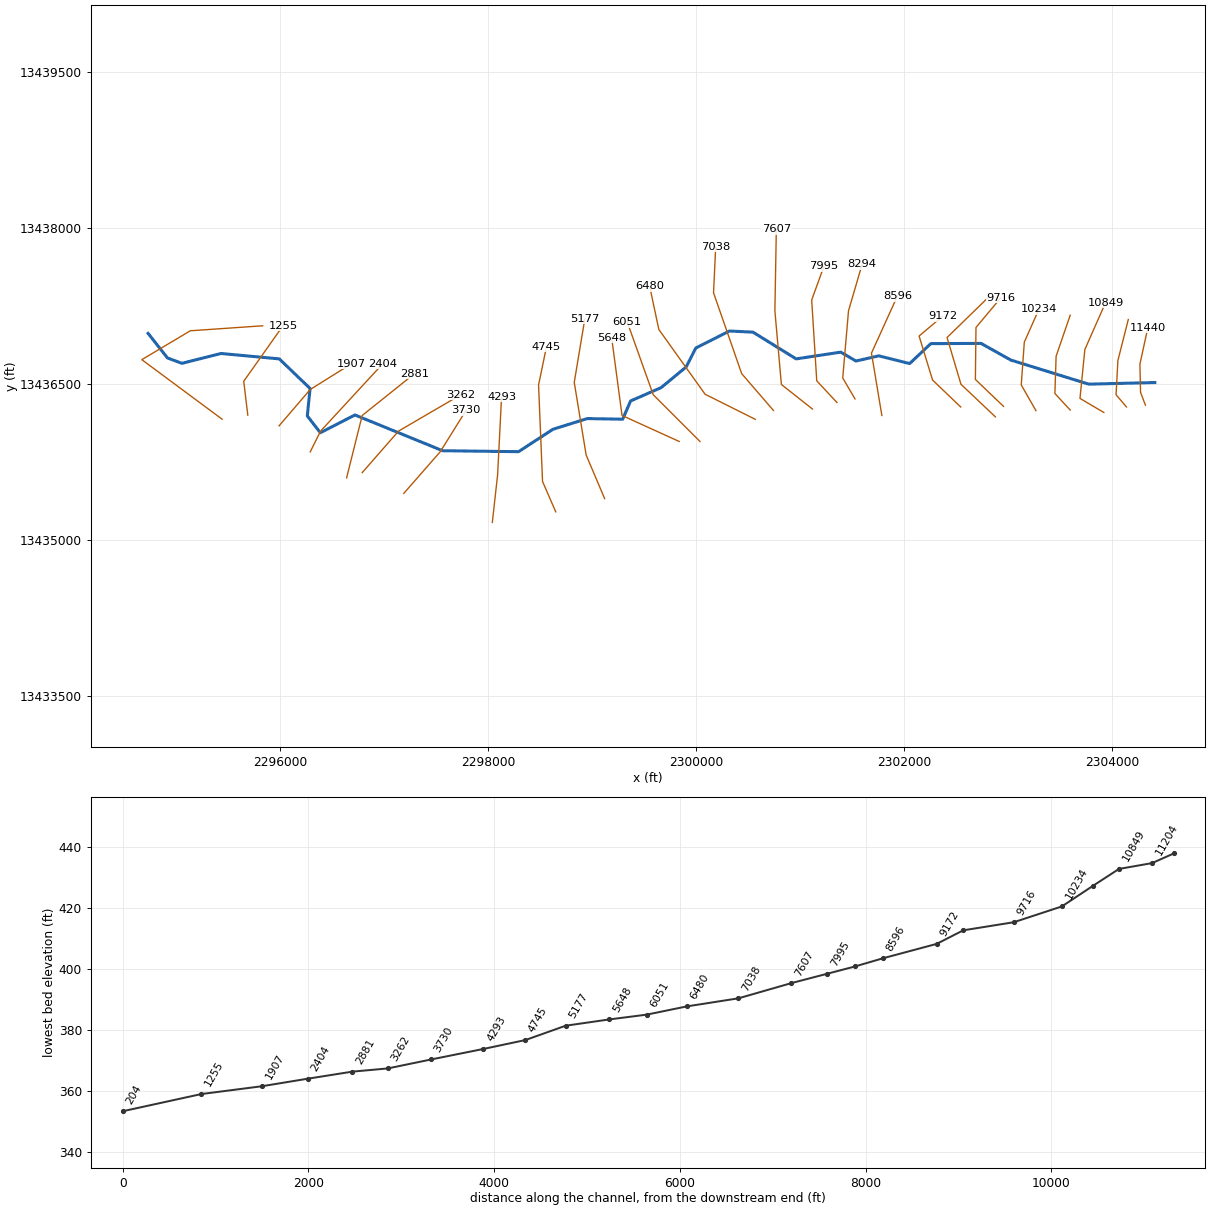
--- UNT012 IN SUCR.prj (project) ---

Proj Title=UNT012 IN SUCR Base Level Engineering
Current Plan=p01
Default Exp/Contr=0.3,0.1
English Units
Geom File=g01
Flow File=f01
Plan File=p01
Y Axis Title=Elevation
X Axis Title(PF)=Main Channel Distance
X Axis Title(XS)=Station
BEGIN DESCRIPTION:
UNT012 IN SUCR
END DESCRIPTION:
DSS Export Rating Curves= 0
DSS Export Rating Curve Sorted= 0
DSS Export Volume Flow Curves= 0
DXF OffsetX= 0
DXF OffsetY= 0
DXF ScaleX= 1
DXF ScaleY= 10

--- UNT012 IN SUCR.p01 (plan) ---

Plan Title=Multiple Run
Short Identifier=Multiple
Geom File=g01
Flow File=f01
Subcritical Flow
K Sum by GR= 0
Std Step Tol= 0.01
Critical Tol= 0.01
Num of Std Step Trials= 20
Max Error Tol= 0.3
Flow Tol Ratio= 0.001
Split Flow NTrial= 30
Split Flow Tol= 0.02
Split Flow Ratio= 0.02
Log Output Level= 0
Friction Slope Method= 1
Unsteady Friction Slope Method= 2
Unsteady Bridges Friction Slope Method= 1
Parabolic Critical Depth
Global Vel Dist=  1 , 1 , 1
Global Log Level= 0
CheckData=True
Encroach Param= -1, 0, 0, 0
BEGIN DESCRIPTION:
Multiple Run
END DESCRIPTION:

--- UNT012 IN SUCR.f01 (steady flow) ---

Flow Title=Multiple
Number of Profiles=7
Profile Names=10-year,25-year,50-year,1pct_min,100-year,1pct_plu,500-year
River Rch & RM= UNT012 IN SUCR,Reach-1,11440
     343     472     579     520     704     951    1041
River Rch & RM= UNT012 IN SUCR,Reach-1,8596
     949    1386    1764    1640    2218    2999    3519
River Rch & RM= UNT012 IN SUCR,Reach-1,4745
    1002    1462    1859    1726    2334    3156    3693
Boundary for River Rch & Prof#=UNT012 IN SUCR,Reach-1,1
Up Type=0
Dn Type=3
Dn Slope=0.005
Boundary for River Rch & Prof#=UNT012 IN SUCR,Reach-1,2
Up Type=0
Dn Type=3
Dn Slope=0.005
Boundary for River Rch & Prof#=UNT012 IN SUCR,Reach-1,3
Up Type=0
Dn Type=3
Dn Slope=0.005
Boundary for River Rch & Prof#=UNT012 IN SUCR,Reach-1,4
Up Type=0
Dn Type=3
Dn Slope=0.005
Boundary for River Rch & Prof#=UNT012 IN SUCR,Reach-1,5
Up Type=0
Dn Type=3
Dn Slope=0.005
Boundary for River Rch & Prof#=UNT012 IN SUCR,Reach-1,6
Up Type=0
Dn Type=3
Dn Slope=0.005
Boundary for River Rch & Prof#=UNT012 IN SUCR,Reach-1,7
Up Type=0
Dn Type=3
Dn Slope=0.005

--- UNT012 IN SUCR.g01 (geometry) ---

Geom Title=Existing Conditions
Program Version=4.10

River Reach=UNT012 IN SUCR  ,Reach-1
Reach XY= 30
      2304413.53     13436513.68      2303778.02     13436498.27
      2303029.11     13436729.94      2302741.53     13436890.48
      2302258.52     13436888.09      2302055.11     13436696.37
      2301757.72     13436770.71      2301538.43     13436720.83
      2301392.54     13436806.28      2300963.02     13436741.36
      2300547.55      13436998.7      2300321.62     13437009.45
      2299997.91     13436846.08      2299904.47     13436663.29
       2299664.3     13436465.25      2299369.62     13436336.08
       2299294.1     13436161.08      2298952.98     13436166.94
       2298623.6     13436064.26      2298291.91     13435848.47
      2297561.41     13435857.82      2296718.07     13436201.84
      2296385.03     13436030.66      2296259.48     13436192.45
      2296286.34     13436456.42      2295990.05     13436741.39
      2295428.78     13436793.26      2295053.58     13436698.62
      2294914.19     13436750.22      2294727.72     13436986.85

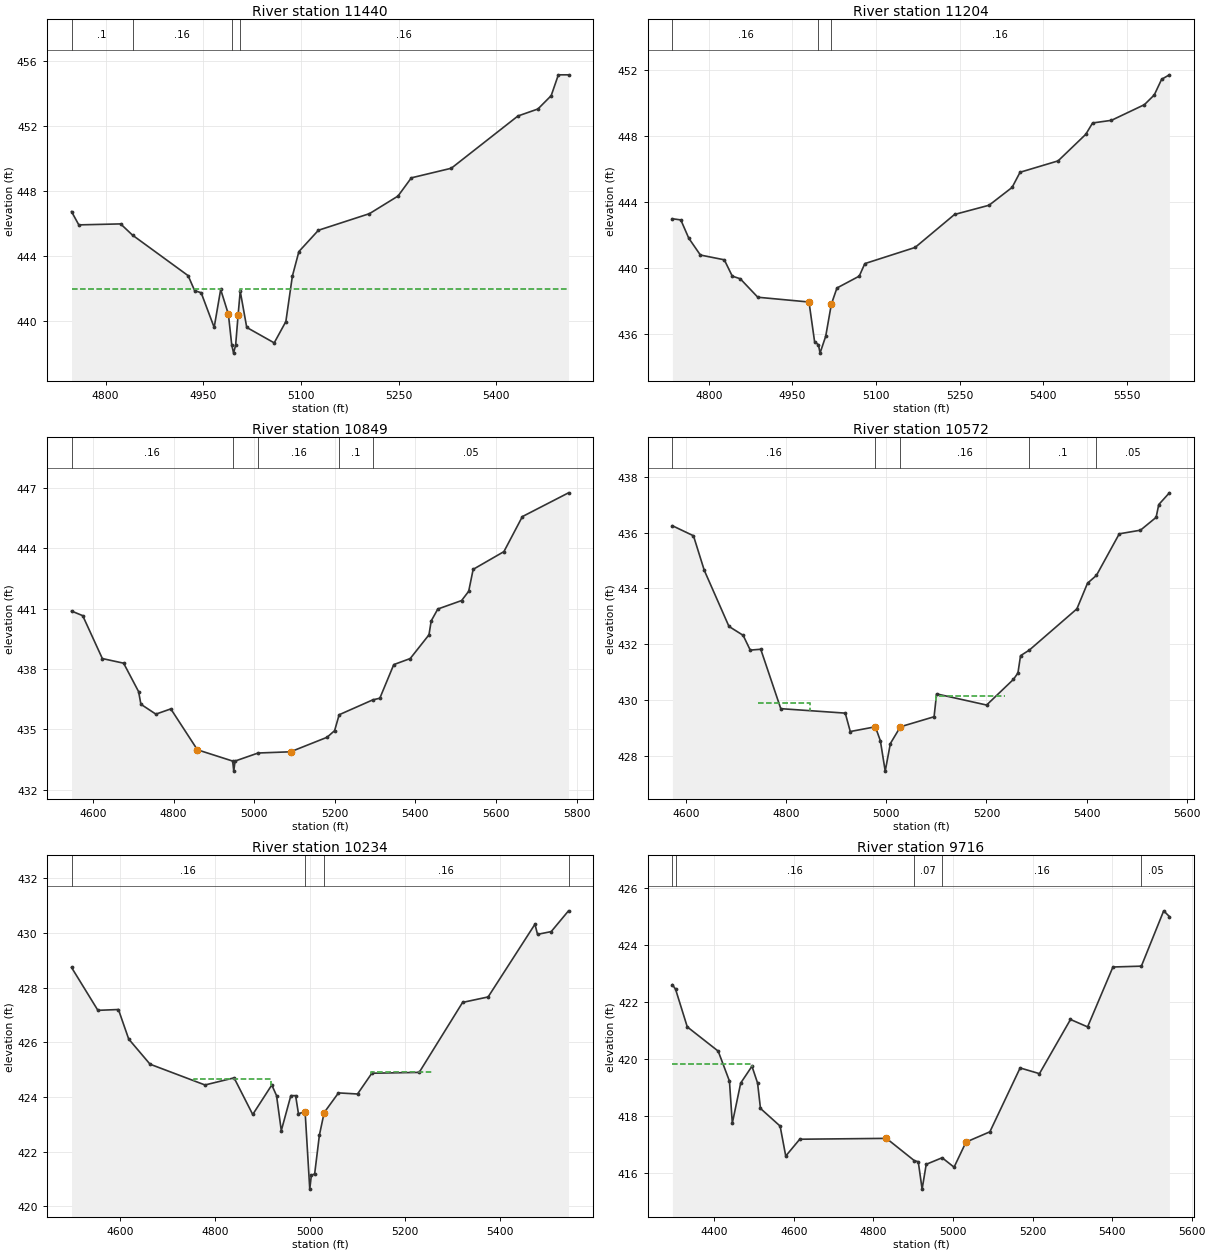
Type RM Length L Ch R = 1 ,11440   ,236,236,236
BEGIN DESCRIPTION:
UNT012 IN SUCR 23.0
END DESCRIPTION:
XS GIS Cut Line= 4
      2304323.62     13436296.41      2304276.55     13436419.97
      2304270.67     13436690.69      2304346.96     13437042.81
#Sta/Elev= 30
  4747.7  446.72  4758.9   445.9  4823.1  445.96  4841.4  445.27  4926.8  442.78
  4936.8  441.86  4946.8  441.73  4966.8   439.6  4976.8  441.93 4988.62  440.41
  4993.8  438.52  4996.6  438.02  4999.8  438.52 5003.62  440.39  5006.8  441.83
  5016.8   439.6    5059  438.65  5076.9  439.96  5086.9  442.75  5096.9  444.26
  5126.9  445.57  5205.3  446.59  5249.1  447.67  5269.6  448.79    5331  449.38
  5433.3  452.59    5464  453.02  5484.4  453.84  5495.4  455.12    5511  455.12
#Mann= 4 ,-1 , 0
  4747.7      .1       0  4841.4     .16       0  4993.8     .07       0
  5006.8     .16       0
#XS Ineff= 2 , 0
         4976.96  441.98 5007.07          441.93
Permanent Ineff=
       T       T
Bank Sta=4988.62,5003.62
XS Rating Curve= 0 ,0
Exp/Cntr=0.3,0.1

Type RM Length L Ch R = 1 ,11204   ,355,355,355
BEGIN DESCRIPTION:
Mapping XS db8d5563
END DESCRIPTION:
XS GIS Cut Line= 4
      2304141.17     13436278.75      2304041.14     13436396.43
       2304058.8       13436726.      2304158.85     13437120.32
#Sta/Elev= 30
  4734.9  442.98    4750  442.91  4764.3   441.8  4785.1  440.78    4828  440.49
  4842.3   439.5  4856.6  439.34  4888.1  438.22  4979.9  437.93  4989.9  435.53
  4996.9  435.33  4999.7  434.83  5009.9  435.86    5020   437.8    5030  438.78
    5070   439.5    5080  440.26  5170.2  441.24  5240.9  443.24  5302.8   443.8
  5344.1  444.88  5358.4   445.8  5426.6  446.49  5476.2   448.1  5488.5  448.79
  5522.3  448.95  5581.4   449.9  5599.1  450.49  5612.3  451.44  5626.2  451.71
#Mann= 3 ,-1 , 0
  4734.9     .16       0  4996.9     .07       0    5020     .16       0
Bank Sta=4979.9,5020
XS Rating Curve= 0 ,0
Exp/Cntr=0.3,0.1

Type RM Length L Ch R = 1 ,10849   ,277,277,277
BEGIN DESCRIPTION:
UNT012 IN SUCR 22.0
END DESCRIPTION:
XS GIS Cut Line= 4
      2303923.39     13436225.78      2303693.91     13436361.12
      2303740.99     13436831.94      2303940.38     13437283.49
#Sta/Elev= 30
  4546.8  440.88  4574.6  440.65  4623.3  438.52  4676.1  438.29  4713.2  436.88
    4719  436.25  4756.1  435.76  4793.2  436.02  4859.2  433.99  4946.6  433.43
  4949.4  432.93  4952.6  433.43  5009.9  433.83  5090.3  433.89  5180.8  434.61
  5199.6  434.94  5210.9  435.73  5294.5  436.47  5311.8  436.55  5346.4  438.22
  5387.2  438.52  5433.8   439.7  5439.3  440.39  5455.7  440.98  5514.7   441.4
  5532.3  441.86  5543.4  442.95  5619.7  443.83  5665.5  445.57    5780  446.75
#Mann= 5 ,-1 , 0
  4546.8     .16       0  4946.6     .07       0  5009.9     .16       0
  5210.9      .1       0  5294.5     .05       0
Bank Sta=4859.2,5090.3
XS Rating Curve= 0 ,0
Exp/Cntr=0.3,0.1

Type RM Length L Ch R = 1 ,10572   ,338,338,338
BEGIN DESCRIPTION:
UNT012 IN SUCR 21.0
END DESCRIPTION:
XS GIS Cut Line= 4
      2303599.77     13436249.26      2303452.61      13436408.2
      2303464.38      13436767.2      2303599.75     13437161.52
#Sta/Elev= 30
  4572.8  436.25  4614.9  435.89  4636.5  434.65  4685.8  432.64  4714.1  432.32
  4728.3  431.79  4749.3  431.82  4789.3  429.69  4918.1  429.53  4928.1  428.87
  4978.2  429.04  4988.2  428.54  4997.9  427.45  5008.2  428.44  5028.2  429.04
  5095.5   429.4  5100.5  430.22  5200.4  429.82    5254  430.74    5263  430.97
  5268.2  431.59  5285.7  431.79  5380.8  433.27    5402  434.19  5419.8  434.47
  5465.4  435.96  5507.7  436.09    5539  436.55  5544.3  437.01  5565.5  437.43
#Mann= 5 ,-1 , 0
  4572.8     .16       0  4978.2     .07       0  5028.2     .16       0
  5285.7      .1       0  5419.8     .05       0
#XS Ineff= 2 ,-1
 4743.98 4847.64  429.89 5098.95 5237.17  430.15
Permanent Ineff=
       F       T
Bank Sta=4978.2,5028.2
XS Rating Curve= 0 ,0
Exp/Cntr=0.3,0.1

Type RM Length L Ch R = 1 ,10234   ,518,518,518
BEGIN DESCRIPTION:
UNT012 IN SUCR 20.0
END DESCRIPTION:
XS GIS Cut Line= 4
      2303270.15     13436243.45      2303128.92     13436490.59
      2303158.35     13436902.56      2303299.62     13437220.41
#Sta/Elev= 30
    4498  428.74  4553.5  427.17  4596.7   427.2  4618.3  426.12  4663.2   425.2
  4778.8  424.44    4840   424.7  4879.2  423.36  4919.3  424.44  4929.3  424.05
  4939.3  422.77  4959.4  424.05  4969.4  424.05  4975.4  423.39  4989.4  423.46
  4999.2  420.63  5002.5  421.13  5009.5  421.19  5019.5  422.61  5029.5  423.43
  5059.6  424.15  5099.7  424.11  5129.8  424.87  5229.4   424.9  5320.7  427.46
  5374.4  427.66  5472.9  430.32  5478.3  429.95  5507.1  430.05  5543.5  430.81
#Mann= 4 ,-1 , 0
    4498     .16       0  4989.4     .07       0  5029.5     .16       0
  5543.5      .1       0
#XS Ineff= 3 ,-1
 4754.97 4918.32  424.67 4921.47 4960.73  424.04  5128.8 5257.59  424.93
Permanent Ineff=
       T       T       T
Bank Sta=4989.4,5029.5
XS Rating Curve= 0 ,0
Exp/Cntr=0.3,0.1

Type RM Length L Ch R = 1 ,9716    ,544,544,544
BEGIN DESCRIPTION:
UNT012 IN SUCR 19.0
END DESCRIPTION:
XS GIS Cut Line= 4
      2302958.26      13436284.6      2302687.53     13436543.56
      2302693.41     13437043.81      2302933.59     13437330.85
#Sta/Elev= 30
  4294.8  422.61  4302.8  422.45  4332.2  421.13  4409.9  420.28  4438.2  419.23
  4445.4  417.75  4466.5  419.16  4494.8  419.75  4508.9  419.16  4516.2  418.27
  4565.6  417.65  4579.7   416.6  4614.9  417.19  4832.8  417.22  4902.8  416.44
  4912.8   416.4  4922.5  415.44  4932.8  416.31  4972.8  416.54  5002.8  416.21
  5032.8  417.09  5092.8  417.45  5168.8  419.69  5217.4  419.49  5295.4  421.39
  5338.4  421.13  5402.1  423.23  5473.6  423.26  5529.7   425.2    5544     425
#Mann= 5 ,-1 , 0
  4294.8     .05       0  4302.8     .16       0  4902.8     .07       0
  4972.8     .16       0  5473.6     .05       0
#XS Ineff= 2 , 0
         4495.03  419.83
Permanent Ineff=
       F       F
Bank Sta=4832.8,5032.8
XS Rating Curve= 0 ,0
Exp/Cntr=0.3,0.1

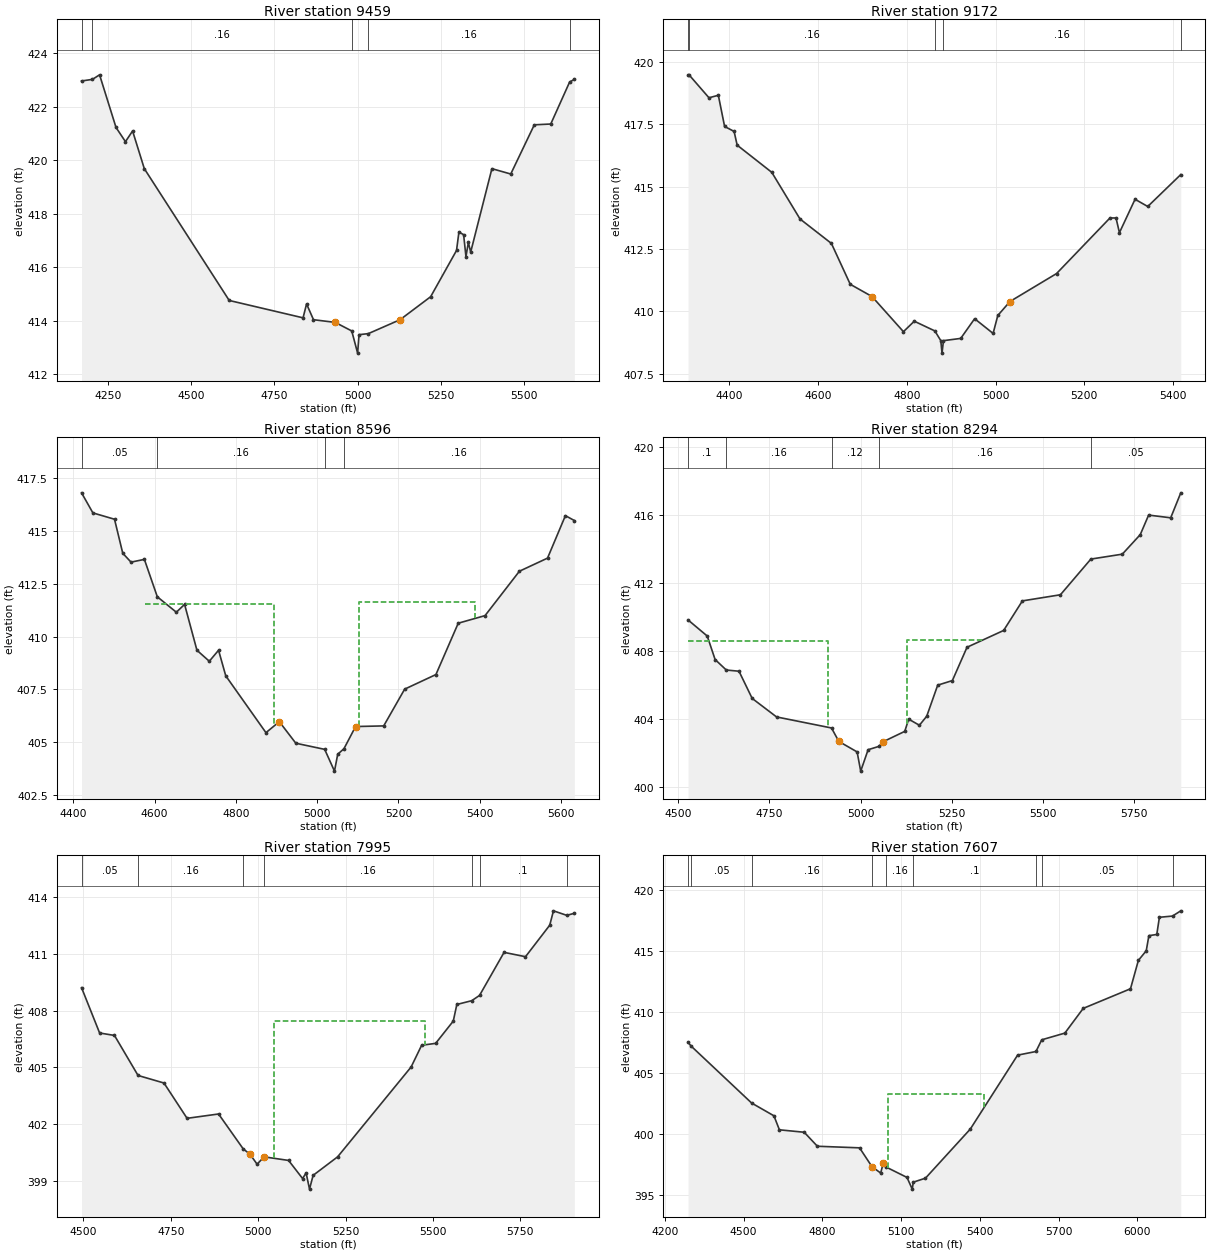
Type RM Length L Ch R = 1 ,9459    ,287,287,287
BEGIN DESCRIPTION:
UNT012 IN SUCR 19.0
END DESCRIPTION:
XS GIS Cut Line= 4
      2302880.33     13436183.05      2302548.71     13436497.31
      2302415.03     13436946.96      2302811.45       13437333.
#Sta/Elev= 30
    4171  422.97  4203.7  423.03  4225.1   423.2  4274.5  421.23  4302.8   420.7
  4324.2   421.1  4359.4  419.69  4614.3  414.76    4836  414.11  4846.5  414.63
  4867.3  414.04  4932.4  413.94  4982.1  413.62  4999.8  412.79    5004  413.48
    5032  413.52  5127.2  414.04    5219   414.9  5296.7  416.63  5303.9  417.32
    5318  417.22    5325   416.4  5332.2  416.93  5339.2  416.57  5402.9  419.69
  5459.5  419.49  5530.2  421.33  5579.6  421.36  5636.2  422.93  5650.3  423.03
#Mann= 5 ,-1 , 0
    4171     .05       0  4203.7     .16       0  4982.1     .07       0
    5032     .16       0  5636.2      .1       0
Bank Sta=4932.4,5127.2
XS Rating Curve= 0 ,0
Exp/Cntr=0.3,0.1

Type RM Length L Ch R = 1 ,9172    ,576,576,576
BEGIN DESCRIPTION:
UNT012 IN SUCR 18.0
END DESCRIPTION:
XS GIS Cut Line= 4
      2302546.29     13436278.71      2302275.56     13436537.68
      2302146.08     13436961.42      2302369.72     13437149.74
#Sta/Elev= 30
  4307.1  419.49  4309.4  419.49  4354.3  418.57  4375.4  418.67  4389.5  417.42
  4410.9  417.22  4417.8  416.67  4495.8  415.58  4559.4  413.71  4630.1  412.73
  4672.6  411.09  4721.6   410.6  4792.4  409.19  4816.8  409.61  4863.2  409.22
  4876.6  408.83  4879.3  408.33  4882.6  408.83  4921.4  408.92  4952.8  409.71
  4994.4  409.12    5005  409.84  5032.4   410.4  5137.3  411.52  5257.7  413.75
  5271.3  413.75    5279  413.16  5314.2   414.5  5342.8  414.21  5417.2  415.49
#Mann= 5 ,-1 , 0
  4307.1      .1       0  4309.4     .16       0  4863.2     .07       0
  4882.6     .16       0  5417.2     .05       0
Bank Sta=4721.6,5032.4
XS Rating Curve= 0 ,0
Exp/Cntr=0.3,0.1

Type RM Length L Ch R = 1 ,8596    ,302,302,302
BEGIN DESCRIPTION:
UNT012 IN SUCR 17.0
END DESCRIPTION:
XS GIS Cut Line= 3
      2301787.72     13436196.84      2301687.72     13436796.85
       2301937.7     13437346.82
#Sta/Elev= 30
  4420.2   416.8  4448.1  415.85  4501.3  415.55  4521.6  413.94  4541.9  413.52
  4574.8  413.65  4606.6  411.88  4653.4  411.15  4673.7  411.52  4704.1  409.35
  4734.5  408.83  4757.3  409.35    4775  408.14  4873.9  405.45  4906.8  405.97
  4947.4  404.95  5018.4  404.66  5042.5  403.63  5050.5  404.43  5065.8  404.69
  5094.4  405.74  5163.6  405.77  5215.2  407.51  5292.1   408.2    5347  410.63
    5413  410.99  5497.5  413.09  5566.7  413.71  5610.7  415.72  5632.6  415.49
#Mann= 4 ,-1 , 0
  4420.2     .05       0  4606.6     .16       0  5018.4     .12       0
  5065.8     .16       0
#XS Ineff= 2 ,-1
 4576.27  4893.3 411.552 5103.17  5388.5411.6489
Permanent Ineff=
       T       T
Bank Sta=4906.8,5094.4
XS Rating Curve= 0 ,0
Exp/Cntr=0.3,0.1

Type RM Length L Ch R = 1 ,8294    ,299,299,299
BEGIN DESCRIPTION:
UNT012 IN SUCR 16.0
END DESCRIPTION:
XS GIS Cut Line= 4
      2301529.32     13436356.33      2301411.27     13436557.71
      2301466.83     13437203.54      2301598.32     13437653.38
#Sta/Elev= 30
  4527.2  409.84  4579.9  408.89  4601.4  407.51  4632.1  406.89  4666.9  406.82
    4703  405.22  4769.8  404.13  4920.4  403.48  4940.4  402.69  4990.6  402.07
  5000.4  400.94  5020.7   402.2  5050.8   402.4  5060.9  402.66  5121.1  403.28
  5131.9     404  5161.2  403.64  5181.3  404.17  5211.4     406  5251.6  406.27
  5291.7  408.23  5392.1  409.22  5443.5  410.96  5547.7  411.32  5631.1  413.42
  5717.3  413.71  5766.5  414.86  5789.4  416.01  5849.9  415.85  5877.5  417.32
#Mann= 5 ,-1 , 0
  4527.2      .1       0  4632.1     .16       0  4920.4     .12       0
  5050.8     .16       0  5631.1     .05       0
#XS Ineff= 2 ,-1
 4457.97 4910.15408.6188  5127.8 5332.52408.6433
Permanent Ineff=
       T       T
Bank Sta=4940.4,5060.9
XS Rating Curve= 0 ,0
Exp/Cntr=0.3,0.1

Type RM Length L Ch R = 1 ,7995    ,388,388,388
BEGIN DESCRIPTION:
UNT012 IN SUCR 15.0
END DESCRIPTION:
XS GIS Cut Line= 4
      2301355.73     13436321.58      2301161.27     13436529.93
      2301112.66     13437307.71      2301230.31     13437632.99
#Sta/Elev= 30
  4494.5  409.22  4546.2  406.82  4588.7  406.69  4656.2  404.57  4730.4  404.17
  4796.5   402.3  4886.6  402.53  4956.8  400.69  4976.8  400.39  4996.9  399.87
  5016.9  400.26    5087  400.07  5127.1  399.11  5137.1  399.41  5146.9  398.55
  5157.2  399.28  5227.3  400.26  5437.7  405.02  5467.8  406.17  5507.8  406.27
  5558.3  407.45  5568.5  408.33  5611.1  408.53  5633.5  408.81  5703.7  411.09
    5765  410.86  5834.4  412.53    5845  413.29  5883.2  413.05  5904.7  413.16
#Mann= 7 ,-1 , 0
  4494.5     .05       0  4656.2     .16       0  4956.8     .12       0
  5016.9     .16       0  5611.1     .05       0  5633.5      .1       0
  5883.2     .05       0
#XS Ineff= 1 ,-1
 5044.78 5476.04407.4497
Permanent Ineff=
       T
Bank Sta=4976.8,5016.9
XS Rating Curve= 0 ,0
Exp/Cntr=0.3,0.1

Type RM Length L Ch R = 1 ,7607    ,569,569,569
BEGIN DESCRIPTION:
UNT012 IN SUCR 14.0
END DESCRIPTION:
XS GIS Cut Line= 4
      2301119.57     13436259.12      2300820.99     13436495.21
      2300758.49     13437203.54      2300772.38     13437988.29
#Sta/Elev= 30
  4288.4  407.51  4300.9  407.19  4530.6  402.53  4615.6  401.48  4636.4  400.33
  4730.9  400.13  4781.1  398.98  4941.7  398.85  4988.8  397.31  5022.1  396.78
  5032.1  397.61  5042.1  397.28  5122.4  396.42  5142.3  395.46  5146.3  396.03
  5192.7  396.36  5363.4  400.39  5543.5  406.46  5613.5  406.76  5635.4  407.72
  5723.5  408.27  5793.5   410.3  5973.5  411.91  6003.5  414.24  6033.5  415.03
  6043.5  416.27  6073.6  416.37  6083.6  417.78  6133.5  417.88    6165  418.31
#Mann= 9 ,-1 , 0
  4288.4      .1       0  4300.9     .05       0  4530.6     .16       0
  4988.8     .12       0  5042.1     .16       0  5146.3      .1       0
  5613.5      .1       0  5635.4     .05       0  6133.5      .1       0
#XS Ineff= 1 ,-1
  5049.5 5415.17403.2366
Permanent Ineff=
       T
Bank Sta=4988.8,5032.1
XS Rating Curve= 0 ,0
Exp/Cntr=0.3,0.1

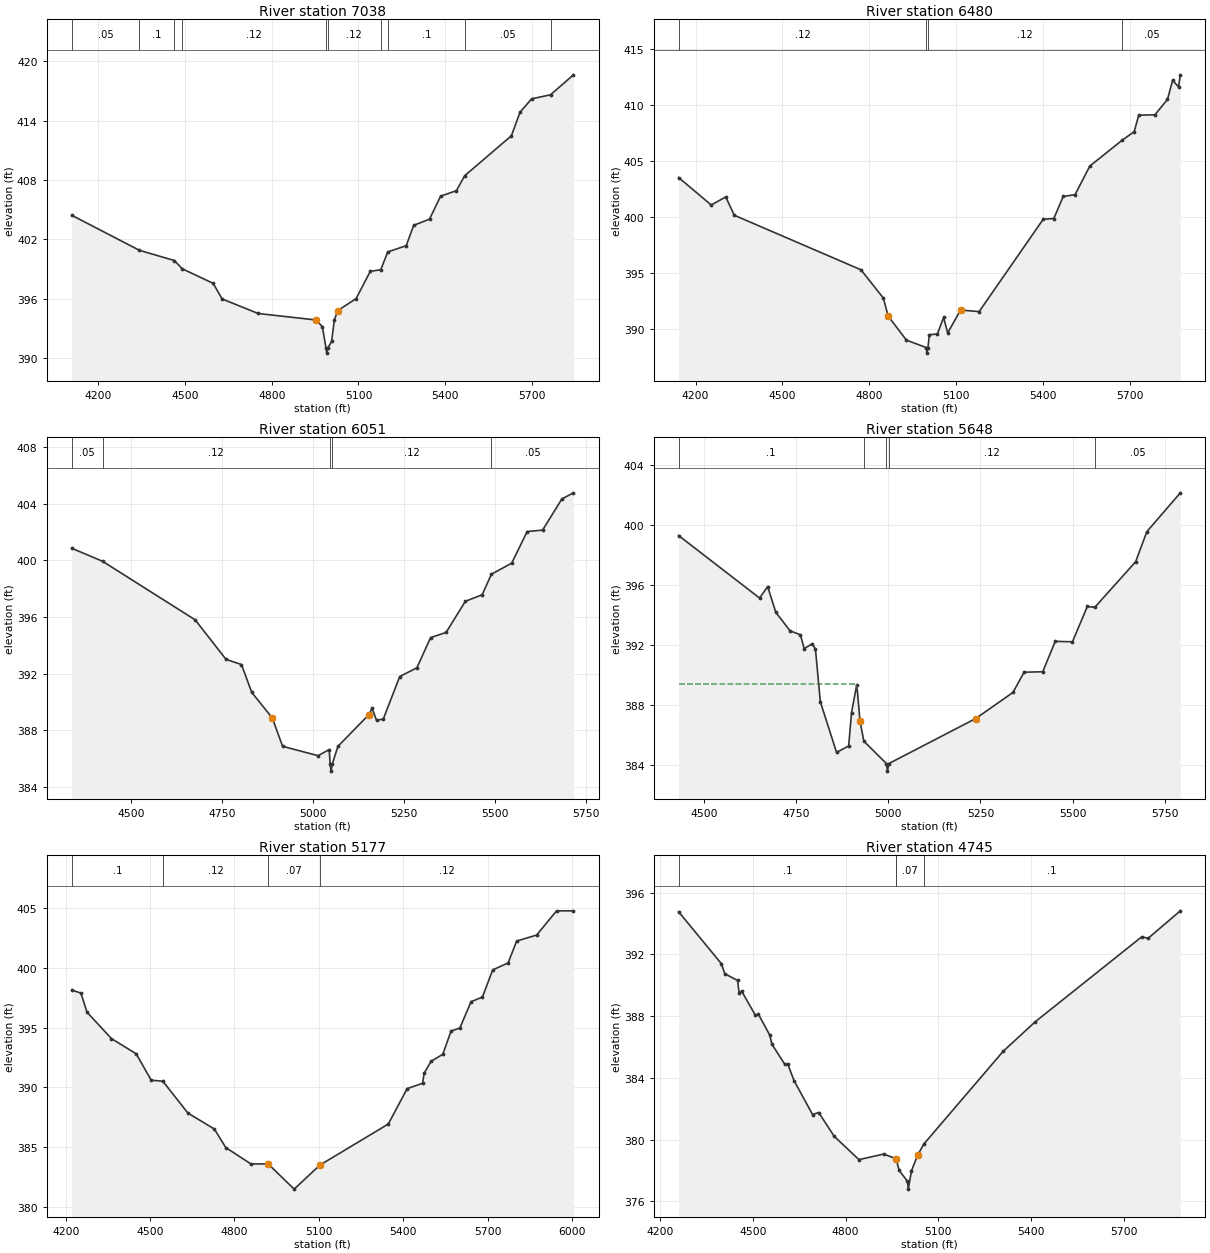
Type RM Length L Ch R = 1 ,7038    ,558,558,558
BEGIN DESCRIPTION:
UNT012 IN SUCR 13.0
END DESCRIPTION:
XS GIS Cut Line= 4
      2300744.62     13436245.18      2300439.05     13436599.37
      2300168.21     13437377.15      2300189.05     13437821.59
#Sta/Elev= 30
  4107.9  404.43  4342.3  400.88    4463  399.85    4490  399.02  4597.2  397.54
  4628.3  395.96    4753  394.49  4954.2  393.83  4975.4  393.14  4987.8  390.98
  4990.5  390.48  4993.8  390.98  5007.2  391.67  5016.6  393.83  5028.3  394.78
  5091.9     396  5140.9  398.75  5177.3  398.92  5201.4  400.72  5265.3  401.35
  5291.1  403.41    5346  404.04  5384.3  406.36    5439  406.92    5468  408.44
  5629.2  412.47  5659.3  414.86  5699.3  416.21  5764.7  416.62  5844.2  418.64
#Mann= 10 ,-1 , 0
  4107.9     .05       0  4342.3      .1       0    4463     .05       0
    4490     .12       0  4987.8     .07       0  4993.8     .12       0
  5177.3     .05       0  5201.4      .1       0    5468     .05       0
  5764.7      .1       0
Bank Sta=4954.2,5028.3
XS Rating Curve= 0 ,0
Exp/Cntr=0.3,0.1

Type RM Length L Ch R = 1 ,6480    ,429,429,429
BEGIN DESCRIPTION:
UNT012 IN SUCR 12.0
END DESCRIPTION:
XS GIS Cut Line= 4
      2300570.01     13436159.74      2300086.82     13436401.33
      2299641.79     13437024.37      2299553.01     13437442.88
#Sta/Elev= 30
  4141.5  403.54  4254.2  401.08  4304.5   401.8  4334.1  400.16  4771.6  395.28
    4849  392.75  4865.6  391.13  4928.9  388.98  4997.2  388.32  4999.9  387.82
  5003.2  388.32    5008  389.47  5035.8  389.53  5057.2  391.01  5071.4  389.63
  5115.7  391.67  5180.1  391.54  5401.3   399.8  5438.1  399.87  5470.4  401.84
  5511.3     402  5562.4  404.56  5674.8  406.89  5715.7  407.64  5731.5  409.12
  5787.3  409.15  5830.8  410.53  5848.6  412.24    5869  411.65  5875.2  412.73
#Mann= 4 ,-1 , 0
  4141.5     .12       0  4997.2     .07       0  5003.2     .12       0
  5674.8     .05       0
Bank Sta=4865.6,5115.7
XS Rating Curve= 0 ,0
Exp/Cntr=0.3,0.1

Type RM Length L Ch R = 1 ,6051    ,403,403,403
BEGIN DESCRIPTION:
UNT012 IN SUCR 11.0
END DESCRIPTION:
XS GIS Cut Line= 3
      2300037.72     13435946.86      2299587.72     13436396.85
      2299337.72     13437096.86
#Sta/Elev= 30
  4337.2  400.85    4422  399.93  4676.6   395.8  4761.5  393.01  4803.9  392.65
  4832.2  390.68  4888.7  388.88    4917  386.88  5014.5  386.22  5045.3  386.65
  5047.6  385.63  5050.3  385.13  5053.6  385.63  5069.2  386.88  5154.1  389.11
  5163.1  389.57  5175.3  388.71  5193.9  388.81  5239.1   391.8  5286.3  392.42
    5324  394.55  5366.5  394.91  5419.6  397.11  5465.8  397.57  5491.2  399.02
    5547   399.8  5589.5  402.03  5631.9  402.13    5685  404.33  5716.9  404.76
#Mann= 5 ,-1 , 0
  4337.2     .05       0    4422     .12       0  5047.6     .07       0
  5053.6     .12       0  5491.2     .05       0
Bank Sta=4888.7,5154.1
XS Rating Curve= 0 ,0
Exp/Cntr=0.3,0.1

Type RM Length L Ch R = 1 ,5648    ,471,471,471
BEGIN DESCRIPTION:
UNT012 IN SUCR 10.0
END DESCRIPTION:
XS GIS Cut Line= 3
      2299837.68     13435946.87      2299287.72     13436196.85
      2299187.73     13436946.81
#Sta/Elev= 30
  4431.3  399.28  4650.9  395.11  4672.9  395.87  4694.9  394.16  4733.3  392.93
  4761.9  392.65  4771.8  391.73  4793.7  392.06  4802.5   391.7  4815.7  388.19
  4859.7  384.81  4892.6  385.24  4900.3  387.47  4914.6  389.34  4923.4  386.88
  4933.7  385.56  4995.1  384.06  4997.8  383.56  5001.1  384.06  5237.2  387.07
  5338.1  388.81  5368.3  390.16  5418.8  390.19  5452.8  392.22  5499.5  392.19
  5539.8  394.55    5560  394.49    5671  397.54  5701.2  399.54    5792  402.13
#Mann= 5 ,-1 , 0
  4431.3      .1       0  4933.7     .12       0  4995.1     .07       0
  5001.1     .12       0    5560     .05       0
#XS Ineff= 2 , 0
       0 4916.12  389.39               0
Permanent Ineff=
       T       T
Bank Sta=4923.4,5237.2
XS Rating Curve= 0 ,0
Exp/Cntr=0.3,0.1

Type RM Length L Ch R = 1 ,5177    ,432,432,432
BEGIN DESCRIPTION:
UNT012 IN SUCR 9.0
END DESCRIPTION:
XS GIS Cut Line= 4
      2299120.47     13435396.84      2298942.46     13435816.44
      2298828.02     13436515.77      2298929.75     13437126.13
#Sta/Elev= 30
  4221.6  398.16  4254.2   397.9  4275.9   396.3  4362.8  394.09  4450.7  392.82
    4504  390.61  4545.4  390.52  4634.4  387.86  4728.5  386.52    4769  384.97
  4858.3   383.6  4919.7   383.6    5012  381.49  5103.4   383.5  5346.6  386.94
  5413.5   389.9  5468.2  390.35  5474.4  391.21  5498.6  392.19  5540.3  392.78
  5569.6  394.72  5601.1  394.98  5640.6  397.18  5681.1  397.57  5717.7  399.84
  5772.4  400.43  5802.8  402.26  5873.7  402.76  5944.7  404.79  6004.8  404.79
#Mann= 4 ,-1 , 0
  4221.6      .1       0  4545.4     .12       0  4919.7     .07       0
  5103.4     .12       0
Bank Sta=4919.7,5103.4
XS Rating Curve= 0 ,0
Exp/Cntr=0.3,0.1

Type RM Length L Ch R = 1 ,4745    ,452,452,452
BEGIN DESCRIPTION:
UNT012 IN SUCR 8.0
END DESCRIPTION:
XS GIS Cut Line= 4
      2298650.01     13435269.68      2298522.86     13435562.14
      2298484.71     13436490.34        2298561.     13436859.04
#Sta/Elev= 30
  4259.1  394.76  4397.6   391.4  4408.7  390.75  4449.9  390.31  4455.4  389.48
  4463.2  389.62  4507.7  388.06  4517.7  388.12  4554.6  386.76  4561.3  386.18
  4602.7  384.89  4612.8  384.88  4632.8  383.83  4692.8  381.63  4712.8  381.76
  4762.9  380.22  4842.9  378.71    4923  379.07    4963  378.77  4973.1  378.02
  5000.1   377.3  5002.8   376.8  5013.1  377.99  5033.1     379  5053.1  379.72
  5310.2  385.73  5413.4  387.63  5758.7  393.14  5779.2  393.04  5883.5  394.82
#Mann= 4 ,-1 , 0
  4259.1      .1       0    4963     .05       0    4963     .07       0
  5053.1      .1       0
Bank Sta=4963,5033.1
XS Rating Curve= 0 ,0
Exp/Cntr=0.3,0.1

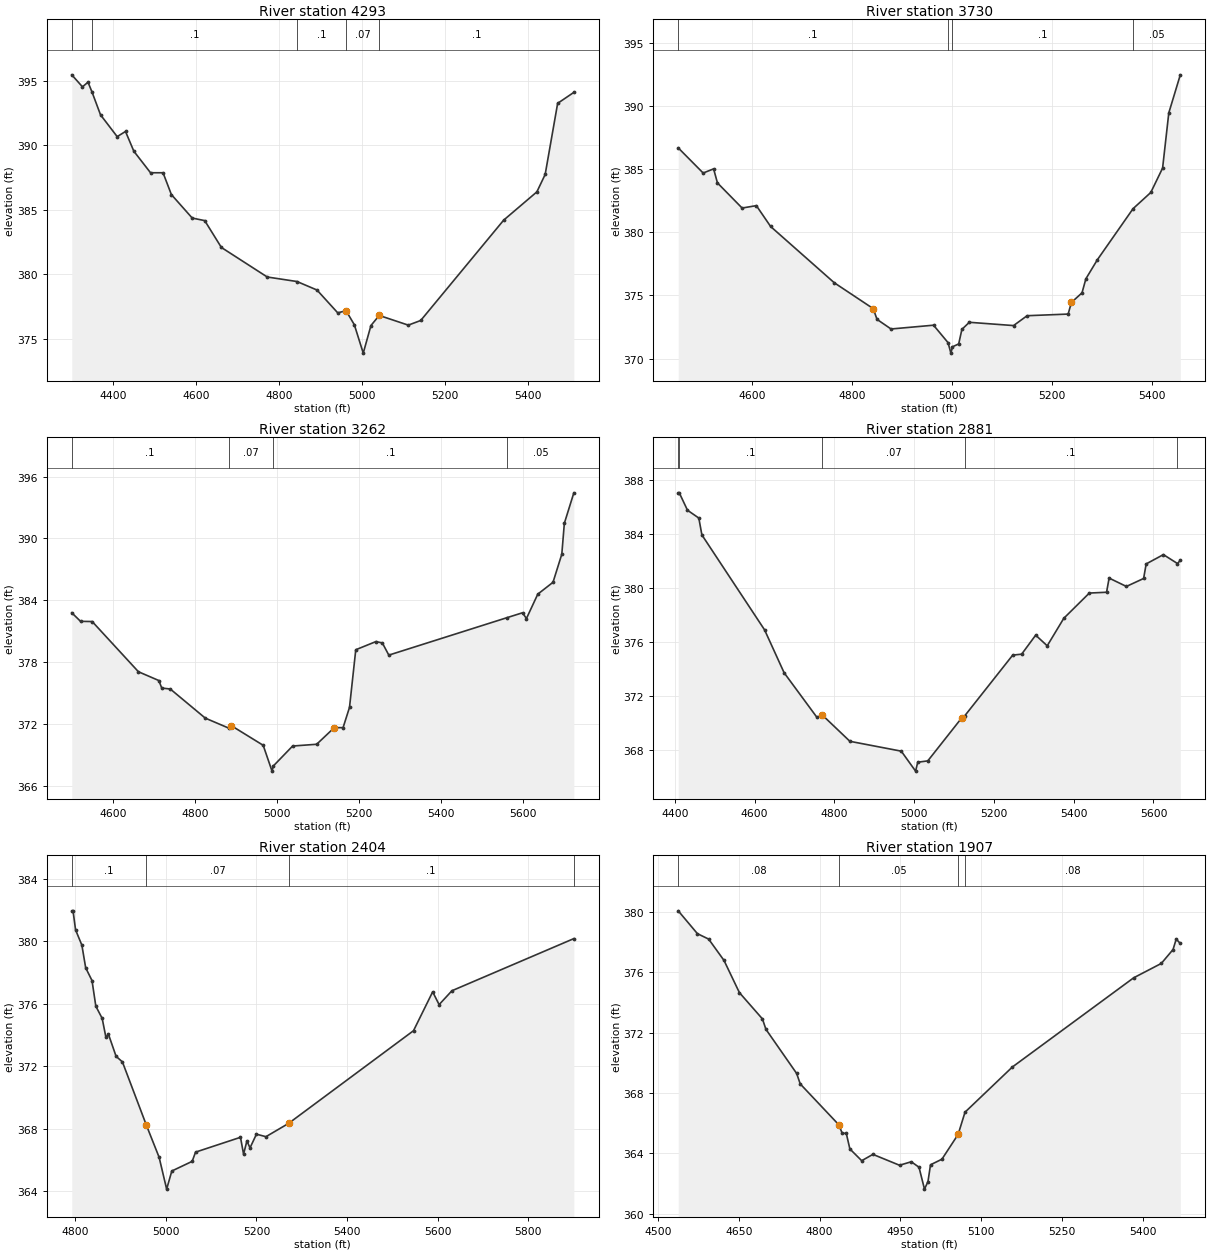
Type RM Length L Ch R = 1 ,4293    ,563,563,563
BEGIN DESCRIPTION:
UNT012 IN SUCR 7.0
END DESCRIPTION:
XS GIS Cut Line= 3
      2298039.68     13435167.92      2298090.55     13435625.71
      2298128.69     13436375.94
#Sta/Elev= 30
  4299.5  395.45  4325.3  394.52  4338.7  394.88  4348.7  394.09  4368.9  392.35
  4409.1  390.66  4429.2  391.06  4449.3  389.53  4489.6  387.86  4519.8  387.86
  4539.9  386.17  4590.2  384.35  4620.4  384.15  4660.6  382.07  4771.3  379.78
  4843.1  379.43  4891.4  378.77  4941.5     377  4961.5  377.17  4981.5  376.08
    5003  373.88  5021.6  376.02  5041.6   376.8  5111.7  376.05  5141.7  376.41
    5342  384.19  5422.1  386.38  5442.1  387.73  5472.2  393.24  5511.3  394.09
#Mann= 5 ,-1 , 0
  4299.5     .05       0  4348.7      .1       0  4843.1      .1       0
  4961.5     .07       0  5041.6      .1       0
Bank Sta=4961.5,5041.6
XS Rating Curve= 0 ,0
Exp/Cntr=0.3,0.1

Type RM Length L Ch R = 1 ,3730    ,468,468,468
BEGIN DESCRIPTION:
UNT012 IN SUCR 6.0
END DESCRIPTION:
XS GIS Cut Line= 3
      2297187.75     13435446.89      2297537.72     13435846.85
      2297787.74     13436246.89
#Sta/Elev= 30
  4452.5  386.67  4502.3  384.68  4523.2  385.01  4530.8   383.9  4580.1  381.91
  4608.6   382.1  4637.1  380.45  4764.2     376  4842.1  373.95  4849.7   373.1
  4877.7  372.34  4962.6  372.64  4991.6  371.26  4997.3  370.43  5000.5  370.93
  5012.9  371.16  5019.3  372.31  5034.1  372.87  5122.5  372.61  5149.6  373.39
  5231.6  373.52  5238.1  374.44  5259.3   375.2    5267  376.31    5290  377.82
  5361.3  381.86  5396.7  383.14  5420.3  385.07  5432.7  389.44  5455.7  392.45
#Mann= 4 ,-1 , 0
  4452.5      .1       0  4991.6     .07       0  5000.5      .1       0
  5361.3     .05       0
Bank Sta=4842.1,5238.1
XS Rating Curve= 0 ,0
Exp/Cntr=0.3,0.1

Type RM Length L Ch R = 1 ,3262    ,381,381,381
BEGIN DESCRIPTION:
UNT012 IN SUCR 5.0
END DESCRIPTION:
XS GIS Cut Line= 3
      2296787.69     13435646.83      2297137.72     13436046.85
      2297737.75     13436396.87
#Sta/Elev= 30
  4498.7  382.81  4520.1  381.98  4548.6  381.96  4661.5   377.1  4711.3  376.25
  4718.5  375.52  4739.3  375.43  4824.8  372.61  4881.7  371.65  4888.4  371.88
  4966.2  369.98  4987.8  367.48    4991  367.98  5038.1  369.91  5096.8  370.08
  5139.8  371.69  5161.3  371.69    5177  373.65  5192.3  379.23  5241.5  380.02
  5257.2  379.89    5273  378.71  5562.8  382.35  5599.6  382.81  5609.1  382.25
  5636.8  384.61    5674  385.76  5695.5  388.48  5701.7  391.47  5724.9  394.42
#Mann= 4 ,-1 , 0
  4498.7      .1       0  4881.7     .07       0    4991      .1       0
  5562.8     .05       0
Bank Sta=4888.4,5139.8
XS Rating Curve= 0 ,0
Exp/Cntr=0.3,0.1

Type RM Length L Ch R = 1 ,2881    ,477,477,477
BEGIN DESCRIPTION:
UNT012 IN SUCR 4.0
END DESCRIPTION:
XS GIS Cut Line= 3
      2296637.71     13435596.82      2296787.72     13436196.85
      2297287.71     13436596.84
#Sta/Elev= 30
  4408.5  387.06  4411.1  387.06  4431.7  385.77  4460.1  385.19  4467.8  383.94
    4625   376.9    4674  373.72  4756.4  370.41  4769.3   370.6  4838.9  368.64
  4967.7  367.91  5003.6  366.43    5009  367.09  5034.2  367.19  5119.1  370.37
  5127.1  370.54  5247.1  375.03  5269.5   375.1  5304.7  376.51  5333.6  375.72
  5375.2  377.76  5439.2  379.63  5482.4  379.69  5488.8  380.74  5532.1  380.12
  5575.3  380.71  5581.7  381.79  5624.9  382.48  5660.1  381.82  5667.3  382.05
#Mann= 5 ,-1 , 0
  4408.5     .05       0  4411.1      .1       0  4769.3     .07       0
  5127.1      .1       0  5660.1     .05       0
Bank Sta=4769.3,5119.1
XS Rating Curve= 0 ,0
Exp/Cntr=0.3,0.1

Type RM Length L Ch R = 1 ,2404    ,497,497,497
BEGIN DESCRIPTION:
UNT012 IN SUCR 3.0
END DESCRIPTION:
XS GIS Cut Line= 3
      2296287.73     13435846.87      2296387.72     13436046.85
      2296987.73     13436696.87
#Sta/Elev= 30
  4792.3  381.96  4795.1  381.96  4800.7  380.74  4814.6  379.76    4823  378.31
    4837  377.49  4845.4  375.85  4859.4  375.07  4867.7  373.85  4873.3  374.05
  4890.1  372.64  4904.1  372.28  4957.2  368.21  4985.1  366.17  5001.7  364.13
  5013.1  365.29  5058.1  365.91  5065.5   366.5  5164.7  367.45  5171.5  366.37
  5178.9  367.22  5185.7  366.77  5199.9  367.65  5220.9  367.49  5270.8  368.34
  5546.6  374.28  5588.9  376.77  5603.1  375.95  5631.4  376.84  5900.5  380.18
#Mann= 4 ,-1 , 0
  4792.3      .1       0  4957.2     .07       0  5270.8      .1       0
  5900.5     .05       0
Bank Sta=4957.2,5270.8
XS Rating Curve= 0 ,0
Exp/Cntr=0.3,0.1

Type RM Length L Ch R = 1 ,1907    ,652,652,652
BEGIN DESCRIPTION:
UNT012 IN SUCR 2.0
END DESCRIPTION:
XS GIS Cut Line= 3
      2295987.75     13436096.89      2296287.72     13436446.85
      2296687.69     13436696.84
#Sta/Elev= 30
  4537.4  380.05    4573  378.54  4593.9  378.18  4622.4  376.77    4651  374.64
  4693.8   372.9  4700.3  372.21  4757.4  369.29    4764   368.6  4835.3  365.91
  4841.9  365.35  4849.6  365.32  4856.2   364.3  4878.2  363.52    4899  363.94
  4948.4  363.22  4970.3  363.45  4984.6  363.09  4994.8  361.64  5001.3  362.14
    5006  363.25  5027.2  363.62  5057.3  365.26  5070.1  366.73  5158.1  369.72
  5383.4  375.62  5434.7  376.57  5456.5  377.49  5462.4  378.18    5470  377.89
#Mann= 4 ,-1 , 0
  4537.4     .08       0  4835.3     .05       0  5057.3      .1       0
  5070.1     .08       0
Bank Sta=4835.3,5057.3
XS Rating Curve= 0 ,0
Exp/Cntr=0.3,0.1

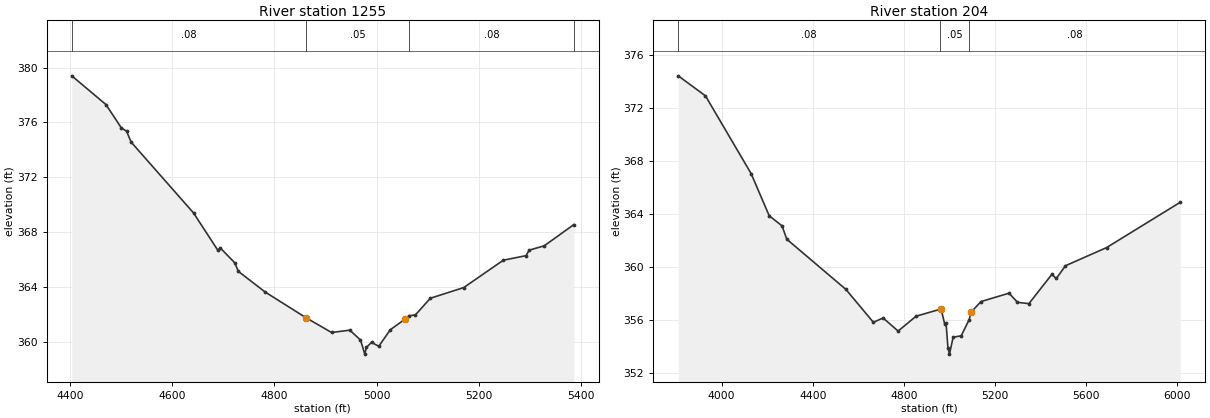
Type RM Length L Ch R = 1 ,1255    ,847,847,847
BEGIN DESCRIPTION:
Mapping XS 6173d685
END DESCRIPTION:
XS GIS Cut Line= 3
      2295686.97     13436200.43      2295647.91     13436525.97
      2296025.53     13437059.85
#Sta/Elev= 30
  4403.8   379.4  4470.7   377.3  4500.9  375.59    4511  375.36  4519.7  374.57
  4641.9  369.39  4689.3  366.67  4694.3  366.83  4722.5  365.75  4729.6  365.12
  4781.8  363.62  4861.3  361.75  4911.8  360.66  4947.5  360.83  4968.4  360.11
  4976.8  359.08    4980  359.58    4990  359.94  5004.1  359.65  5026.7  360.86
  5054.5  361.61  5063.2  361.88  5075.7  361.94    5105  363.16  5170.3  363.94
  5247.8  365.94  5292.1  366.27  5298.2  366.67  5327.8  366.99  5385.6  368.54
#Mann= 4 ,-1 , 0
  4403.8     .08       0  4861.3     .05       0  5063.2     .08       0
  5385.6     .05       0
Bank Sta=4861.3,5054.5
XS Rating Curve= 0 ,0
Exp/Cntr=0.3,0.1

Type RM Length L Ch R = 1 ,204     ,0,0,0
BEGIN DESCRIPTION:
UNT012 IN SUCR 1.0
END DESCRIPTION:
XS GIS Cut Line= 4
      2295439.58     13436161.38      2294667.32       13436734.
       2295133.9     13437011.78      2295830.24     13437059.82
#Sta/Elev= 30
    3810  374.44  3929.4  372.93  4129.8  367.06  4209.1  363.88  4265.4  363.12
  4286.2  362.11  4545.1  358.33  4666.1  355.84  4708.6  356.17  4774.5  355.18
  4853.3   356.3  4957.5  356.82  4963.3  356.82  4978.9  355.71  4984.7  355.81
    4993  353.94  4999.8  353.44  5015.9  354.72  5051.2  354.82  5086.1  356.04
  5095.7  356.63  5138.5  357.41  5261.2  358.04  5298.2  357.35  5348.3  357.25
  5448.5  359.45  5468.6  359.15  5508.7  360.11  5689.1  361.48  6012.4   364.9
#Mann= 3 ,-1 , 0
    3810     .08       0  4957.5     .05       0  5086.1     .08       0
Bank Sta=4963.3,5095.7
XS Rating Curve= 0 ,0
Exp/Cntr=0.3,0.1

Chan Stop Cuts=-1
Use User Specified Reach Order=0
Composite Channel Slope=5