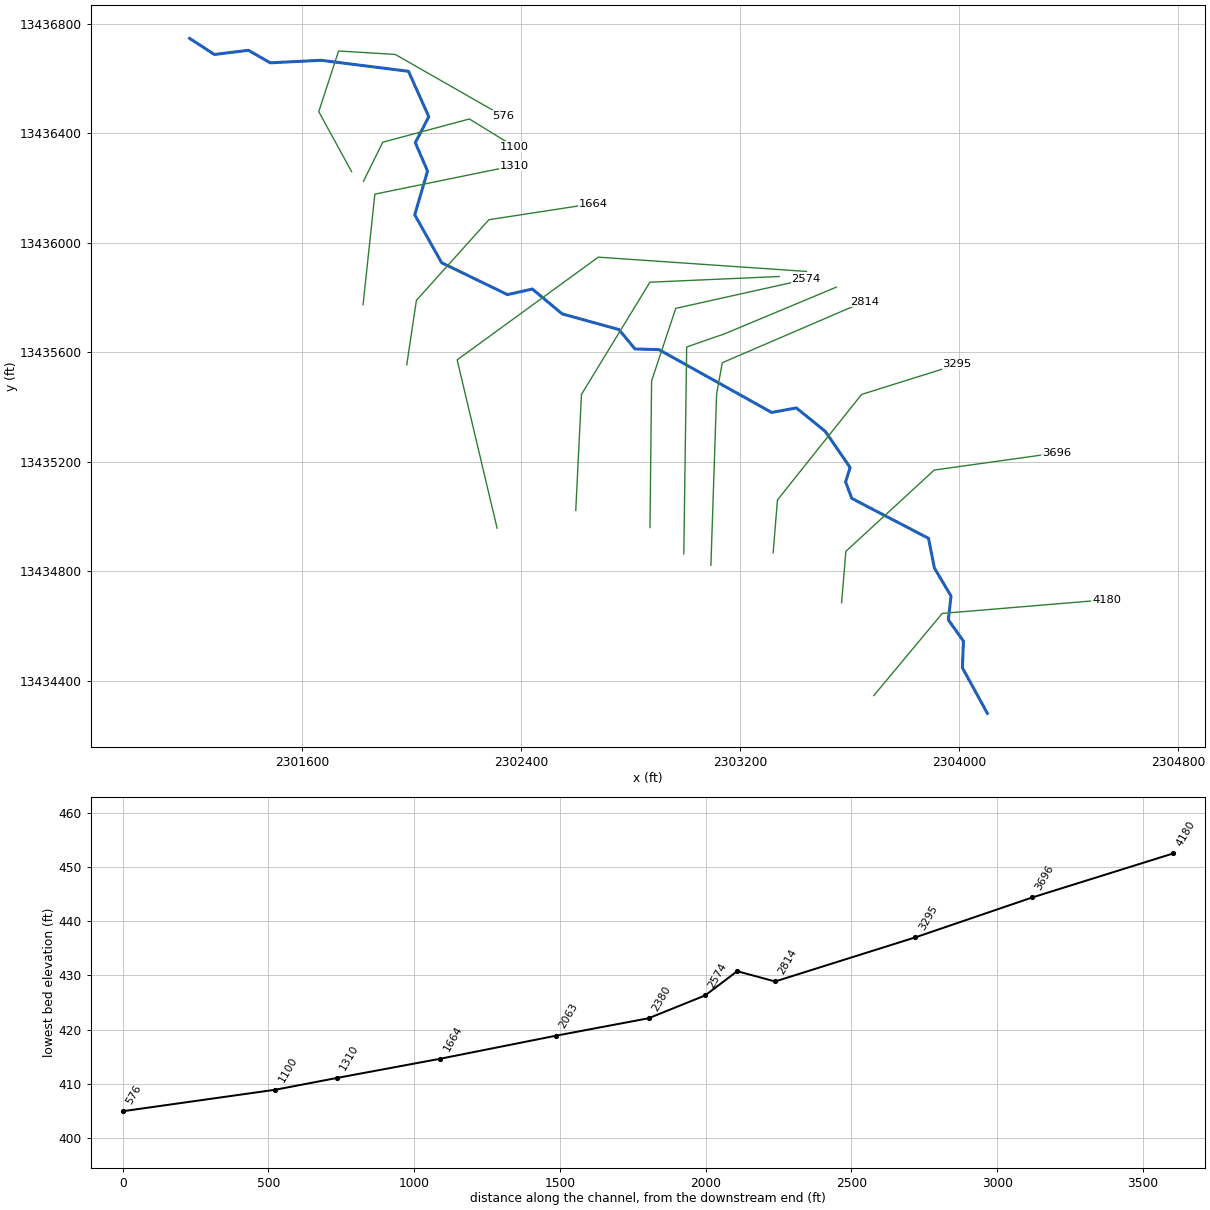
--- UNT013 IN SUCR.prj (project) ---

Proj Title=UNT013 IN SUCR Base Level Engineering
Current Plan=p01
Default Exp/Contr=0.3,0.1
English Units
Geom File=g01
Flow File=f01
Plan File=p01
BEGIN DESCRIPTION:
UNT013 IN SUCR
END DESCRIPTION:

--- UNT013 IN SUCR.p01 (plan) ---

Plan Title=Multiple Run
Short Identifier=Multiple
Geom File=g01
Flow File=f01
Subcritical Flow
K Sum by GR= 0
Std Step Tol= 0.01
Critical Tol= 0.01
Num of Std Step Trials= 20
Max Error Tol= 0.3
Flow Tol Ratio= 0.001
Split Flow NTrial= 30
Split Flow Tol= 0.02
Split Flow Ratio= 0.02
Log Output Level= 0
Friction Slope Method= 1
Unsteady Friction Slope Method= 2
Unsteady Bridges Friction Slope Method= 1
Parabolic Critical Depth
Global Vel Dist=  1 , 1 , 1
Global Log Level= 0
CheckData=True
Encroach Param= -1, 0, 0, 0
BEGIN DESCRIPTION:
Multiple Run
END DESCRIPTION:

--- UNT013 IN SUCR.f01 (steady flow) ---

Flow Title=Multiple
Number of Profiles=7
Profile Names=10-year,25-year,50-year,1pct_min,100-year,1pct_plu,500-year
River Rch & RM= UNT013 IN SUCR,Reach-1,4180
     258     347     419     371     502     679     720
Boundary for River Rch & Prof#=UNT013 IN SUCR,Reach-1,1
Up Type=0
Dn Type=3
Dn Slope=0.005
Boundary for River Rch & Prof#=UNT013 IN SUCR,Reach-1,2
Up Type=0
Dn Type=3
Dn Slope=0.005
Boundary for River Rch & Prof#=UNT013 IN SUCR,Reach-1,3
Up Type=0
Dn Type=3
Dn Slope=0.005
Boundary for River Rch & Prof#=UNT013 IN SUCR,Reach-1,4
Up Type=0
Dn Type=3
Dn Slope=0.005
Boundary for River Rch & Prof#=UNT013 IN SUCR,Reach-1,5
Up Type=0
Dn Type=3
Dn Slope=0.005
Boundary for River Rch & Prof#=UNT013 IN SUCR,Reach-1,6
Up Type=0
Dn Type=3
Dn Slope=0.005
Boundary for River Rch & Prof#=UNT013 IN SUCR,Reach-1,7
Up Type=0
Dn Type=3
Dn Slope=0.005

--- UNT013 IN SUCR.g01 (geometry) ---

Geom Title=Existing Conditions

River Reach=UNT013 IN SUCR,Reach-1
Reach XY= 30
      2304102.72     13434281.86      2304011.42     13434448.23
      2304015.21     13434545.82      2303960.04     13434623.25
      2303969.71     13434710.46      2303909.20     13434812.51
      2303887.66     13434921.07      2303607.36     13435066.84
      2303584.64     13435127.12      2303601.14     13435179.54
      2303510.40     13435311.86      2303404.75     13435397.21
      2303314.55     13435380.75      2302902.67     13435610.09
      2302815.22     13435612.59      2302756.31     13435683.52
      2302549.33     13435740.63      2302440.14     13435831.46
      2302349.27     13435810.98      2302108.65     13435927.50
      2302010.53     13436102.53      2302057.25     13436262.19
      2302012.61     13436365.90      2302061.87     13436460.68
      2301987.71     13436626.46      2301668.46     13436666.64
      2301482.39     13436657.50      2301402.84     13436703.20
      2301278.44     13436687.92      2301187.72     13436746.86

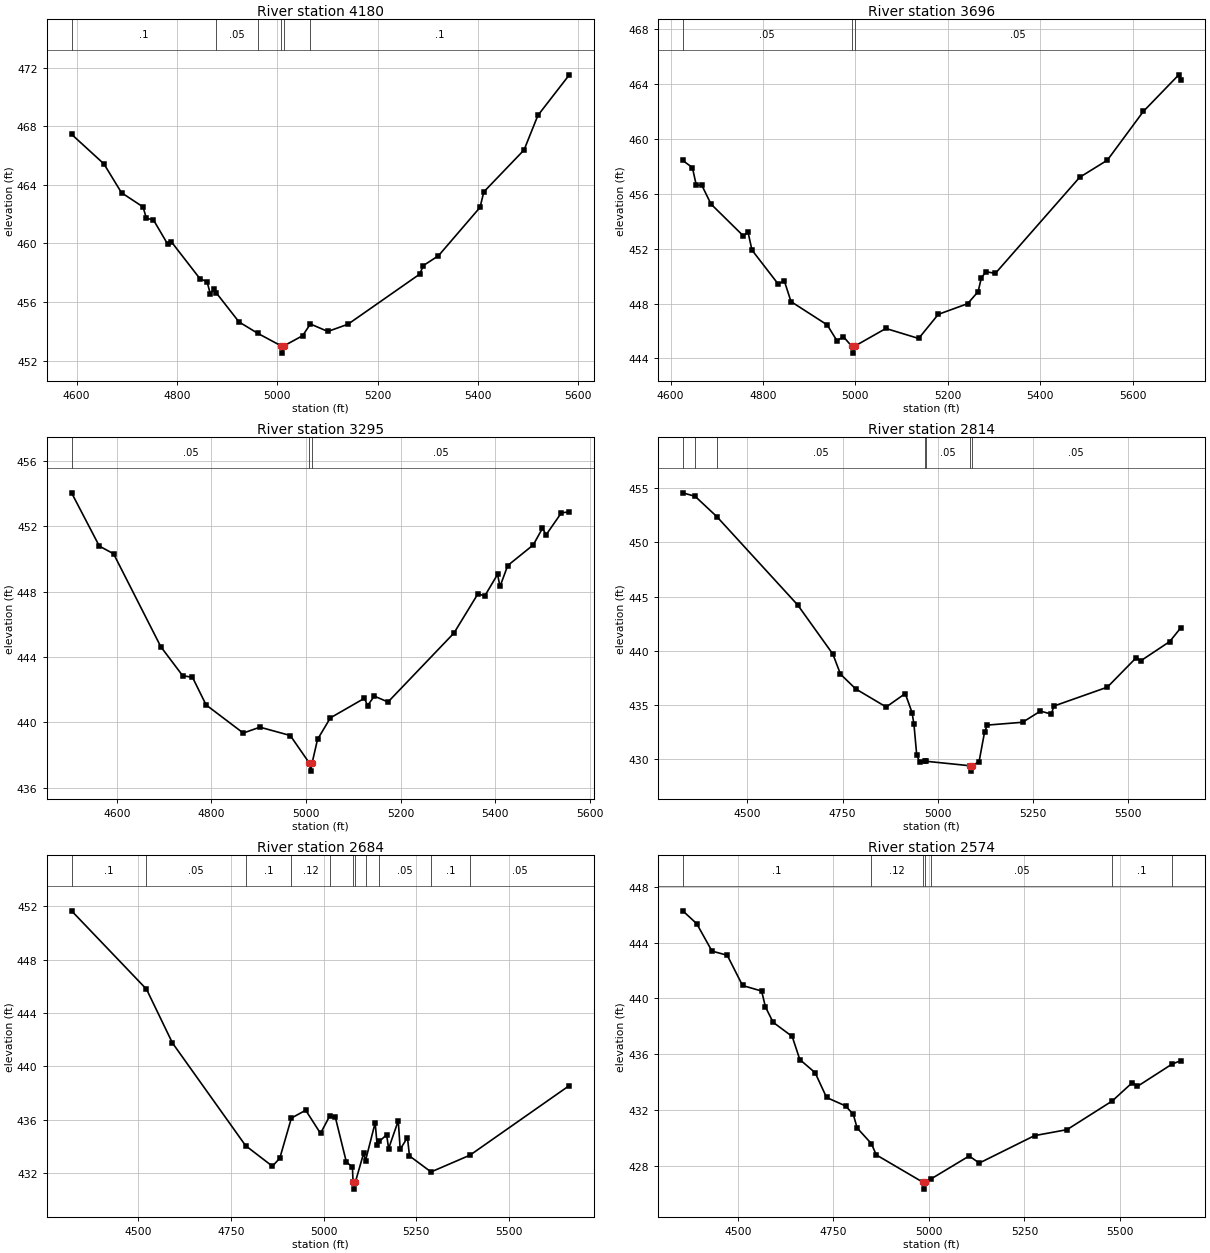
Type RM Length L Ch R = 1,4180,484,484,484
BEGIN DESCRIPTION:
UNT013 IN SUCR 6.0
END DESCRIPTION:
XS GIS Cut Line= 3
      2303687.69     13434346.82      2303937.72     13434646.85
      2304537.68     13434696.85
#Sta/Elev= 30
  4589.8  467.45  4654.3  465.43  4689.4  463.46  4732.4  462.49  4738.9  461.72
  4753.2  461.60  4781.8  459.93  4788.4  460.13  4845.6  457.60  4860.0  457.38
  4866.5  456.56  4874.3  456.90  4878.7  456.61  4923.7  454.64  4961.2  453.86
  5007.5  453.01  5010.2  452.51  5013.5  453.01  5050.6  453.70  5066.0  454.50
  5100.8  453.99  5140.9  454.48  5283.9  457.90  5291.4  458.49  5321.5  459.16
  5404.3  462.46  5411.9  463.52  5492.1  466.38  5519.7  468.74  5582.4  471.51
#Mann=6,-1,0
  4589.8     0.1       0  4878.7    0.05       0  4961.2    0.12       0
  5007.5    0.07       0  5013.5    0.12       0  5066.0     0.1       0
Bank Sta=5007.5,5013.5
Exp/Cntr=0.3,0.1

Type RM Length L Ch R = 1,3696,401,401,401
BEGIN DESCRIPTION:
UNT013 IN SUCR 5.0
END DESCRIPTION:
XS GIS Cut Line= 4
      2303570.00     13434686.00      2303585.63     13434873.52
      2303908.54     13435170.40      2304354.60     13435232.64
#Sta/Elev= 30
  4626.4  458.44  4647.3  457.92  4655.8  456.62  4667.4  456.65  4687.5  455.26
  4757.7  452.93  4767.7  453.20  4776.2  451.90  4832.3  449.45  4846.5  449.62
  4860.7  448.14  4939.0  446.44  4960.0  445.29  4974.1  445.58  4992.1  444.88
  4994.9  444.38  4998.1  444.88  5066.0  446.18  5136.9  445.45  5179.4  447.21
  5243.0  447.99  5265.6  448.87  5272.6  449.88  5282.7  450.32  5302.9  450.20
  5485.3  457.21  5545.2  458.46  5623.2  462.02  5699.8  464.69  5703.6  464.33
#Mann=3,-1,0
  4626.4    0.05       0  4992.1    0.03       0  4998.1    0.05       0
Bank Sta=4992.1,4998.1
Exp/Cntr=0.3,0.1

Type RM Length L Ch R = 1,3295,481,481,481
BEGIN DESCRIPTION:
UNT013 IN SUCR 4.0
END DESCRIPTION:
XS GIS Cut Line= 4
      2303320.00     13434868.32      2303335.63     13435061.02
      2303642.92     13435446.44      2303991.92     13435555.83
#Sta/Elev= 30
  4504.5  454.05  4563.2  450.79  4593.3  450.32  4693.2  444.63  4739.3  442.86
  4760.1  442.76  4788.9  441.07  4867.4  439.35  4902.6  439.71  4966.7  439.20
  5006.9  437.52  5009.7  437.02  5012.9  437.52  5024.3  438.96  5051.5  440.28
  5123.6  441.48  5130.0  441.03  5144.4  441.61  5173.3  441.25  5312.7  445.47
  5363.5  447.88  5377.6  447.73  5404.8  449.06  5410.0  448.32  5426.3  449.60
  5480.2  450.86  5499.7  451.88  5507.4  451.48  5539.8  452.83  5556.5  452.88
#Mann=3,-1,0
  4504.5    0.05       0  5006.9    0.03       0  5012.9    0.05       0
Bank Sta=5006.9,5012.9
Exp/Cntr=0.3,0.1

Type RM Length L Ch R = 1,2814,130,130,130
BEGIN DESCRIPTION:
UNT013 IN SUCR 3.0
END DESCRIPTION:
XS GIS Cut Line= 4
      2303092.56     13434822.81      2303113.39     13435447.77
      2303134.22     13435562.35      2303653.85     13435785.79
#Sta/Elev= 30
  4330.0  454.58  4362.4  454.26  4419.6  452.38  4632.1  444.22  4724.3  439.69
  4744.3  437.84  4784.3  436.48  4864.3  434.81  4914.4  436.05  4932.3  434.29
  4937.3  433.20  4944.4  430.42  4952.3  429.71  4967.4  429.79  4969.2  429.80
  5083.5  429.39  5086.2  428.89  5089.5  429.39  5108.2  429.75  5122.8  432.51
  5130.0  433.14  5222.5  433.40  5269.5  434.43  5298.5  434.15  5304.2  434.89
  5445.2  436.64  5521.3  439.37  5532.8  439.07  5609.0  440.85  5637.4  442.09
#Mann=7,-1,0
  4330.0    0.05       0  4362.4     0.1       0  4419.6    0.05       0
  4967.4     0.1       0  4969.2    0.05       0  5083.5   0.035       0
  5089.5    0.05       0
Bank Sta=5083.5,5089.5
Exp/Cntr=0.3,0.1

Type RM Length L Ch R = 1,2684,110,110,110
BEGIN DESCRIPTION:
Mapping XS 6b6cb1dd
END DESCRIPTION:
XS GIS Cut Line= 5
      2302993.60     13434864.48      2303004.01     13435619.64
      2303108.18     13435656.10      2303139.43     13435666.52
      2303550.85     13435838.37
#Sta/Elev= 30
  4319.4  451.66  4521.8  445.78  4591.8  441.75  4789.5  434.04  4861.8  432.50
  4881.8  433.10  4913.1  436.11  4951.8  436.70  4991.8  434.96  5017.0  436.29
  5031.8  436.17  5061.8  432.79  5078.0  432.46  5079.6  431.28  5082.3  430.78
  5085.6  431.28  5108.3  433.48  5113.3  432.91  5139.4  435.76  5144.6  434.11
  5150.9  434.37  5170.4  434.86  5175.7  433.82  5201.8  435.91  5207.0  433.77
  5226.6  434.65  5232.1  433.27  5290.3  432.07  5395.6  433.33  5663.8  438.55
#Mann=11,-1,0
  4319.4     0.1       0  4521.8    0.05       0  4789.5     0.1       0
  4913.1    0.12       0  5017.0    0.05       0  5079.6    0.07       0
  5085.6    0.05       0  5113.3    0.12       0  5150.9    0.05       0
  5290.3     0.1       0  5395.6    0.05       0
Bank Sta=5079.6,5085.6
Exp/Cntr=0.3,0.1

Type RM Length L Ch R = 1,2574,194,194,194
BEGIN DESCRIPTION:
Mapping XS 35faaaea
END DESCRIPTION:
XS GIS Cut Line= 4
      2302869.97     13434960.39      2302875.86     13435495.98
      2302964.13     13435760.82      2303440.82     13435866.75
#Sta/Elev= 30
  4355.4  446.29  4391.9  445.37  4431.9  443.40  4471.9  443.10  4511.9  440.93
  4561.9  440.53  4571.9  439.39  4591.9  438.29  4641.9  437.27  4661.9  435.61
  4701.9  434.67  4731.9  432.89  4781.9  432.28  4801.9  431.67  4811.9  430.70
  4849.4  429.57  4861.9  428.77  4983.8  426.81  4986.6  426.31  4989.8  426.81
  5005.9  427.05  5105.2  428.69  5131.6  428.18  5276.3  430.15  5361.4  430.58
  5479.8  432.64  5532.4  433.96  5545.8  433.69  5635.4  435.27  5658.5  435.53
#Mann=7,-1,0
  4355.4     0.1       0  4849.4    0.12       0  4983.8    0.07       0
  4989.8    0.12       0  5005.9    0.05       0  5479.8     0.1       0
  5635.4    0.05       0
Bank Sta=4983.8,4989.8
Exp/Cntr=0.3,0.1

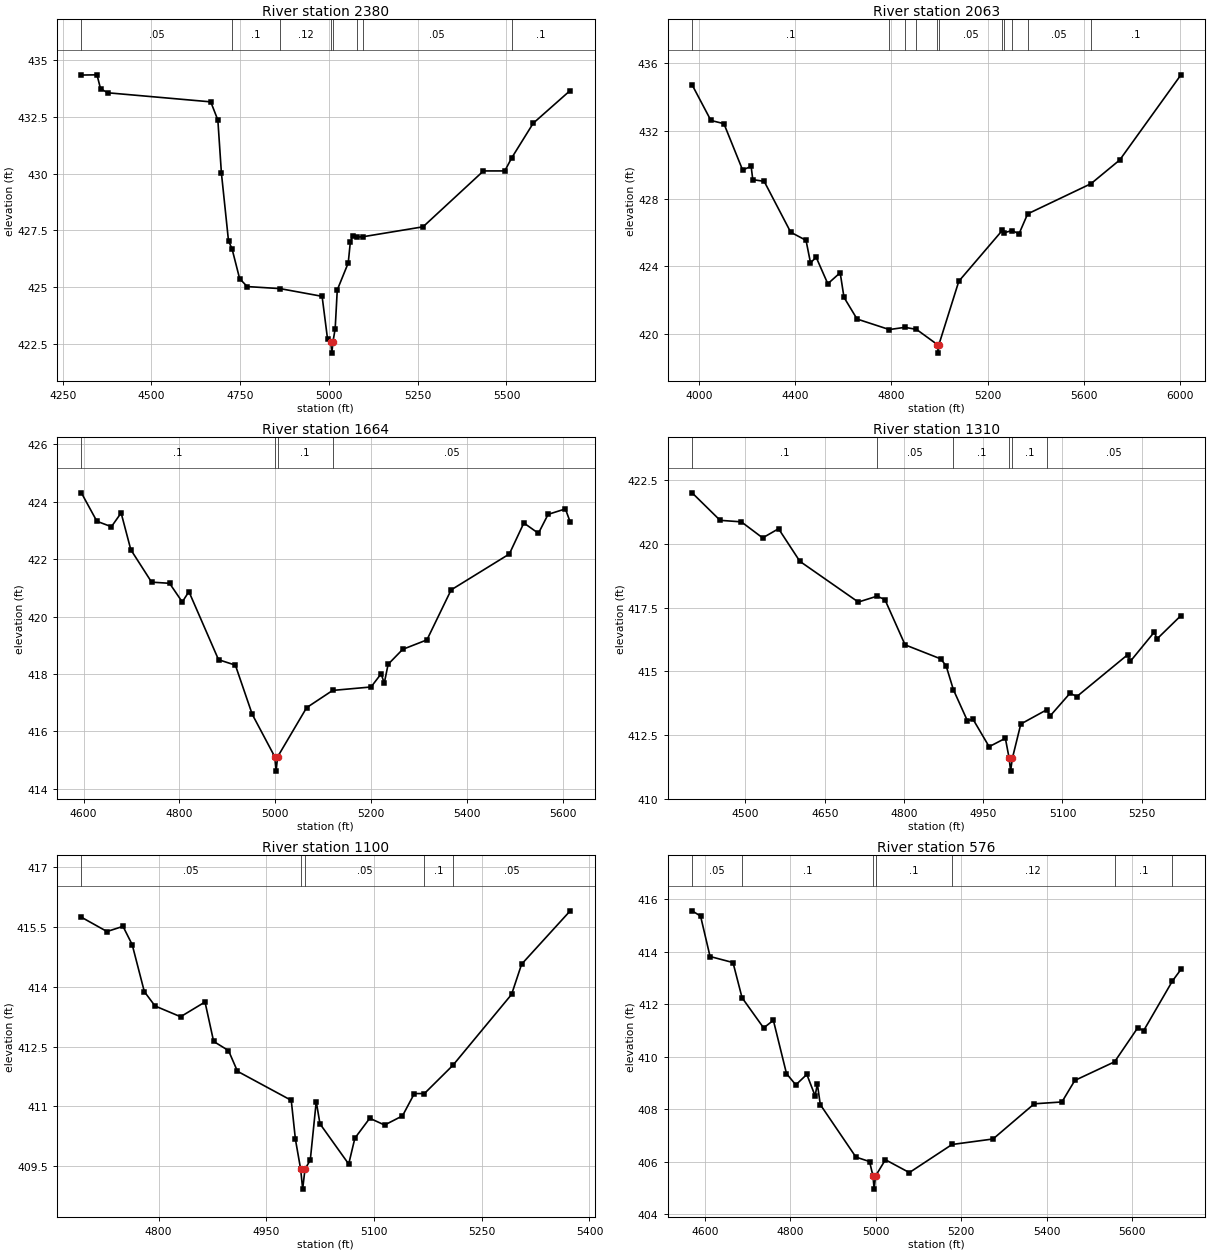
Type RM Length L Ch R = 1,2380,317,317,317
BEGIN DESCRIPTION:
Mapping XS c6014e0f
END DESCRIPTION:
XS GIS Cut Line= 4
      2302598.77     13435022.94      2302619.60     13435446.59
      2302869.60     13435856.32      2303341.80     13435877.15
#Sta/Elev= 30
  4302.7  434.34  4346.7  434.35  4356.7  433.74  4376.7  433.56  4667.1  433.16
  4687.1  432.36  4697.1  430.03  4717.1  427.04  4727.1  426.69  4748.4  425.38
  4769.7  425.03  4862.1  424.94  4980.7  424.60  4996.2  422.70  5005.3  422.60
  5008.1  422.10  5011.3  422.60  5017.5  423.17  5023.4  424.88  5054.3  426.07
  5060.1  426.97  5066.9  427.26  5080.1  427.21  5094.7  427.22  5265.0  427.66
  5435.2  430.12  5495.2  430.12  5514.9  430.70  5575.3  432.22  5679.5  433.66
#Mann=8,-1,0
  4302.7    0.05       0  4727.1     0.1       0  4862.1    0.12       0
  5005.3    0.07       0  5011.3    0.12       0  5080.1     0.1       0
  5094.7    0.05       0  5514.9     0.1       0
Bank Sta=5005.3,5011.3
Exp/Cntr=0.3,0.1

Type RM Length L Ch R = 1,2063,399,399,399
BEGIN DESCRIPTION:
UNT013 IN SUCR 2.1
END DESCRIPTION:
XS GIS Cut Line= 4
      2302311.30     13434958.22      2302165.47     13435572.77
      2302681.10     13435947.77      2303441.54     13435895.68
#Sta/Elev= 30
  3972.1  434.71  4050.2  432.61  4104.3  432.42  4181.9  429.69  4217.4  429.90
  4224.2  429.12  4271.5  429.02  4381.8  426.02  4445.5  425.54  4464.0  424.22
  4487.7  424.54  4536.0  422.98  4587.4  423.63  4603.2  422.18  4657.6  420.90
  4791.4  420.28  4856.4  420.41  4904.4  420.29  4991.6  419.39  4994.3  418.89
  4997.6  419.39  5080.4  423.13  5261.2  426.13  5269.1  425.99  5302.1  426.12
  5330.4  425.92  5366.4  427.10  5629.5  428.88  5749.1  430.28  6003.5  435.30
#Mann=11,-1,0
  3972.1     0.1       0  4791.4    0.05       0  4856.4     0.1       0
  4904.4    0.05       0  4991.6   0.035       0  4997.6    0.05       0
  5261.2     0.1       0  5269.1    0.05       0  5302.1     0.1       0
  5366.4    0.05       0  5629.5     0.1       0
Bank Sta=4991.6,4997.6
Exp/Cntr=0.3,0.1

Type RM Length L Ch R = 1,1664,354,354,354
BEGIN DESCRIPTION:
Mapping XS 6378bf50
END DESCRIPTION:
XS GIS Cut Line= 4
      2301981.29     13435554.81      2302016.61     13435790.25
      2302281.44     13436084.51      2302663.39     13436143.27
#Sta/Elev= 30
  4595.2  424.31  4627.6  423.32  4657.9  423.13  4678.2  423.61  4698.4  422.33
  4741.8  421.20  4779.3  421.16  4805.8  420.51  4819.7  420.87  4881.5  418.50
  4916.7  418.31  4951.8  416.60  4998.9  415.12  5001.6  414.62  5004.9  415.12
  5065.4  416.83  5119.7  417.43  5199.9  417.55  5220.9  418.01  5227.4  417.68
  5235.5  418.34  5265.9  418.86  5316.5  419.19  5367.0  420.93  5488.5  422.18
  5518.8  423.26  5549.2  422.90  5569.4  423.56  5605.5  423.75  5615.6  423.29
#Mann=4,-1,0
  4595.2     0.1       0  4998.9    0.07       0  5004.9     0.1       0
  5119.7    0.05       0
Bank Sta=4998.9,5004.9
Exp/Cntr=0.3,0.1

Type RM Length L Ch R = 1,1310,210,210,210
BEGIN DESCRIPTION:
UNT013 IN SUCR 2.0
END DESCRIPTION:
XS GIS Cut Line= 3
      2301821.72     13435774.14      2301864.83     13436177.95
      2302373.35     13436281.73
#Sta/Elev= 30
  4399.1  422.01  4452.1  420.93  4492.3  420.87  4532.6  420.24  4562.7  420.60
  4603.0  419.32  4713.6  417.72  4748.9  417.95  4763.9  417.82  4802.1  416.04
  4869.4  415.49  4879.7  415.22  4893.5  414.28  4920.0  413.06  4930.6  413.12
  4961.2  412.04  4991.9  412.37  4999.1  411.58  5001.8  411.08  5005.1  411.58
  5021.1  412.93  5070.2  413.49  5076.7  413.25  5114.3  414.14  5127.2  414.01
  5223.2  415.65  5228.3  415.39  5273.7  416.54  5278.8  416.27  5324.2  417.19
#Mann=6,-1,0
  4399.1     0.1       0  4748.9    0.05       0  4893.5     0.1       0
  4999.1    0.07       0  5005.1     0.1       0  5070.2    0.05       0
Bank Sta=4999.1,5005.1
Exp/Cntr=0.3,0.1

Type RM Length L Ch R = 1,1100,524,524,524
BEGIN DESCRIPTION:
Mapping XS 5e7d22cf
END DESCRIPTION:
XS GIS Cut Line= 4
      2301823.19     13436224.79      2301893.54     13436367.56
      2302210.02     13436452.36      2302375.45     13436351.03
#Sta/Elev= 30
  4692.4  415.75  4728.1  415.39  4750.4  415.52  4763.2  415.06  4780.1  413.88
  4795.0  413.52  4830.6  413.25  4864.6  413.62  4876.6  412.63  4897.3  412.40
  4909.8  411.88  4984.7  411.15  4990.5  410.17  4997.8  409.42  5000.6  408.92
  5003.8  409.42  5011.2  409.65  5019.5  411.12  5024.7  410.56  5064.7  409.55
  5073.3  410.20  5094.0  410.70  5114.7  410.53  5139.6  410.76  5156.1  411.32
  5170.1  411.32  5209.8  412.03  5291.5  413.81  5305.5  414.57  5373.2  415.91
#Mann=5,-1,0
  4692.4    0.05       0  4997.8   0.035       0  5003.8    0.05       0
  5170.1     0.1       0  5209.8    0.05       0
Bank Sta=4997.8,5003.8
Exp/Cntr=0.3,0.1

Type RM Length L Ch R = 1,576,0,0,0
BEGIN DESCRIPTION:
UNT013 IN SUCR 1.0
END DESCRIPTION:
XS GIS Cut Line= 5
      2301779.78     13436260.00      2301659.81     13436479.25
      2301732.20     13436700.58      2301939.05     13436688.17
      2302333.43     13436463.10
#Sta/Elev= 30
  4570.1  415.55  4589.9  415.35  4612.1  413.81  4665.8  413.58  4687.0  412.24
  4737.5  411.09  4760.3  411.38  4791.0  409.35  4812.8  408.92  4838.6  409.32
  4858.0  408.50  4863.2  408.96  4870.1  408.17  4953.5  406.17  4985.4  406.00
  4993.4  405.45  4996.1  404.95  4999.4  405.45  5022.5  406.07  5078.5  405.58
  5178.4  406.65  5274.4  406.86  5370.8  408.20  5435.6  408.27  5465.8  409.09
  5558.9  409.80  5612.8  411.09  5627.0  410.99  5694.3  412.88  5714.2  413.32
#Mann=7,-1,0
  4570.1    0.05       0  4687.0     0.1       0  4993.4    0.07       0
  4999.4     0.1       0  5178.4    0.12       0  5558.9     0.1       0
  5694.3    0.05       0
Bank Sta=4993.4,4999.4
Exp/Cntr=0.3,0.1

Chan Stop Cuts=-1