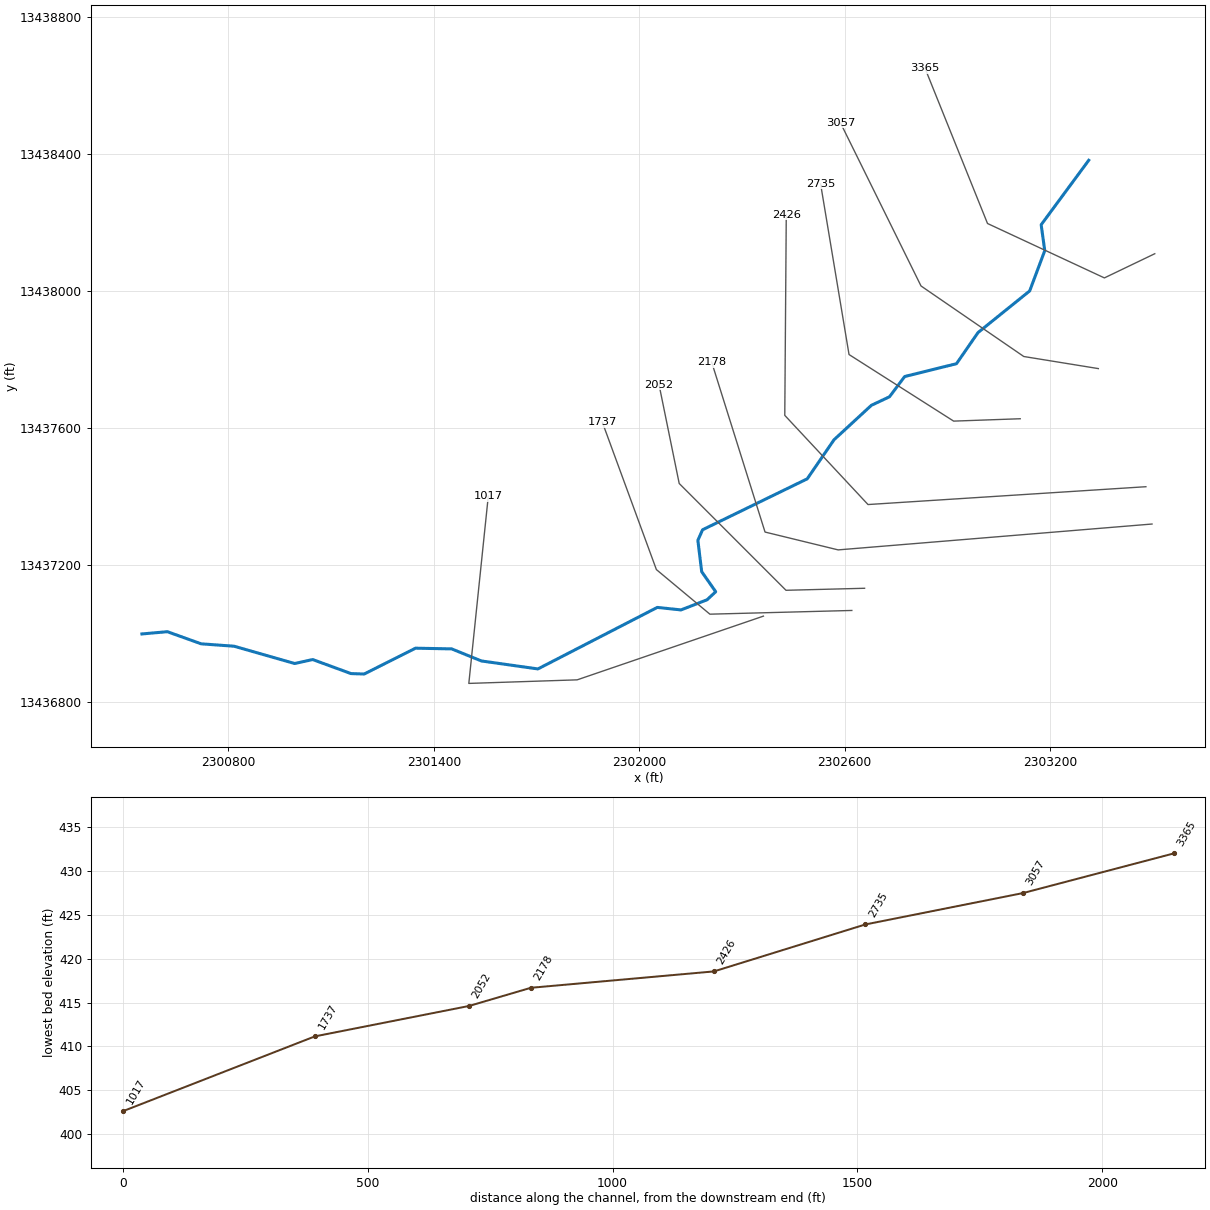
--- UNT014 IN SUCR.prj (project) ---

Proj Title=UNT014 IN SUCR Base Level Engineering
Current Plan=p01
Default Exp/Contr=0.3,0.1
English Units
Geom File=g01
Flow File=f01
Plan File=p01
Y Axis Title=Elevation
X Axis Title(PF)=Main Channel Distance
X Axis Title(XS)=Station
BEGIN DESCRIPTION:
UNT014 IN SUCR
END DESCRIPTION:
DSS Export Rating Curves= 0
DSS Export Rating Curve Sorted= 0
DSS Export Volume Flow Curves= 0
DXF OffsetX= 0
DXF OffsetY= 0
DXF ScaleX= 1
DXF ScaleY= 10

--- UNT014 IN SUCR.p01 (plan) ---

Plan Title=Multiple Run
Short Identifier=Multiple
Geom File=g01
Flow File=f01
Subcritical Flow
K Sum by GR= 0
Std Step Tol= 0.01
Critical Tol= 0.01
Num of Std Step Trials= 20
Max Error Tol= 0.3
Flow Tol Ratio= 0.001
Split Flow NTrial= 30
Split Flow Tol= 0.02
Split Flow Ratio= 0.02
Log Output Level= 0
Friction Slope Method= 1
Unsteady Friction Slope Method= 2
Unsteady Bridges Friction Slope Method= 1
Parabolic Critical Depth
Global Vel Dist=  1 , 1 , 1
Global Log Level= 0
CheckData=True
Encroach Param= -1, 0, 0, 0
BEGIN DESCRIPTION:
Multiple Run
END DESCRIPTION:

--- UNT014 IN SUCR.f01 (steady flow) ---

Flow Title=Multiple
Program Version=4.10
Number of Profiles= 7
Profile Names=10-year,25-year,50-year,1pct_min,100-year,1pct_plu,500-year
River Rch & RM=UNT014 IN SUCR,Reach-1         ,3365
     264     358     433     385     521     705     754
Boundary for River Rch & Prof#=UNT014 IN SUCR,Reach-1         , 1
Up Type= 0
Dn Type= 3
Dn Slope=0.013
Boundary for River Rch & Prof#=UNT014 IN SUCR,Reach-1         , 2
Up Type= 0
Dn Type= 3
Dn Slope=0.013
Boundary for River Rch & Prof#=UNT014 IN SUCR,Reach-1         , 3
Up Type= 0
Dn Type= 3
Dn Slope=0.013
Boundary for River Rch & Prof#=UNT014 IN SUCR,Reach-1         , 4
Up Type= 0
Dn Type= 3
Dn Slope=0.013
Boundary for River Rch & Prof#=UNT014 IN SUCR,Reach-1         , 5
Up Type= 0
Dn Type= 3
Dn Slope=0.013
Boundary for River Rch & Prof#=UNT014 IN SUCR,Reach-1         , 6
Up Type= 0
Dn Type= 3
Dn Slope=0.013
Boundary for River Rch & Prof#=UNT014 IN SUCR,Reach-1         , 7
Up Type= 0
Dn Type= 3
Dn Slope=0.013
DSS Import GetInterval= 0
DSS Import GetPeak= 0
DSS Import FillOption= 0

--- UNT014 IN SUCR.g01 (geometry) ---

Geom Title=Existing Conditions
Program Version=4.10

River Reach=UNT014 IN SUCR  ,Reach-1
Reach XY= 30
      2303312.72     13438381.86      2303173.78     13438193.65
      2303184.31     13438117.93      2303140.27     13438000.38
      2302989.28     13437878.69      2302926.51     13437787.89
      2302775.19     13437750.43      2302730.92     13437691.31
      2302677.93     13437666.38      2302568.91     13437565.83
      2302490.56     13437451.64      2302184.99     13437302.95
      2302171.19     13437272.12      2302182.35      13437180.5
      2302223.29     13437121.99      2302197.95     13437098.43
      2302121.98     13437068.87      2302052.68     13437076.21
      2301704.03     13436896.53      2301538.95     13436919.83
      2301452.15     13436955.09      2301346.61     13436957.11
      2301196.56     13436881.68      2301158.06     13436882.98
      2301046.39     13436923.92      2300993.72     13436912.37
      2300816.92     13436962.83      2300720.56     13436969.85
      2300621.85     13437005.28      2300547.55      13436998.7

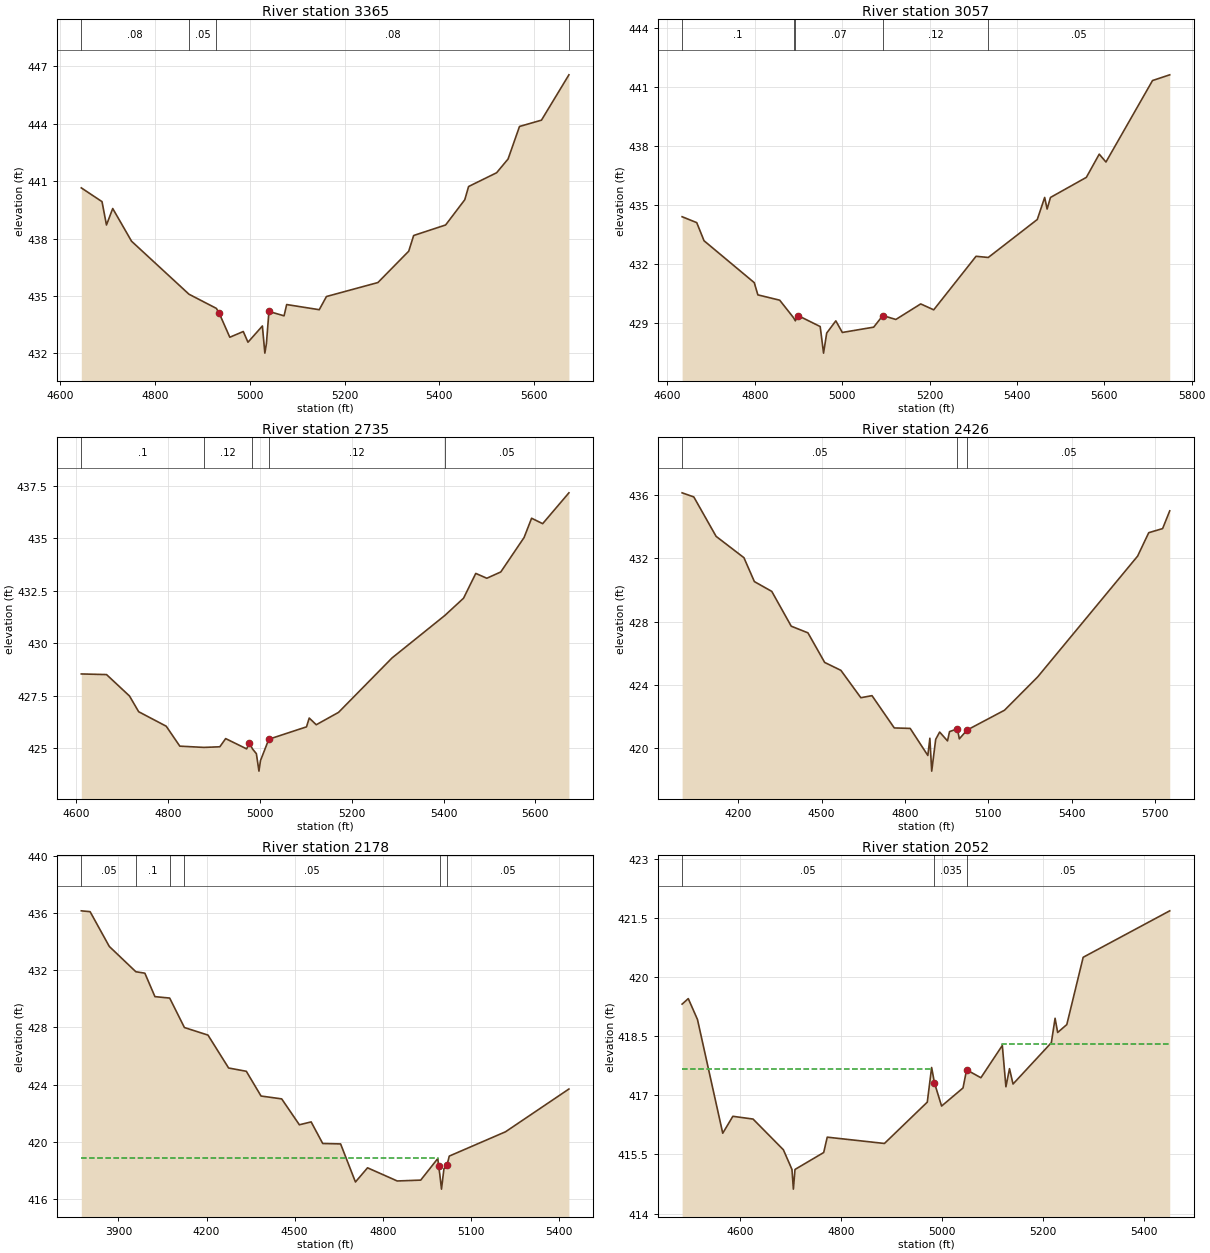
Type RM Length L Ch R = 1 ,3365    ,308,308,308
BEGIN DESCRIPTION:
UNT014 IN SUCR 3.0
END DESCRIPTION:
XS GIS Cut Line= 4
       2303505.6     13438109.05      2303358.45     13438038.42
       2303017.1     13438197.32      2302834.64     13438650.53
#Sta/Elev= 30
  4644.9  440.65  4688.6  439.93    4698  438.71  4711.2  439.57  4750.9  437.86
    4872  435.09  4929.7  434.35  4935.3  434.12  4958.1  432.84  4986.5  433.14
  4996.4  432.58  5026.8  433.43    5032  432.01  5035.3  432.51  5040.6  434.19
  5072.5  433.96    5078  434.55  5146.7  434.28  5161.9  434.97  5270.4   435.7
  5335.4  437.34  5345.8  438.16  5413.2  438.71  5453.6  440.03  5461.6  440.72
  5520.7  441.44  5544.9  442.16    5569  443.86  5615.3  444.19  5673.2  446.56
#Mann= 4 ,-1 , 0
  4644.9     .08       0    4872     .05       0  4929.7     .08       0
  5673.2     .05       0
Bank Sta=4935.3,5040.6
XS Rating Curve= 0 ,0
Exp/Cntr=0.3,0.1

Type RM Length L Ch R = 1 ,3057    ,322,322,322
BEGIN DESCRIPTION:
UNT014 IN SUCR 2.0
END DESCRIPTION:
XS GIS Cut Line= 4
      2303340.77     13437773.59      2303123.04      13437808.9
      2302822.89     13438014.88      2302587.46     13438491.61
#Sta/Elev= 30
  4633.5  434.42    4667  434.12  4683.7   433.2  4798.7  431.07  4806.9  430.45
  4856.9  430.18  4888.6  429.29  4892.7  429.13  4898.8   429.4  4949.6  428.84
  4957.3  427.49  4964.5  428.51  4985.4  429.13  5000.3  428.54  5072.1  428.81
    5093   429.4  5122.8   429.2  5179.7  429.99  5209.5  429.69  5306.4  432.41
  5334.4  432.35  5446.6  434.28  5463.5   435.4  5469.1  434.81  5476.8   435.4
  5558.9  436.42  5588.4   437.6  5603.8   437.2  5710.4  441.34  5749.8  441.63
#Mann= 5 ,-1 , 0
  4633.5      .1       0  4888.6     .12       0  4892.7     .07       0
    5093     .12       0  5334.4     .05       0
Bank Sta=4898.8,5093
XS Rating Curve= 0 ,0
Exp/Cntr=0.3,0.1

Type RM Length L Ch R = 1 ,2735    ,309,309,309
BEGIN DESCRIPTION:
Mapping XS 89a62d4b
END DESCRIPTION:
XS GIS Cut Line= 4
      2303112.64     13437627.15      2302918.21     13437620.21
      2302612.66     13437814.65      2302529.56     13438313.25
#Sta/Elev= 30
    4611  428.54    4666  428.51    4716  427.49    4736  426.74    4796  426.05
  4825.6   425.1  4878.1  425.04  4912.8  425.07  4925.5  425.46  4971.2  424.97
  4977.1  425.26  4983.9  424.97  4992.4  424.74    4998  423.91  5001.3  424.41
  5019.5  425.43  5101.6  426.02  5107.5  426.44  5122.8  426.12  5171.4  426.71
  5287.8   429.3  5403.1  431.33  5443.7  432.15  5470.3  433.33  5494.4   433.1
  5524.8   433.4  5575.5  435.04  5591.9  435.96    5616   435.7  5673.2  437.17
#Mann= 5 ,-1 , 0
    4611      .1       0  4878.1     .12       0  4983.9     .07       0
  5019.5     .12       0  5403.1     .05       0
Bank Sta=4977.1,5019.5
XS Rating Curve= 0 ,0
Exp/Cntr=0.3,0.1

Type RM Length L Ch R = 1 ,2426    ,374,374,374
BEGIN DESCRIPTION:
Mapping XS f4aee5f31
END DESCRIPTION:
XS GIS Cut Line= 4
      2303479.74     13437428.67      2302668.08     13437376.59
      2302425.02       13437637.      2302429.36     13438222.43
#Sta/Elev= 30
    3998  436.15  4040.1  435.89  4120.3   433.4  4220.5  432.05  4258.1  430.54
  4320.7  429.92  4390.8  427.72  4450.9   427.3  4511.1  425.43  4569.5  424.93
  4641.3   423.2  4681.4  423.33  4761.6  421.29  4818.9  421.26  4882.4  419.55
  4889.7  420.64  4896.3  418.56  4910.7  420.57  4924.9  421.03  4953.2  420.47
  4960.5  421.06  4988.9  421.23  4995.7   420.6    5024  421.16  5158.4  422.41
  5277.4  424.51  5637.4  432.15  5677.4  433.63  5727.4  433.89    5753  435.01
#Mann= 3 , 0 , 0
    3998     .05       0  4988.9     .03       0    5024     .05       0
#XS Ineff= 1 ,-1
 4794.25  4987.6  421.09
Permanent Ineff=
       T
Bank Sta=4988.9,5024
XS Rating Curve= 0 ,0
Exp/Cntr=0.3,0.1

Type RM Length L Ch R = 1 ,2178    ,126,126,126
BEGIN DESCRIPTION:
Mapping XS f4aee5f31
END DESCRIPTION:
XS GIS Cut Line= 4
      2303497.58     13437319.69      2302580.91     13437244.16
      2302367.37     13437296.25       2302211.4     13437792.75
#Sta/Elev= 30
  3773.6  436.15  3803.6  436.09  3868.9  433.66  3959.4  431.89    3990  431.79
  4024.3  430.15  4074.5  430.05  4124.6  427.99  4204.9  427.46  4275.1  425.16
  4335.4  424.93  4385.5   423.2  4455.8     423    4516  421.19  4556.1  421.39
  4595.5  419.88  4656.4  419.85  4706.9  417.19  4748.1  418.18  4849.2  417.26
  4929.1  417.32  4987.2  418.83 4990.13   418.3  4993.9  417.75  4999.8  416.69
  5008.1  418.11  5018.6  418.37  5026.3     419  5217.8   420.7  5433.6  423.69
#Mann= 6 ,-1 , 0
  3773.6     .05       0  3959.4      .1       0  4074.5     .05       0
  4124.6     .05       0  4993.9     .03       0  5018.6     .05       0
#XS Ineff= 2 , 0
         4986.32  418.85
Permanent Ineff=
       T       T
Bank Sta=4990.13,5018.6
XS Rating Curve= 0 ,0
Exp/Cntr=0.3,0.1

Type RM Length L Ch R = 1 ,2052    ,315,315,315
BEGIN DESCRIPTION:
Mapping XS f4
END DESCRIPTION:
XS GIS Cut Line= 4
       2302658.1     13437132.09      2302428.57      13437126.2
      2302116.66     13437438.12      2302057.81     13437726.46
#Sta/Elev= 30
  4485.7  419.32  4497.9  419.46  4516.1  418.93  4566.1  416.04  4586.1  416.47
  4626.1   416.4  4686.1  415.62  4703.1  415.12  4705.9  414.62  4709.1  415.12
  4765.9  415.55  4772.9  415.94  4886.1  415.78  4970.9  416.83 4979.48  417.71
  4985.1  417.32  4999.2  416.73  5041.6  417.19  5048.7  417.65    5077  417.45
  5119.4  418.27  5126.5  417.22  5133.6  417.68  5140.6  417.29  5216.4  418.34
  5223.8  418.96  5228.9   418.6    5247   418.8  5279.4  420.51  5450.7  421.69
#Mann= 3 , 0 , 0
  4485.7     .05       0  4985.1    .035       0  5048.7     .05       0
#XS Ineff= 2 , 0
       0  4980.2  417.67 5119.37       0  418.31
Permanent Ineff=
       T       T
Bank Sta=4985.1,5048.7
XS Rating Curve= 0 ,0
Exp/Cntr=0.3,0.1

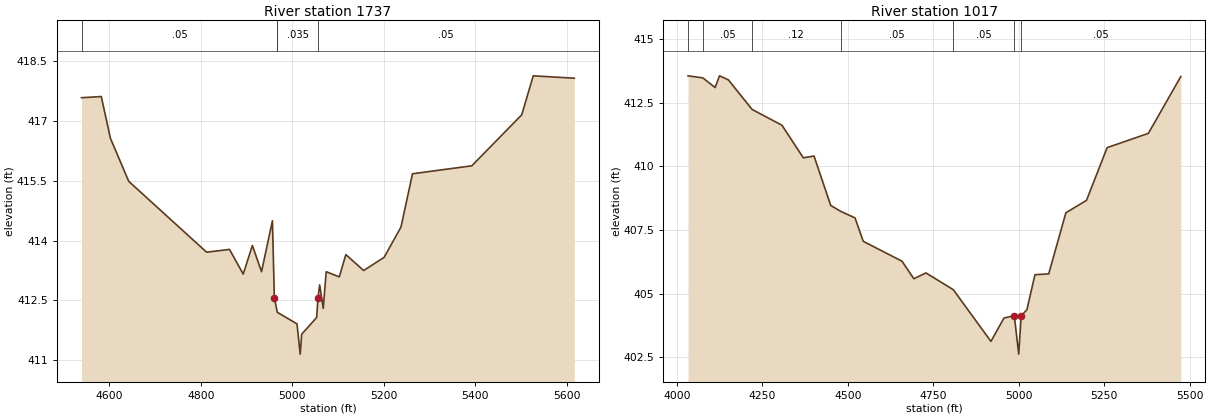
Type RM Length L Ch R = 1 ,1737    ,392,392,392
BEGIN DESCRIPTION:
Mapping XS f4aee5f3
END DESCRIPTION:
XS GIS Cut Line= 4
      2302620.83     13437067.29      2302206.29     13437056.44
      2302050.04     13437186.65      2301892.16     13437617.04
#Sta/Elev= 30
  4539.7  417.59  4582.8  417.62  4602.8  416.57  4642.8  415.49  4812.9  413.71
  4862.9  413.78  4892.9  413.16  4912.9  413.88  4932.9  413.22  4956.7   414.5
  4960.9  412.57  4967.4   412.2  5010.4  411.91  5017.4  411.15  5020.6  411.65
  5053.3  412.07 5056.25  412.57  5059.9  412.89  5067.7   412.3  5074.2  413.22
  5102.8  413.09  5117.1  413.65    5156  413.25  5200.6  413.58  5237.5  414.34
  5262.7  415.68  5392.3  415.88  5501.3  417.16  5526.5  418.14  5616.2  418.08
#Mann= 4 ,-1 , 0
  4539.7     .05       0  4967.4      .1       0  4967.4    .035       0
 5056.25     .05       0
Bank Sta=4960.9,5056.25
XS Rating Curve= 0 ,0
Exp/Cntr=0.3,0.1

Type RM Length L Ch R = 1 ,1017    ,0,0,0
BEGIN DESCRIPTION:
UNT014 IN SUCR 1.0
END DESCRIPTION:
XS GIS Cut Line= 4
      2302362.62     13437050.75      2301818.65     13436864.66
      2301502.24     13436854.25       2301559.1      13437401.1
#Sta/Elev= 30
  4032.5  413.55  4075.8  413.47  4111.7  413.09  4124.6  413.55  4150.7  413.39
  4219.9  412.23  4307.2  411.61  4369.8  410.33  4401.1   410.4  4449.9  408.46
  4478.7  408.23    4521  407.97    4545  407.05  4658.4  406.27  4693.1  405.58
  4728.4  405.81  4808.5  405.15  4918.5  403.12  4956.8  404.04  4986.9  404.13
  4999.8  402.62    5007  404.13  5023.7  404.36  5047.3  405.74  5087.5  405.77
  5137.7  408.17  5198.1  408.66  5258.4  410.73    5379  411.29  5473.8  413.52
#Mann= 7 ,-1 , 0
  4032.5      .1       0  4075.8     .05       0  4219.9     .12       0
  4478.7     .05       0  4808.5     .05       0  4986.9     .03       0
    5007     .05       0
Bank Sta=4986.9,5007
XS Rating Curve= 0 ,0
Exp/Cntr=0.3,0.1

Chan Stop Cuts=-1
Use User Specified Reach Order=0
Composite Channel Slope=5