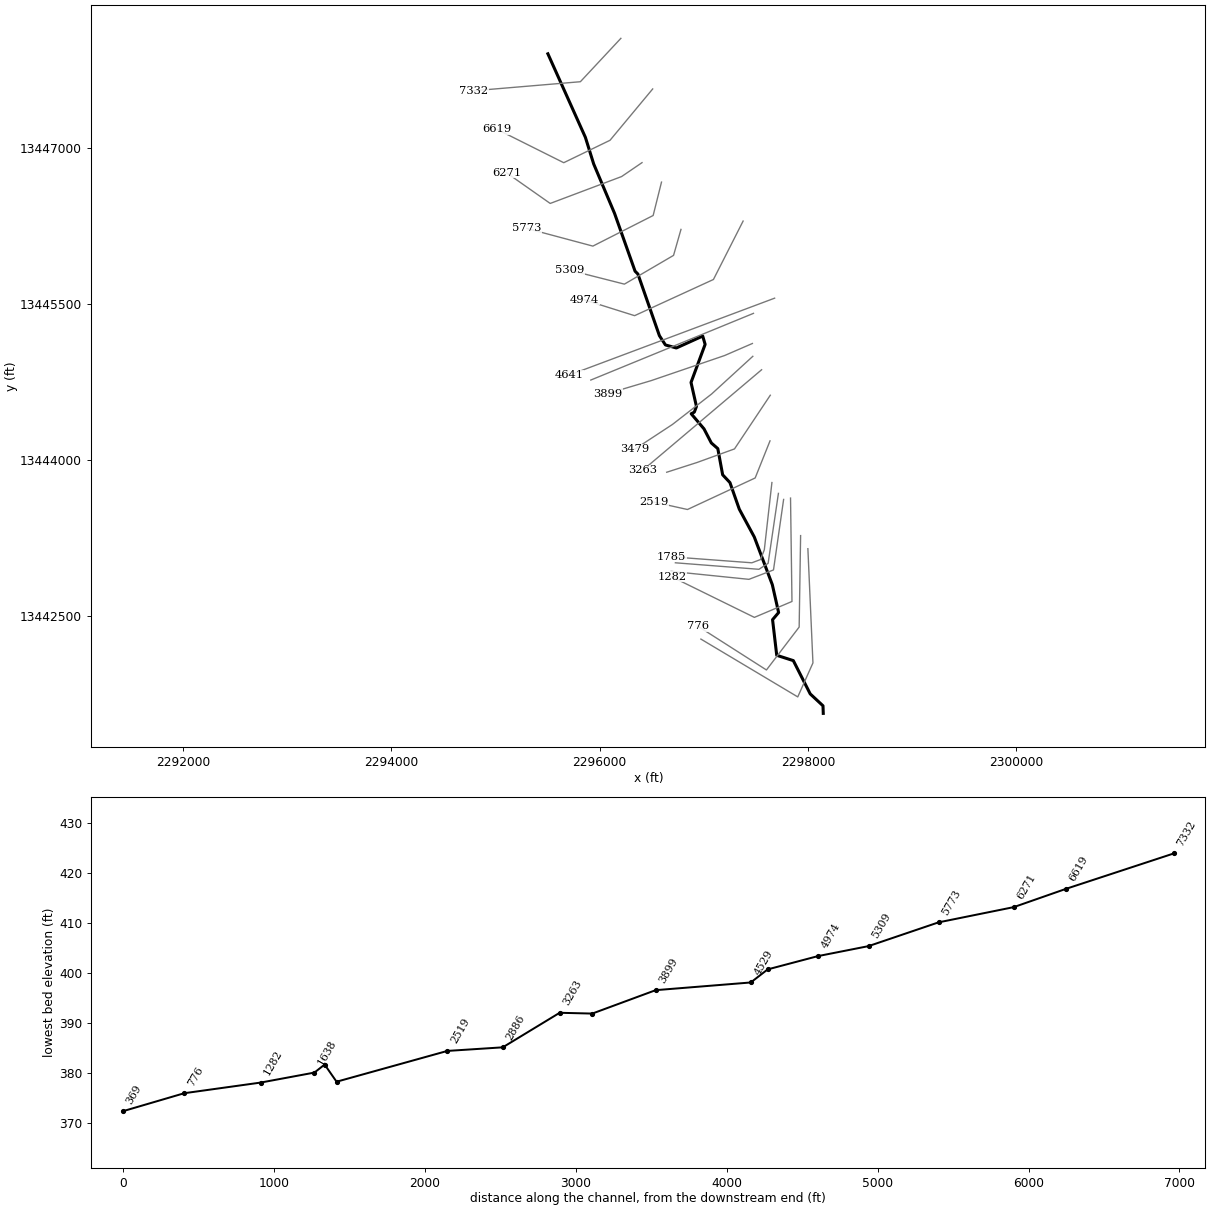
--- UNT015 IN SUCR.prj (project) ---

Proj Title=UNT015 IN SUCR Base Level Engineering
Current Plan=p01
Default Exp/Contr=0.3,0.1
English Units
Geom File=g01
Flow File=f01
Plan File=p01
Y Axis Title=Elevation
X Axis Title(PF)=Main Channel Distance
X Axis Title(XS)=Station
BEGIN DESCRIPTION:
UNT015 IN SUCR
END DESCRIPTION:
DSS Export Rating Curves= 0
DSS Export Rating Curve Sorted= 0
DSS Export Volume Flow Curves= 0
DXF OffsetX= 0
DXF OffsetY= 0
DXF ScaleX= 1
DXF ScaleY= 10

--- UNT015 IN SUCR.p01 (plan) ---

Plan Title=Multiple Run
Short Identifier=Multiple
Geom File=g01
Flow File=f01
Subcritical Flow
K Sum by GR= 0
Std Step Tol= 0.01
Critical Tol= 0.01
Num of Std Step Trials= 20
Max Error Tol= 0.3
Flow Tol Ratio= 0.001
Split Flow NTrial= 30
Split Flow Tol= 0.02
Split Flow Ratio= 0.02
Log Output Level= 0
Friction Slope Method= 1
Unsteady Friction Slope Method= 2
Unsteady Bridges Friction Slope Method= 1
Parabolic Critical Depth
Global Vel Dist=  1 , 1 , 1
Global Log Level= 0
CheckData=True
Encroach Param= -1, 0, 0, 0
BEGIN DESCRIPTION:
Multiple Run
END DESCRIPTION:

--- UNT015 IN SUCR.f01 (steady flow) ---

Flow Title=Multiple
Program Version=4.10
Number of Profiles= 7
Profile Names=10-year,25-year,50-year,1pct_min,100-year,1pct_plu,500-year
River Rch & RM=UNT015 IN SUCR,Reach-1         ,7332
     204     268     318     276     374     505     517
River Rch & RM=UNT015 IN SUCR,Reach-1         ,4641
     350     477     579     515     696     941    1008
River Rch & RM=UNT015 IN SUCR,Reach-1         ,3263
     434     599     734     658     889    1203    1311
Boundary for River Rch & Prof#=UNT015 IN SUCR,Reach-1         , 1
Up Type= 0
Dn Type= 3
Dn Slope=0.0091
Boundary for River Rch & Prof#=UNT015 IN SUCR,Reach-1         , 2
Up Type= 0
Dn Type= 3
Dn Slope=0.0091
Boundary for River Rch & Prof#=UNT015 IN SUCR,Reach-1         , 3
Up Type= 0
Dn Type= 3
Dn Slope=0.0091
Boundary for River Rch & Prof#=UNT015 IN SUCR,Reach-1         , 4
Up Type= 0
Dn Type= 3
Dn Slope=0.0091
Boundary for River Rch & Prof#=UNT015 IN SUCR,Reach-1         , 5
Up Type= 0
Dn Type= 3
Dn Slope=0.0091
Boundary for River Rch & Prof#=UNT015 IN SUCR,Reach-1         , 6
Up Type= 0
Dn Type= 3
Dn Slope=0.0091
Boundary for River Rch & Prof#=UNT015 IN SUCR,Reach-1         , 7
Up Type= 0
Dn Type= 3
Dn Slope=0.0091
DSS Import GetInterval= 0
DSS Import GetPeak= 0
DSS Import FillOption= 0

--- UNT015 IN SUCR.g01 (geometry) ---

Geom Title=Existing Conditions
Program Version=4.10

River Reach=UNT015 IN SUCR  ,Reach-1
Reach XY= 30
      2295502.72     13447901.86      2295862.95     13447099.58
      2295942.52     13446844.13      2296142.97     13446369.61
      2296340.16     13445813.85      2296367.55     13445786.31
      2296573.95     13445194.52      2296631.73     13445105.55
      2296736.39     13445076.34      2296989.75     13445191.01
      2297013.08     13445111.06      2296877.63     13444745.24
      2296929.71     13444514.77      2296909.05     13444459.91
      2296879.28     13444444.72      2297002.28     13444299.37
      2297072.68     13444164.15      2297134.88     13444109.71
      2297181.37     13443858.29      2297251.32     13443783.69
      2297341.12     13443528.25       2297485.2     13443261.08
      2297658.53      13442802.6      2297718.86     13442535.46
      2297660.73     13442466.76      2297700.75      13442124.7
      2297860.22     13442073.48      2298022.34     13441753.97
      2298145.14     13441639.62      2298147.72     13441566.85

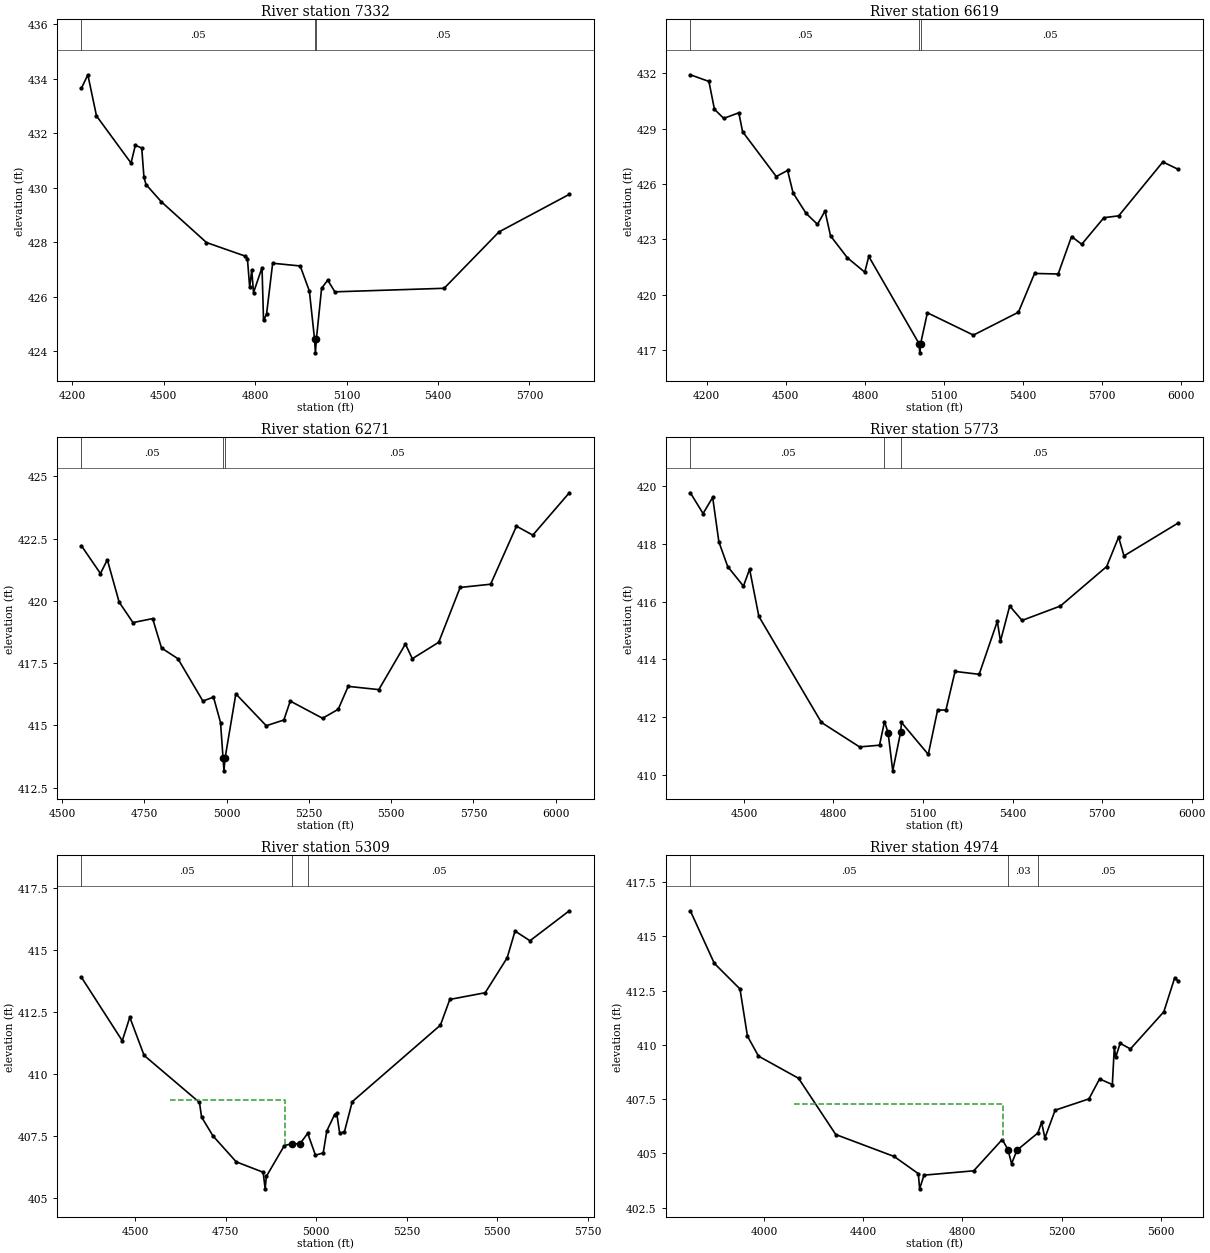
Type RM Length L Ch R = 1 ,7332    ,713,713,713
BEGIN DESCRIPTION:
UNT015 IN SUCR 11.0
END DESCRIPTION:
XS GIS Cut Line= 3
      2296203.79     13448050.46      2295814.86     13447633.76
      2294787.74     13447546.86
#Sta/Elev= 30
  4230.2  433.66    4251  434.15  4279.4  432.64  4392.7  430.91  4406.9  431.56
  4427.9  431.46  4435.2  430.38    4442  430.12  4491.9  429.49  4640.4  427.99
  4767.9  427.49  4774.7   427.4  4782.1  426.35  4788.9  426.97  4794.7  426.15
  4822.6  427.07  4827.6  425.13  4837.5  425.36  4857.5  427.23  4947.9  427.13
    4978  426.21    4995  424.44  4997.8  423.94    5001  424.44  5018.1  426.31
  5038.2  426.61  5061.6  426.18  5420.2  426.31  5600.2  428.38    5831  429.76
#Mann= 3 ,-1 , 0
  4230.2     .05       0    4995    .035       0    5001     .05       0
Bank Sta=4995,5001
XS Rating Curve= 0 ,0
Exp/Cntr=0.3,0.1

Type RM Length L Ch R = 1 ,6619    ,348,348,348
BEGIN DESCRIPTION:
UNT015 IN SUCR 10.0
END DESCRIPTION:
XS GIS Cut Line= 4
       2296509.3      13447564.3      2296099.59     13447071.26
      2295655.14     13446855.98      2295016.25     13447175.43
#Sta/Elev= 30
  4138.2  431.92  4208.7  431.56  4229.6  430.05  4264.9  429.56    4322  429.86
  4336.3  428.84  4463.9  426.41  4506.9  426.74  4527.7  425.52  4577.2  424.41
  4620.2  423.82  4648.8  424.54  4669.6   423.2  4733.4  422.01  4799.4  421.23
  4814.7  422.08  5005.2  417.36  5007.9  416.86  5011.2  417.36  5036.9  419.03
  5211.4  417.82    5382  419.06  5443.1  421.16  5532.6  421.13  5583.3  423.16
    5622  422.74  5705.9  424.18  5762.1  424.28  5929.5   427.2  5987.4   426.8
#Mann= 3 ,-1 , 0
  4138.2     .05       0  5005.2     .03       0  5011.2     .05       0
Bank Sta=5005.2,5011.2
XS Rating Curve= 0 ,0
Exp/Cntr=0.3,0.1

Type RM Length L Ch R = 1 ,6271    ,498,498,498
BEGIN DESCRIPTION:
UNT015 IN SUCR 9.0
END DESCRIPTION:
XS GIS Cut Line= 4
       2296406.9     13446856.57      2296210.96     13446722.97
      2295525.05     13446464.64      2295106.34     13446758.63
#Sta/Elev= 30
  4559.4  422.21  4616.9   421.1  4637.9  421.65  4673.8  419.95  4715.8  419.13
  4775.5  419.29  4802.5  418.11  4852.3  417.68  4928.2  415.98  4960.3  416.14
  4981.7  415.12  4989.4  413.68  4992.1  413.18  4995.4  413.68  5028.2  416.27
  5120.6  414.99    5174  415.22  5193.5  415.98  5291.6  415.29  5339.2  415.65
  5369.4  416.57  5462.5  416.44  5543.3  418.27  5564.2  417.68  5644.4  418.34
  5709.5  420.54  5802.1  420.67  5880.6     423  5930.2  422.64  6041.1  424.34
#Mann= 3 ,-1 , 0
  4559.4     .05       0  4989.4     .03       0  4995.4     .05       0
Bank Sta=4989.4,4995.4
XS Rating Curve= 0 ,0
Exp/Cntr=0.3,0.1

Type RM Length L Ch R = 1 ,5773    ,464,464,464
BEGIN DESCRIPTION:
UNT015 IN SUCR 8.0
END DESCRIPTION:
XS GIS Cut Line= 4
      2296594.01     13446669.56      2296513.83     13446348.84
      2295934.82     13446054.88      2295302.52     13446224.08
#Sta/Elev= 30
  4320.3  419.78    4363  419.06  4395.2  419.62  4415.9  418.08  4445.5  417.22
  4498.3  416.54  4518.9  417.13  4549.9  415.49  4759.5  411.81  4887.4  410.96
  4954.2  411.02  4970.9  411.84    4983  411.45  4998.5  410.13 5025.34  411.49
  5027.8  411.81  5117.6   410.7  5148.9  412.24  5176.8  412.24  5207.3  413.58
  5288.1  413.48    5349  415.32  5359.4  414.63  5390.4  415.85  5431.8  415.35
  5560.3  415.85  5715.3  417.22  5755.3  418.24  5773.4  417.59  5954.8  418.73
#Mann= 3 ,-1 , 0
  4320.3     .05       0  4970.9     .03       0  5027.8     .05       0
Bank Sta=4983,5025.34
XS Rating Curve= 0 ,0
Exp/Cntr=0.3,0.1

Type RM Length L Ch R = 1 ,5309    ,335,335,335
BEGIN DESCRIPTION:
UNT015 IN SUCR 7.0
END DESCRIPTION:
XS GIS Cut Line= 4
      2296781.08     13446215.24      2296709.81      13445965.8
      2296237.69     13445689.65      2295712.37     13445823.21
#Sta/Elev= 30
  4351.2  413.91  4463.9  411.35  4484.7   412.3  4524.2  410.76  4677.3  408.86
  4683.1  408.27  4714.5  407.51    4779  406.46  4853.3  406.04  4858.9  405.37
  4862.1  405.87    4912  407.12  4933.5  407.19    4955  407.19  4976.5  407.61
  4997.9  406.73  5019.4  406.82  5029.3  407.71  5050.8  408.37  5056.6  408.43
  5064.9  407.61  5078.1  407.68  5099.6  408.89  5343.3  411.98  5369.3  413.02
  5467.1  413.29  5527.8   414.7  5549.6  415.78  5590.9  415.39  5699.6   416.6
#Mann= 3 ,-1 , 0
  4351.2     .05       0  4933.5     .03       0  4976.5     .05       0
#XS Ineff= 1 ,-1
 4596.19 4914.63408.9547
Permanent Ineff=
       F
Bank Sta=4933.5,4955
XS Rating Curve= 0 ,0
Exp/Cntr=0.3,0.1

Type RM Length L Ch R = 1 ,4974    ,333,333,333
BEGIN DESCRIPTION:
UNT015 IN SUCR 6.0
END DESCRIPTION:
XS GIS Cut Line= 4
       2297377.9     13446295.38      2297092.85     13445734.19
      2296335.67     13445386.78      2295854.65     13445538.21
#Sta/Elev= 30
  3702.8  416.17  3799.5  413.75    3903  412.57  3933.1   410.4  3977.6  409.48
    4139  408.46  4289.2  405.87  4524.5  404.86    4622  404.07  4627.3  403.37
    4645     404  4845.4   404.2  4960.4  405.64  4983.4  405.18    4998  404.53
    5020  405.15  5103.9  405.94    5119  406.43  5132.4  405.71  5173.6  406.99
  5309.9  407.51  5352.9  408.43  5404.3  408.17  5412.4  409.91  5417.7  409.42
  5435.7  410.07  5477.2  409.81  5611.9  411.52  5655.9  413.09  5669.6  412.93
#Mann= 3 ,-1 , 0
  3702.8     .05       0  4983.4     .03       0  5103.9     .05       0
#XS Ineff= 1 ,-1
 4122.23 4961.53  407.27
Permanent Ineff=
       F
Bank Sta=4983.4,5020
XS Rating Curve= 0 ,0
Exp/Cntr=0.3,0.1

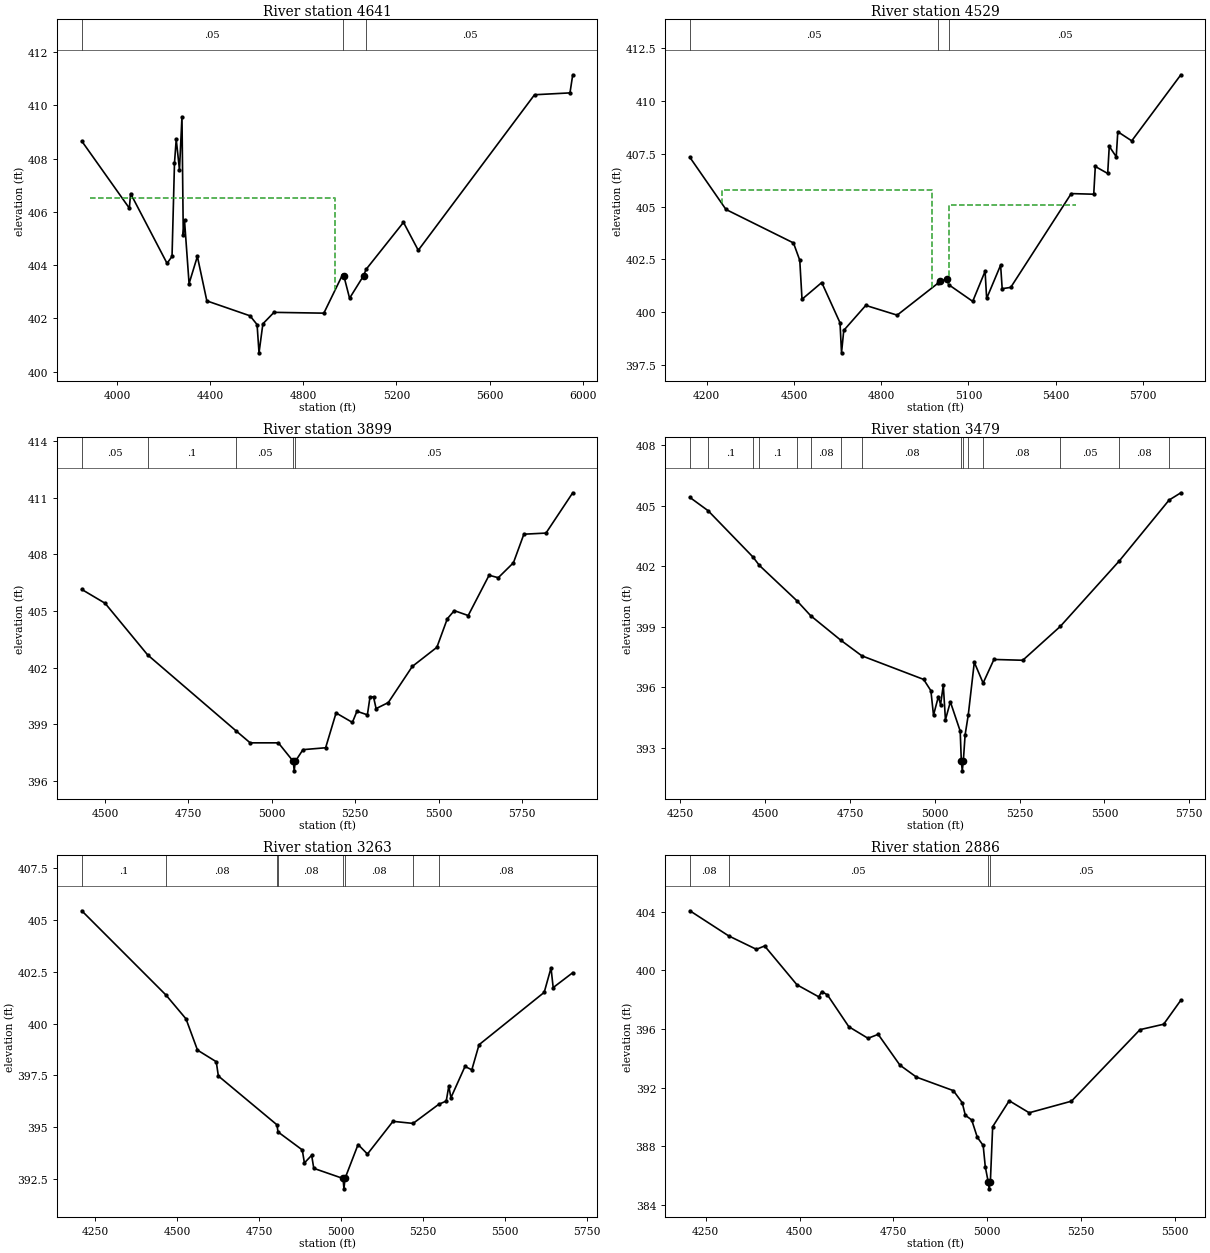
Type RM Length L Ch R = 1 ,4641    ,112,112,112
BEGIN DESCRIPTION:
Mapping XS a907f8ba
END DESCRIPTION:
XS GIS Cut Line= 2
      2297680.54     13445554.83      2295706.55     13444815.24
#Sta/Elev= 30
  3848.9  408.66  4053.2  406.14  4058.5  406.69    4215  404.07  4236.4  404.33
    4247  407.84  4254.4  408.73  4268.4  407.58  4279.1  409.58  4284.7  405.12
    4290  405.68  4309.6  403.31  4345.2  404.33  4385.9  402.66  4571.3   402.1
  4601.6  401.77  4609.9  400.71  4626.5   401.8  4674.2  402.23  4888.3   402.2
  4968.4  403.64  4973.8  403.61  4998.7  402.76  5059.2  403.61  5069.3  403.84
  5230.2  405.61  5293.6  404.56  5792.8   410.4    5945  410.47  5956.9  411.15
#Mann= 3 ,-1 , 0
  3848.9     .05       0  4968.4    .035       0  5069.3     .05       0
#XS Ineff= 1 ,-1
 3884.92 4935.59  406.54
Permanent Ineff=
       F
Bank Sta=4973.8,5059.2
XS Rating Curve= 0 ,0
Exp/Cntr=0.3,0.1

Type RM Length L Ch R = 1 ,4529    ,630,630,630
BEGIN DESCRIPTION:
Mapping XS 9c5cd2cf
END DESCRIPTION:
XS GIS Cut Line= 2
      2297477.37     13445408.98      2295914.89     13444768.37
#Sta/Elev= 30
  4142.1  407.32  4266.2  404.86  4498.3  403.28    4520  402.46  4527.7  400.62
  4595.6  401.41  4658.4  399.51  4663.6  398.09  4671.3  399.15    4747  400.33
    4855  399.87  4995.5  401.38  5002.7  401.48  5026.7  401.57  5032.1  401.31
  5114.8  400.52  5157.4  401.94  5162.8  400.66  5210.8  402.23  5216.2  401.12
  5245.6  401.18  5453.7  405.61  5531.1  405.58  5536.5  406.89  5579.1  406.56
  5584.5  407.84  5608.5  407.35  5613.9  408.53  5661.8   408.1  5830.8  411.22
#Mann= 3 ,-1 , 0
  4142.1     .05       0  4995.5    .035       0  5032.1     .05       0
#XS Ineff= 2 ,-1
 4254.09  4974.8405.7853 5031.78 5470.37 405.066
Permanent Ineff=
       T       T
Bank Sta=5002.7,5026.7
XS Rating Curve= 0 ,0
Exp/Cntr=0.3,0.1

Type RM Length L Ch R = 1 ,3899    ,420,420,420
BEGIN DESCRIPTION:
UNT015 IN SUCR 5.0
END DESCRIPTION:
XS GIS Cut Line= 4
      2297466.99     13445119.55      2297199.74     13445003.74
      2296496.02     13444763.23      2296077.35     13444638.52
#Sta/Elev= 30
  4430.3  406.14  4500.1  405.41  4627.7  402.68  4893.7  398.65  4935.1  398.03
  5019.6  398.03  5064.3  397.05  5067.1  396.55  5070.3  397.05  5093.4  397.67
  5161.3  397.77  5192.6  399.61  5241.5  399.11  5255.2   399.7  5286.5  399.51
  5294.4  400.46  5304.9  400.46  5312.6  399.84  5349.2  400.16  5421.2  402.07
  5494.8  403.08  5526.1  404.59    5547  405.02  5588.7  404.76  5651.3  406.89
  5678.8  406.76  5724.3  407.55  5755.6  409.06  5821.9  409.12  5902.1  411.25
#Mann= 5 ,-1 , 0
  4430.3     .05       0  4627.7      .1       0  4893.7     .05       0
  5064.3    .035       0  5070.3     .05       0
Bank Sta=5064.3,5070.3
XS Rating Curve= 0 ,0
Exp/Cntr=0.3,0.1

Type RM Length L Ch R = 1 ,3479    ,216,216,216
BEGIN DESCRIPTION:
UNT015 IN SUCR 4.0
END DESCRIPTION:
XS GIS Cut Line= 4
      2297471.06     13444996.31      2297075.26     13444634.35
      2296700.26     13444342.69      2296335.66     13444103.09
#Sta/Elev= 30
  4277.8  405.41  4331.6  404.75  4463.6  402.46  4482.7  402.04  4593.3  400.29
  4633.8  399.55    4723  398.33  4784.8  397.56  4967.1  396.39  4988.4  395.83
  4996.1  394.62  5010.5  395.54  5016.9  395.14    5025   396.1  5031.3  394.39
  5045.8  395.28  5074.8  393.83  5078.1  392.36  5080.9  391.86  5084.1  392.36
  5089.3  393.64  5098.6  394.63  5116.4  397.24  5142.4  396.21  5174.3  397.38
  5259.4  397.34  5370.1  399.02  5544.3  402.27  5690.8  405.28  5725.5  405.64
#Mann= 15 ,-1 , 0
  4277.8     .05       0  4331.6      .1       0  4463.6     .05       0
  4482.7      .1       0  4593.3     .05       0  4633.8     .08       0
    4723     .05       0  4784.8     .08       0  5078.1     .07       0
  5084.1     .08       0  5098.6     .05       0  5142.4     .08       0
  5370.1     .05       0  5544.3     .08       0  5690.8     .05       0
Bank Sta=5078.1,5084.1
XS Rating Curve= 0 ,0
Exp/Cntr=0.3,0.1

Type RM Length L Ch R = 1 ,3263    ,377,377,377
BEGIN DESCRIPTION:
UNT015 IN SUCR 3.0
END DESCRIPTION:
XS GIS Cut Line= 2
      2297555.51     13444867.32      2296411.18     13443899.84
#Sta/Elev= 30
  4208.5  405.45  4465.5  401.38  4526.6  400.23  4561.7  398.72  4618.9  398.16
  4625.4  397.47  4804.4  395.11  4807.3  394.77  4881.5   393.9    4888  393.27
  4910.1  393.64  4916.6  393.01  5005.9  392.52  5008.7  392.02  5011.9  392.52
  5051.8  394.16  5080.4   393.7  5158.4  395.28  5219.7  395.18  5297.8   396.1
  5320.9  396.26  5328.7  396.98  5335.2  396.42  5378.1  397.93    5399  397.77
    5421  398.98  5619.9  401.51  5640.7  402.69  5647.3  401.74    5707  402.46
#Mann= 8 ,-1 , 0
  4208.5      .1       0  4465.5     .08       0  4804.4     .05       0
  4807.3     .08       0  5005.9     .07       0  5011.9     .08       0
  5219.7     .05       0  5297.8     .08       0
Bank Sta=5005.9,5011.9
XS Rating Curve= 0 ,0
Exp/Cntr=0.3,0.1

Type RM Length L Ch R = 1 ,2886    ,367,367,367
BEGIN DESCRIPTION:
Mapping XS f060b1fc
END DESCRIPTION:
XS GIS Cut Line= 4
      2297638.84     13444622.51       2297295.1     13444106.91
      2296935.73      13443976.7      2296644.04     13443882.94
#Sta/Elev= 30
  4207.8  404.07  4310.9  402.36    4385  401.44  4406.9  401.67  4493.1  399.02
  4551.1   398.2  4559.2  398.56  4574.3  398.33  4631.3  396.16  4682.4  395.37
  4709.5  395.64  4767.4  393.54  4811.6  392.72  4909.8   391.8  4933.4  390.98
  4941.7  390.12  4958.7   389.8  4973.6  388.62  4989.3  388.06  4994.9  386.61
  5002.5   385.6  5005.3   385.1  5008.5   385.6  5014.6  389.34  5058.7  391.11
  5111.9  390.29  5224.5  391.08  5407.2  395.96  5470.2  396.33  5516.1  397.97
#Mann= 4 ,-1 , 0
  4207.8     .08       0  4310.9     .05       0  5002.5     .03       0
  5008.5     .05       0
Bank Sta=5002.5,5008.5
XS Rating Curve= 0 ,0
Exp/Cntr=0.3,0.1

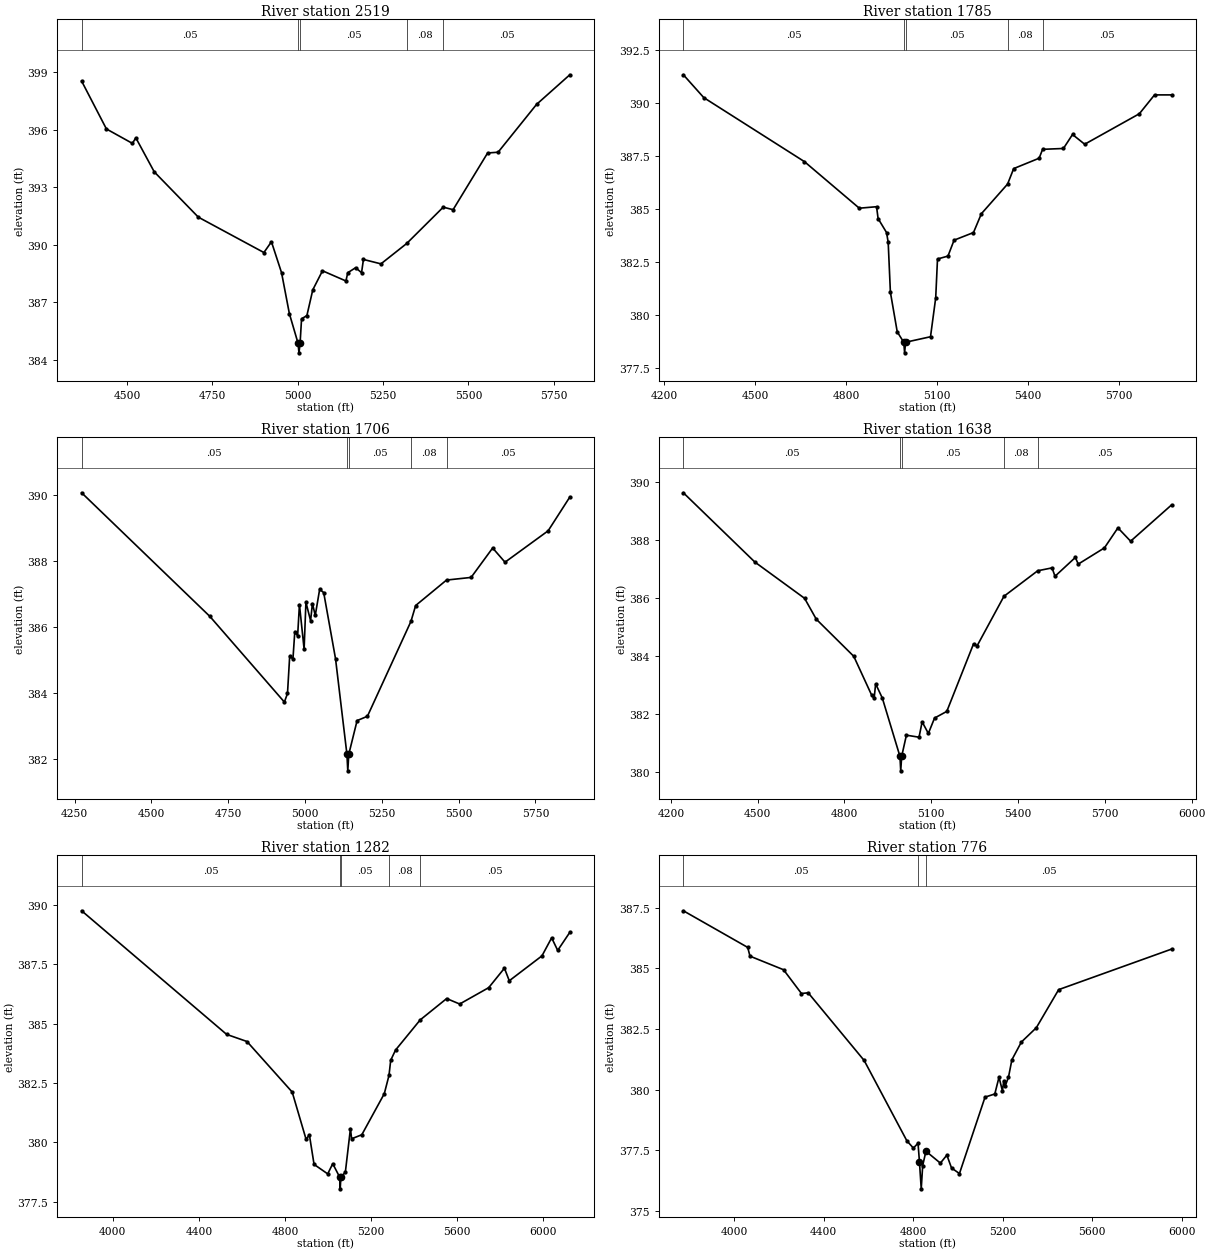
Type RM Length L Ch R = 1 ,2519    ,734,734,734
BEGIN DESCRIPTION:
UNT015 IN SUCR 2.0
END DESCRIPTION:
XS GIS Cut Line= 4
      2297636.25     13444184.25      2297493.71     13443827.89
      2296843.43     13443525.02      2296522.71     13443596.29
#Sta/Elev= 30
  4367.3  398.52  4439.9  396.03    4516  395.28    4526  395.57  4579.9   393.8
  4709.1  391.44  4901.1   389.6  4923.2  390.16  4952.8  388.55  4975.7  386.42
  5001.1  384.88  5003.8  384.38  5007.1  384.88  5011.4  386.15    5027  386.32
  5044.3  387.66  5072.7  388.65  5141.3  388.12  5146.8  388.55  5169.7  388.81
  5187.1  388.55  5192.6  389.24  5243.9  389.01  5319.3  390.07  5426.3  391.96
  5455.2  391.83  5556.3  394.78    5587  394.82  5699.7  397.31    5797  398.85
#Mann= 5 ,-1 , 0
  4367.3     .05       0  5001.1    .035       0  5007.1     .05       0
  5319.3     .08       0  5426.3     .05       0
Bank Sta=5001.1,5007.1
XS Rating Curve= 0 ,0
Exp/Cntr=0.3,0.1

Type RM Length L Ch R = 1 ,1785    ,79,79,79
BEGIN DESCRIPTION:
Mapping XS 657ad7ee
END DESCRIPTION:
XS GIS Cut Line= 5
      2297654.47     13443783.96      2297581.56     13443138.16
       2297545.1     13443044.41      2297461.77     13443013.16
      2296691.79     13443070.39
#Sta/Elev= 30
  4262.3  391.34  4329.8  390.26  4661.9  387.24  4843.1  385.04  4900.1  385.11
  4905.2  384.55  4933.1  383.89  4938.5  383.43  4945.8  381.07  4968.4   379.2
  4989.9  378.71  4992.7  378.21  4995.9  378.71  5078.2  378.97  5095.4  380.81
  5101.3  382.64  5135.9  382.78    5156  383.53  5220.1  383.89  5246.2  384.78
  5332.7  386.18  5352.8  386.91  5436.8   387.4  5448.3  387.82    5517  387.86
  5547.1  388.52  5587.2  388.06  5767.7   389.5  5817.8  390.39  5873.9  390.39
#Mann= 5 ,-1 , 0
  4262.3     .05       0  4989.9     .03       0  4995.9     .05       0
  5332.7     .08       0  5448.3     .05       0
Bank Sta=4989.9,4995.9
XS Rating Curve= 0 ,0
Exp/Cntr=0.3,0.1

Type RM Length L Ch R = 1 ,1706    ,68,68,68
BEGIN DESCRIPTION:
Mapping XS 90fac58d
END DESCRIPTION:
XS GIS Cut Line= 4
      2297716.98     13443679.85      2297618.02     13443007.95
      2297529.48     13442950.66      2296727.42     13443013.16
#Sta/Elev= 30
  4272.9  390.06  4690.4  386.32  4932.9  383.73    4943  383.99  4950.1  385.11
  4960.8  385.04  4966.8  385.86    4976  385.73  4981.9  386.68  4997.1  385.33
    5003  386.75  5018.2  386.19  5024.2  386.71  5033.4  386.35  5047.7  387.14
  5060.9  387.04  5099.4  385.04  5136.5  382.15  5139.3  381.65  5142.5  382.15
  5169.6  383.17  5203.2   383.3  5344.9  386.17  5360.2  386.65  5460.7  387.42
  5540.7   387.5  5610.9  388.39  5651.1  387.96  5791.5  388.91    5862  389.93
#Mann= 5 ,-1 , 0
  4272.9     .05       0  5136.5     .03       0  5142.5     .05       0
  5344.9     .08       0  5460.7     .05       0
Bank Sta=5136.5,5142.5
XS Rating Curve= 0 ,0
Exp/Cntr=0.3,0.1

Type RM Length L Ch R = 1 ,1638    ,356,356,356
BEGIN DESCRIPTION:
Mapping XS a56d
END DESCRIPTION:
XS GIS Cut Line= 4
       2297766.9     13443621.59      2297669.67     13442944.46
      2297433.56     13442854.19      2296687.01     13442930.58
#Sta/Elev= 30
  4243.1  389.63  4490.3  387.24  4662.1  385.99  4702.5  385.27  4832.1  383.99
  4894.4  382.64  4902.6  382.55  4907.7  383.04  4930.8  382.55  4991.7  380.54
  4994.4  380.04  4997.7  380.54    5014  381.27  5057.7   381.2  5068.4  381.73
  5089.9  381.33  5111.3  381.86  5153.6  382.09  5246.1  384.42  5258.3  384.35
  5351.2  386.06  5467.8  386.94  5517.5  387.04  5527.6  386.75    5598   387.4
    5608  387.17  5698.5  387.73  5745.1  388.42    5789  387.96  5930.4  389.21
#Mann= 5 ,-1 , 0
  4243.1     .05       0  4991.7     .03       0  4997.7     .05       0
  5351.2     .08       0  5467.8     .05       0
Bank Sta=4991.7,4997.7
XS Rating Curve= 0 ,0
Exp/Cntr=0.3,0.1

Type RM Length L Ch R = 1 ,1282    ,506,506,506
BEGIN DESCRIPTION:
Mapping XS a56d6e
END DESCRIPTION:
XS GIS Cut Line= 4
       2297833.3      13443634.7      2297847.19     13442641.63
      2297486.07     13442488.85      2296694.41     13442877.74
#Sta/Elev= 30
  3855.5  389.76  4528.9  384.55  4623.4  384.25  4833.4  382.12  4898.2  380.12
  4913.2  380.32    4935  379.07  4998.4  378.67  5021.8   379.1  5053.6  378.54
  5056.4  378.04  5059.6  378.54  5080.3  378.74    5104  380.58  5109.4  380.15
  5156.8  380.32  5261.2  382.05    5283  382.82    5291  383.46  5313.5  383.89
  5427.9  385.16  5550.9  386.06  5611.3  385.83  5746.2  386.52  5819.2  387.34
  5841.7  386.81  5993.5  387.86  6038.5  388.62  6066.5  388.09  6122.8  388.85
#Mann= 5 ,-1 , 0
  3855.5     .05       0  5053.6     .03       0  5059.6     .05       0
    5283     .08       0  5427.9     .05       0
Bank Sta=5053.6,5059.6
XS Rating Curve= 0 ,0
Exp/Cntr=0.3,0.1

Type RM Length L Ch R = 1 ,776     ,407,407,407
BEGIN DESCRIPTION:
Mapping XS a56d6e4e
END DESCRIPTION:
XS GIS Cut Line= 4
      2297930.09     13443274.33       2297916.2     13442395.85
      2297601.97      13441983.7      2296941.59     13442405.58
#Sta/Elev= 30
  3773.5  387.37    4061  385.86    4071   385.5    4221  384.94    4301  383.96
    4331  383.99  4581.1   381.2  4771.8  377.89  4800.9  377.59  4821.7  377.79
    4828  377.03    4836  375.91  4842.5  376.87    4857  377.46  4921.5  376.97
  4950.5   377.3  4971.3  376.77  5006.7  376.54    5121  379.69  5164.6  379.82
  5183.4  380.51  5198.6  379.95  5204.6  380.35    5211  380.15  5225.7  380.51
    5241  381.23  5283.3  381.96  5350.1  382.55  5449.9  384.12    5954  385.79
#Mann= 3 ,-1 , 0
  3773.5     .05       0  4821.7     .03       0    4857     .05       0
Bank Sta=4828,4857
XS Rating Curve= 0 ,0
Exp/Cntr=0.3,0.1

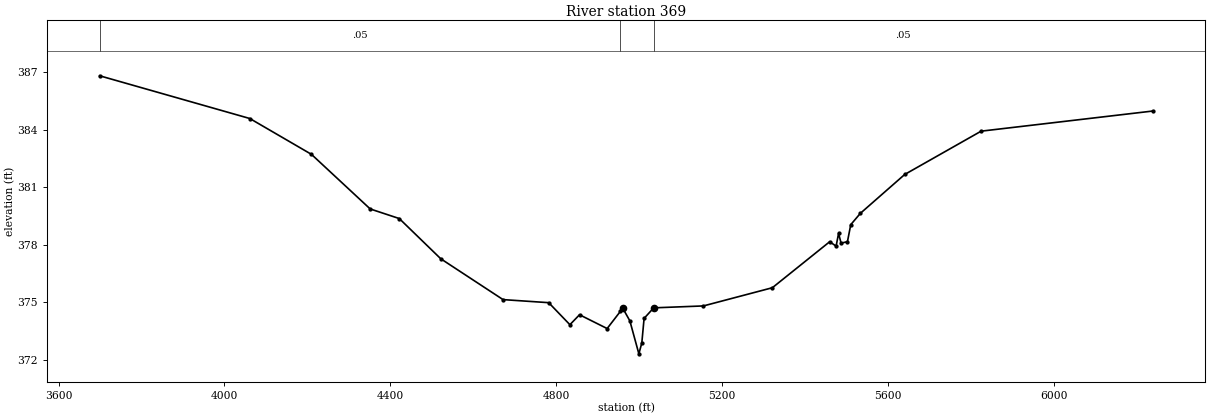
Type RM Length L Ch R = 1 ,369     ,0,0,0
BEGIN DESCRIPTION:
UNT015 IN SUCR 1.0
END DESCRIPTION:
XS GIS Cut Line= 4
      2297999.96     13443148.61      2298048.57     13442051.35
      2297902.74     13441724.96      2296972.44     13442280.37
#Sta/Elev= 30
  3699.1  386.81  4061.2  384.58  4209.8  382.71  4351.5  379.86  4421.6  379.36
  4521.7  377.26  4671.8  375.13  4781.9  374.97    4833  373.82  4856.2  374.34
  4922.8  373.62  4954.5  374.51    4960   374.7  4977.6  374.02  4999.3   372.3
  5006.4  372.87  5011.9  374.15  5035.1   374.7  5154.9   374.8  5321.2  375.75
  5459.4  378.15  5474.9  377.92  5480.8  378.58  5486.9  378.08  5502.2  378.15
  5510.2  379.04  5533.3  379.63  5640.3  381.66  5824.6  383.92  6238.4  384.97
#Mann= 3 ,-1 , 0
  3699.1     .05       0  4954.5     .03       0  5035.1     .05       0
Bank Sta=4960,5035.1
XS Rating Curve= 0 ,0
Exp/Cntr=0.3,0.1

Chan Stop Cuts=-1
Use User Specified Reach Order=0
Composite Channel Slope=5