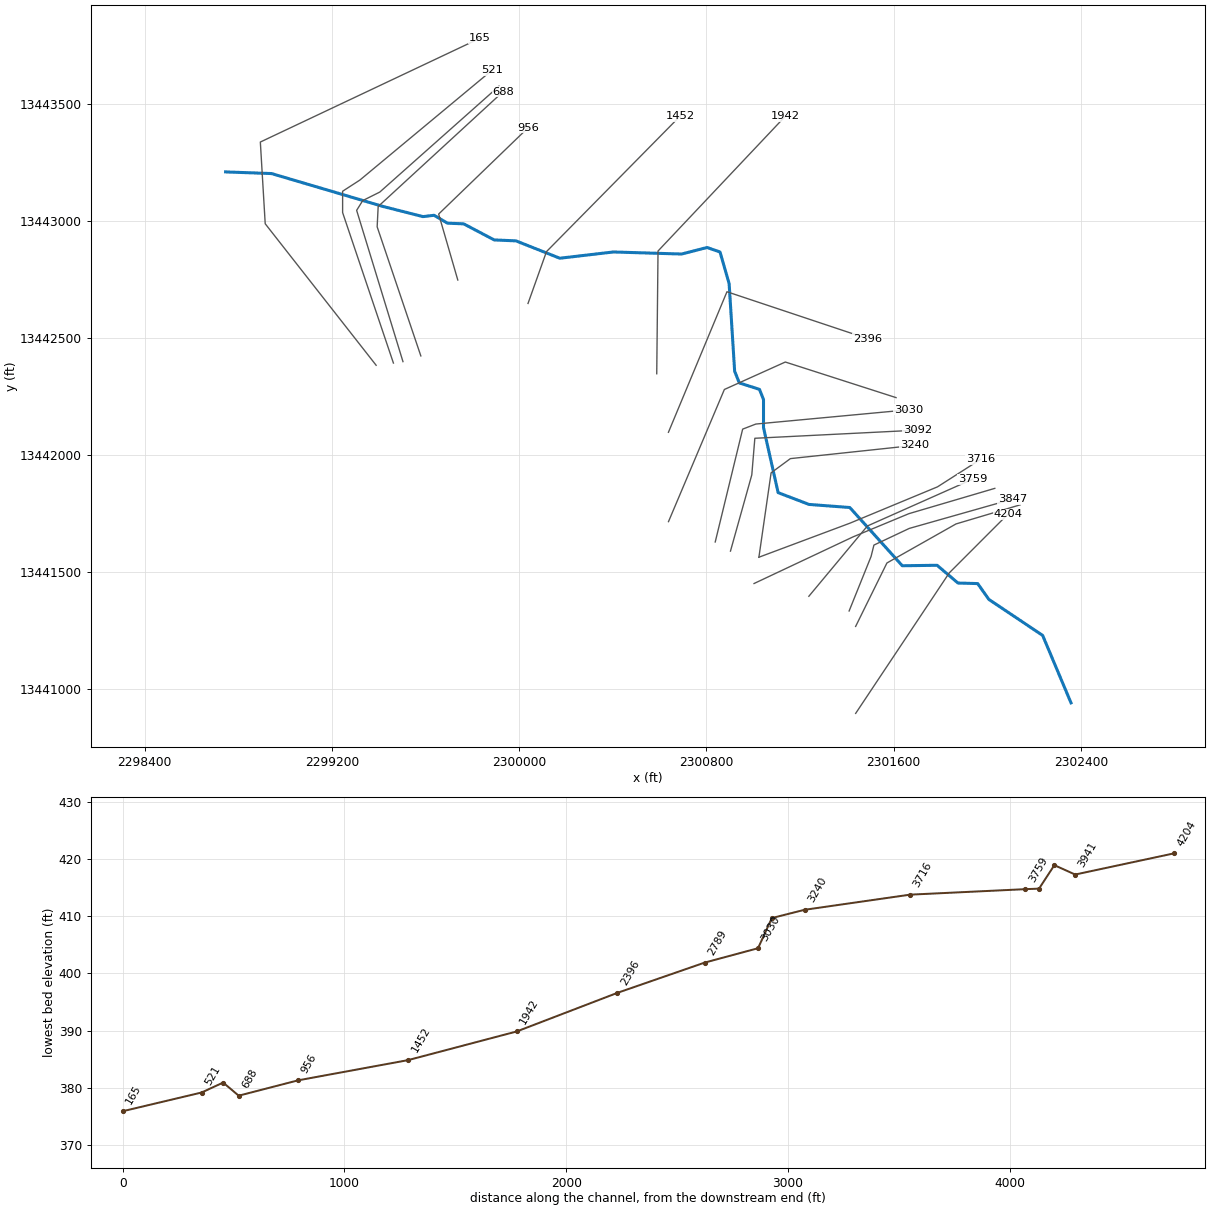
--- UNT016 IN SUCR.prj (project) ---

Proj Title=UNT016 IN SUCR Base Level Engineering
Current Plan=p01
Default Exp/Contr=0.3,0.1
English Units
Geom File=g01
Flow File=f01
Plan File=p01
Y Axis Title=Elevation
X Axis Title(PF)=Main Channel Distance
X Axis Title(XS)=Station
BEGIN DESCRIPTION:
UNT016 IN SUCR
END DESCRIPTION:
DSS Export Rating Curves= 0
DSS Export Rating Curve Sorted= 0
DSS Export Volume Flow Curves= 0
DXF OffsetX= 0
DXF OffsetY= 0
DXF ScaleX= 1
DXF ScaleY= 10

--- UNT016 IN SUCR.p01 (plan) ---

Plan Title=Multiple Run
Short Identifier=Multiple
Geom File=g01
Flow File=f01
Subcritical Flow
K Sum by GR= 0
Std Step Tol= 0.01
Critical Tol= 0.01
Num of Std Step Trials= 20
Max Error Tol= 0.3
Flow Tol Ratio= 0.001
Split Flow NTrial= 30
Split Flow Tol= 0.02
Split Flow Ratio= 0.02
Log Output Level= 0
Friction Slope Method= 1
Unsteady Friction Slope Method= 2
Unsteady Bridges Friction Slope Method= 1
Parabolic Critical Depth
Global Vel Dist=  1 , 1 , 1
Global Log Level= 0
CheckData=True
Encroach Param= -1, 0, 0, 0
BEGIN DESCRIPTION:
Multiple Run
END DESCRIPTION:

--- UNT016 IN SUCR.f01 (steady flow) ---

Flow Title=Multiple
Program Version=4.10
Number of Profiles= 7
Profile Names=10-year,25-year,50-year,1pct_min,100-year,1pct_plu,500-year
River Rch & RM=UNT016 IN SUCR,Reach-1         ,4204
     168     219     259     225     305     412     421
River Rch & RM=UNT016 IN SUCR,Reach-1         ,3240
     209     277     331     291     393     532     554
River Rch & RM=UNT016 IN SUCR,Reach-1         ,1942
     489     687     852     774    1047    1415    1582
Boundary for River Rch & Prof#=UNT016 IN SUCR,Reach-1         , 1
Up Type= 0
Dn Type= 3
Dn Slope=0.0093
Boundary for River Rch & Prof#=UNT016 IN SUCR,Reach-1         , 2
Up Type= 0
Dn Type= 3
Dn Slope=0.0093
Boundary for River Rch & Prof#=UNT016 IN SUCR,Reach-1         , 3
Up Type= 0
Dn Type= 3
Dn Slope=0.0093
Boundary for River Rch & Prof#=UNT016 IN SUCR,Reach-1         , 4
Up Type= 0
Dn Type= 3
Dn Slope=0.0093
Boundary for River Rch & Prof#=UNT016 IN SUCR,Reach-1         , 5
Up Type= 0
Dn Type= 3
Dn Slope=0.0093
Boundary for River Rch & Prof#=UNT016 IN SUCR,Reach-1         , 6
Up Type= 0
Dn Type= 3
Dn Slope=0.0093
Boundary for River Rch & Prof#=UNT016 IN SUCR,Reach-1         , 7
Up Type= 0
Dn Type= 3
Dn Slope=0.0093
DSS Import GetInterval= 0
DSS Import GetPeak= 0
DSS Import FillOption= 0

--- UNT016 IN SUCR.g01 (geometry) ---

Geom Title=Existing Conditions
Program Version=4.10

River Reach=UNT016 IN SUCR  ,Reach-1
Reach XY= 30
      2302357.72     13440941.85      2302236.54     13441229.76
       2302006.9     13441383.16      2301958.99     13441450.95
      2301874.71      13441453.3      2301785.53     13441529.13
        2301637.     13441527.05      2301412.59     13441775.74
      2301238.36     13441788.89      2301106.42     13441839.24
      2301043.92     13442117.02      2301043.92     13442236.81
      2301026.56     13442280.21      2300940.51     13442307.65
      2300920.56     13442358.02      2300897.04     13442731.54
      2300858.05     13442866.65      2300802.75     13442885.85
      2300694.07     13442857.87      2300402.81     13442866.73
      2300173.42     13442839.98      2299986.39     13442914.13
      2299893.28      13442918.1      2299762.82      13442986.8
      2299693.31     13442989.61      2299636.65     13443023.32
      2299588.96     13443017.68       2299419.5     13443060.68
      2298941.85     13443201.48      2298745.56     13443208.48

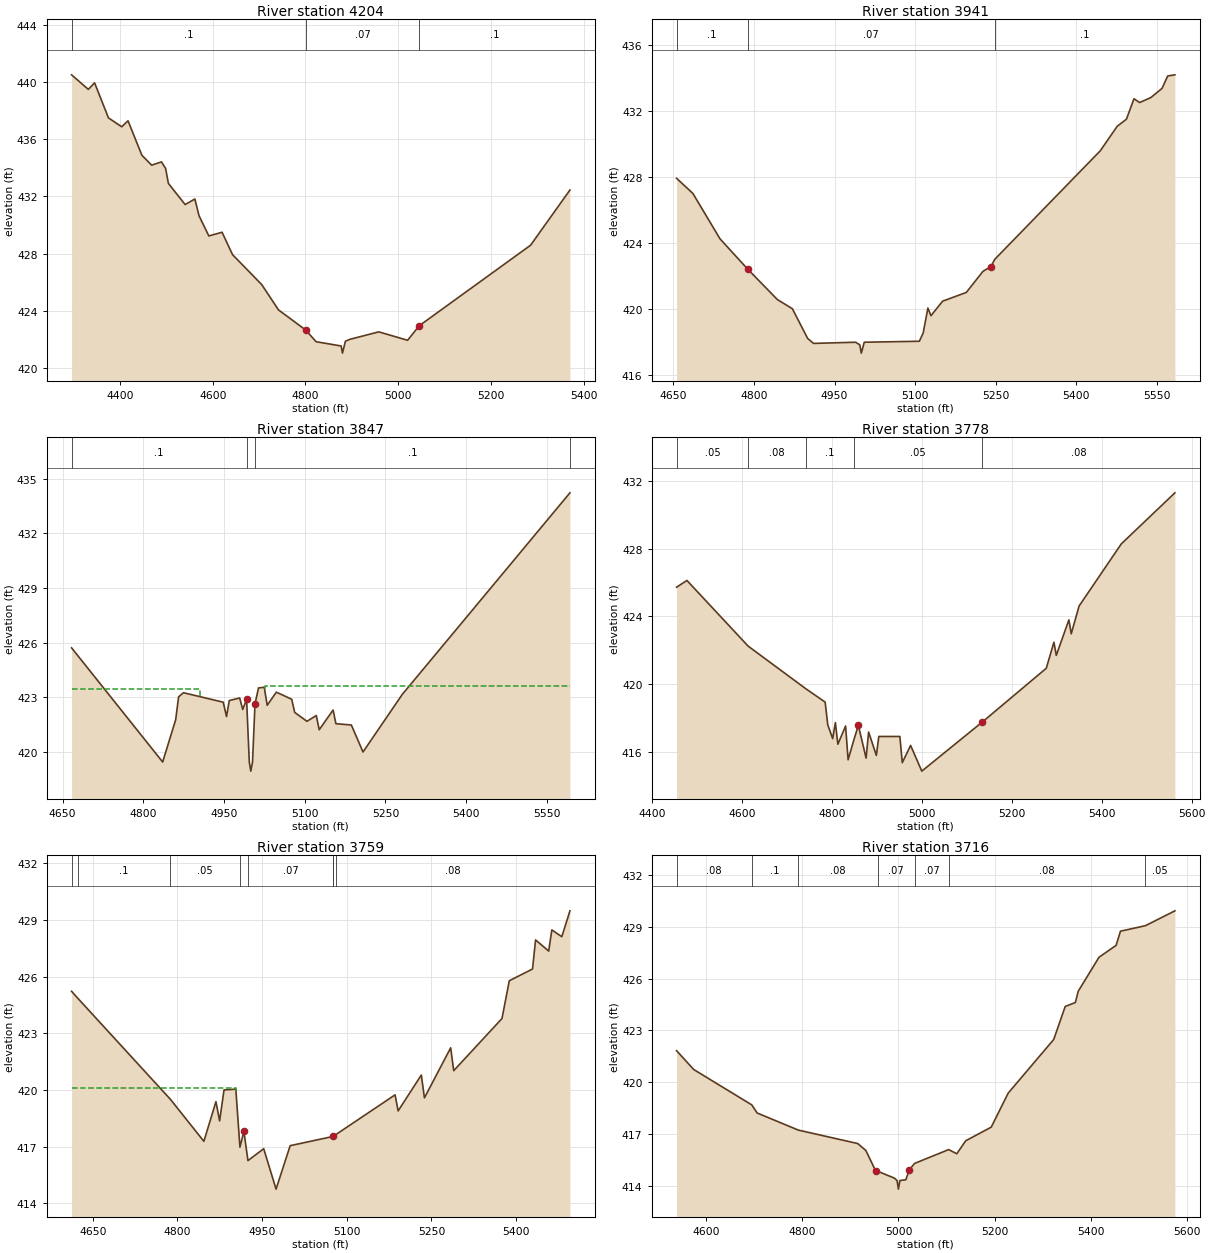
Type RM Length L Ch R = 1 ,4204    ,445,445,445
BEGIN DESCRIPTION:
UNT016 IN SUCR 9.0
END DESCRIPTION:
XS GIS Cut Line= 3
      2301437.71     13440896.84      2301837.72     13441496.85
      2302087.73     13441746.87
#Sta/Elev= 30
  4295.7  440.52  4331.8   439.5  4345.3  439.96  4375.3   437.5  4403.9  436.88
  4417.4   437.3  4447.4  434.88  4468.5  434.19  4489.5  434.42  4498.5  433.96
  4504.5  432.91  4540.6  431.43  4561.6  431.82  4570.6  430.64  4591.7  429.23
  4620.2  429.49  4642.8  427.92  4705.8  425.82  4741.9  424.05  4800.5  422.64
    4823  421.82  4877.1  421.52  4879.9  421.02  4886.1  421.85  4895.1  421.98
  4958.2  422.51  5020.4  421.92  5045.1  422.93  5285.5  428.58  5370.4  432.45
#Mann= 3 , 0 , 0
  4295.7      .1       0  4800.5     .07       0  5045.1      .1       0
Bank Sta=4800.5,5045.1
XS Rating Curve= 0 ,0
Exp/Cntr=0.3,0.1

Type RM Length L Ch R = 1 ,3941    ,94,94,94
BEGIN DESCRIPTION:
UNT016 IN SUCR 8.0
END DESCRIPTION:
XS GIS Cut Line= 4
      2301437.56      13441268.1      2301571.22      13441538.9
      2301866.36     13441705.57      2302140.64     13441787.16
#Sta/Elev= 30
  4656.1  427.92  4686.5     427  4736.9  424.25  4788.5  422.41  4843.6  420.57
  4871.6  420.01    4900  418.21    4911  417.91  4989.3  417.98    4997  417.82
  4999.8  417.32  5005.3  417.98  5107.8  418.04  5114.9  418.54  5123.7  420.05
  5129.4  419.59  5151.1  420.47  5195.2     421  5226.2  422.28  5241.2  422.57
  5247.9     423  5444.5  429.59  5475.8  431.07    5493   431.5  5507.1  432.74
  5517.6  432.51  5538.4  432.81  5559.3  433.37  5569.8  434.12  5583.2  434.19
#Mann= 3 ,-1 , 0
  4656.1      .1       0  4788.5     .07       0  5247.9      .1       0
Bank Sta=4788.5,5241.2
XS Rating Curve= 0 ,0
Exp/Cntr=0.3,0.1

Type RM Length L Ch R = 1 ,3847    ,69,69,69
BEGIN DESCRIPTION:
UNT016 IN SUCR 8.3
END DESCRIPTION:
XS GIS Cut Line= 5
      2301409.75     13441334.02      2301503.51     13441566.68
      2301515.66     13441615.29      2301666.71     13441686.47
      2302107.71     13441811.48
#Sta/Elev= 30
  4666.7  425.72    4836  419.46  4860.2  421.78  4865.6  423.03  4874.6  423.26
  4948.6  422.74  4954.7  421.95  4959.8  422.83  4979.2  422.97  4984.8  422.34
    4992   422.9    4997  419.46  4999.8  418.96    5003  419.46  5007.6  422.64
  5014.1  423.52  5024.8  423.56  5030.3  422.57  5047.3  423.29  5075.9   422.9
  5081.4  422.18  5104.2  421.69  5121.5  422.01    5127  421.23  5152.8  422.31
    5158  421.56  5186.7  421.49  5208.4  420.01  5281.2  423.16    5593  434.22
#Mann= 4 ,-1 , 0
  4666.7      .1       0    4992     .07       0  5007.6      .1       0
    5593     .05       0
#XS Ineff= 2 , 0
         4904.97  423.44 5025.39          423.61
Permanent Ineff=
       T       T
Bank Sta=4992,5007.6
XS Rating Curve= 0 ,0
Exp/Cntr=0.3,0.1

Type RM Length L Ch R = 1 ,3778    ,62,62,62
BEGIN DESCRIPTION:
UNT016 IN SUCR 8.1
END DESCRIPTION:
XS GIS Cut Line= 4
      2301003.49     13441451.22      2301426.69     13441650.45
      2301664.97     13441749.41      2302032.13     13441857.47
#Sta/Elev= 30
  4454.3  425.72  4477.4  426.12  4613.5  422.24  4742.3  419.71  4784.8  418.93
  4790.6  417.59  4801.6  416.77  4807.6  417.72  4813.1  416.44  4830.3  417.52
  4835.9  415.52  4848.7   416.7  4858.7  417.55  4875.9  415.62  4881.5  417.16
  4898.7  415.78  4904.2   416.9    4951   416.9  4956.4  415.35  4974.9  416.37
  4999.8  414.85  5134.3  417.75  5276.7  420.93  5293.7  422.47  5298.9  421.69
    5327  423.79  5332.2  422.97  5349.7  424.61  5443.5  428.28  5562.8   431.3
#Mann= 5 ,-1 , 0
  4454.3     .05       0  4613.5     .08       0  4742.3      .1       0
  4848.7     .05       0  5134.3     .08       0
Bank Sta=4858.7,5134.3
XS Rating Curve= 0 ,0
Exp/Cntr=0.3,0.1

Type RM Length L Ch R = 1 ,3759    ,519,519,519
BEGIN DESCRIPTION:
UNT016 IN SUCR 8.0
END DESCRIPTION:
XS GIS Cut Line= 3
      2301237.69     13441396.82      2301487.72     13441696.85
      2301937.72     13441896.85
#Sta/Elev= 30
  4612.4  425.23  4623.8  424.85  4787.6  419.51  4846.8  417.29  4868.2  419.39
  4874.7  418.37  4882.5  420.01  4903.4  420.05  4910.7  416.98  4917.7  417.82
  4924.9  416.27  4952.8   416.9  4974.7  414.76  4999.7  417.06    5076  417.55
  5080.8  417.65  5185.6  419.75    5191   418.9  5232.1   420.8  5237.6  419.59
  5284.1  422.24  5289.5  421.03    5375  423.79    5388  425.79  5429.1  426.41
  5434.5  427.95  5457.8  427.36  5463.3  428.48    5481  428.12  5495.4  429.49
#Mann= 8 ,-1 , 0
  4612.4     .05       0  4623.8      .1       0  4787.6     .05       0
  4910.7     .08       0  4924.9     .07       0    5076     .08       0
    5076      .1       0  5080.8     .08       0
#XS Ineff= 2 , 0
         4903.67  420.13
Permanent Ineff=
       T       T
Bank Sta=4917.7,5076
XS Rating Curve= 0 ,0
Exp/Cntr=0.3,0.1

Type RM Length L Ch R = 1 ,3716    ,476,476,476
BEGIN DESCRIPTION:
UNT016 IN SUCR 8.2
END DESCRIPTION:
XS GIS Cut Line= 4
      2301024.25      13441563.5      2301413.67     13441709.04
      2301787.37     13441863.99      2301970.97     13441981.18
#Sta/Elev= 30
  4537.7  421.82  4573.4  420.73  4694.4  418.68  4705.6  418.21  4791.3  417.22
  4915.1  416.44    4932  416.04  4952.9  414.83  4957.1  414.83  4991.3  414.44
    4997   414.3  4999.8   413.8    5003   414.3  5015.2  414.34  5022.8  414.93
  5033.6  415.29  5104.5  416.09  5121.5  415.85    5140   416.6  5193.2  417.39
  5228.5  419.36  5323.4  422.47  5347.3  424.38  5368.5  424.61  5374.4  425.26
  5417.7  427.23  5453.3  427.92  5462.4  428.74  5514.5  429.06  5575.8  429.92
#Mann= 7 ,-1 , 0
  4537.7     .08       0  4694.4      .1       0  4791.3     .08       0
  4957.1     .07       0  5033.6     .07       0  5104.5     .08       0
  5514.5     .05       0
Bank Sta=4952.9,5022.8
XS Rating Curve= 0 ,0
Exp/Cntr=0.3,0.1

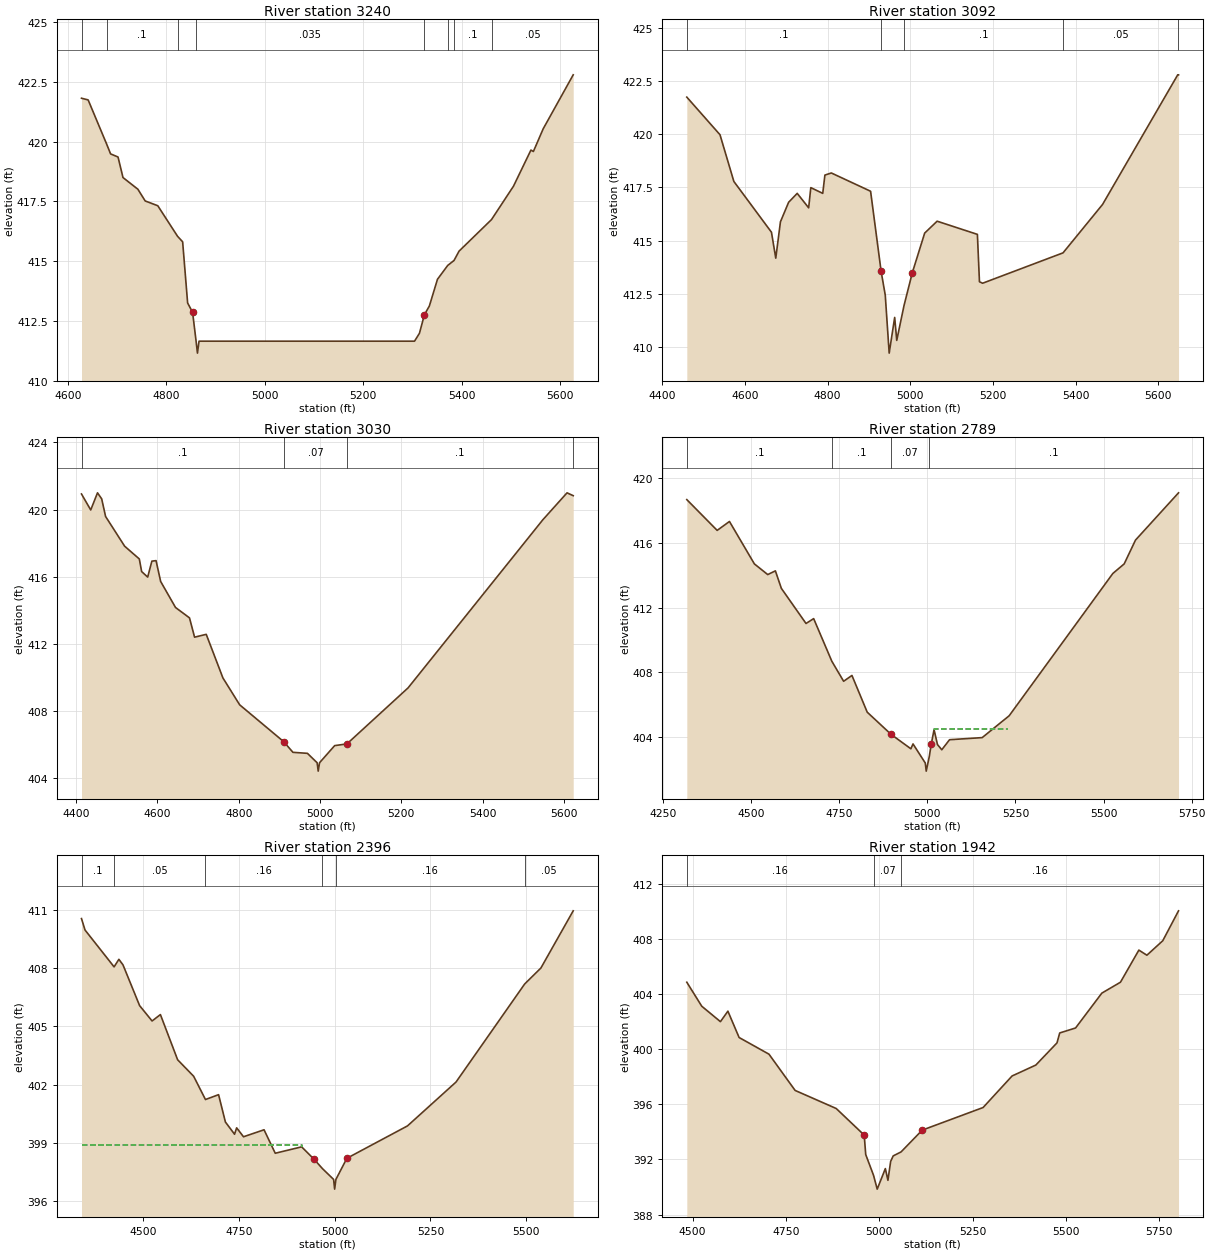
Type RM Length L Ch R = 1 ,3240    ,148,148,148
BEGIN DESCRIPTION:
UNT016 IN SUCR 7.0
END DESCRIPTION:
XS GIS Cut Line= 4
      2301024.26     13441563.46      2301076.35     13441923.75
      2301158.82     13441984.51      2301688.35     13442040.94
#Sta/Elev= 30
  4627.6  421.82  4641.1  421.75  4678.9  419.89  4686.7  419.49  4701.8  419.36
  4711.9   418.5  4742.2  418.01    4757  417.52  4782.6  417.32  4822.8  416.04
  4833.1  415.81  4843.2  413.25  4853.3  412.86  4860.4  411.65  4863.2  411.15
  4866.4  411.65  5304.2  411.65  5314.2  411.98  5324.3  412.76  5334.3  413.12
  5350.8  414.24  5371.6  414.82  5384.5  415.03  5394.7  415.42  5460.6  416.74
  5505.3  418.14  5540.7  419.65  5545.7  419.59  5565.6  420.54  5626.6   422.8
#Mann= 8 ,-1 , 0
  4627.6     .08       0  4678.9      .1       0  4822.8     .07       0
  4860.4    .035       0  5324.3      .1       0  5371.6     .07       0
  5384.5      .1       0  5460.6     .05       0
Bank Sta=4853.3,5324.3
XS Rating Curve= 0 ,0
Exp/Cntr=0.3,0.1

Type RM Length L Ch R = 1 ,3092    ,62,62,62
BEGIN DESCRIPTION:
Mapping XS 388e3c1b
END DESCRIPTION:
XS GIS Cut Line= 4
      2300902.75     13441589.57      2300993.89     13441915.07
      2301006.91     13442071.32      2301701.34     13442106.04
#Sta/Elev= 30
  4459.1  421.75  4539.4  419.98    4573  417.78    4664  415.39  4674.4  414.17
  4685.7  415.88  4705.5   416.8  4726.3  417.22    4754  416.54  4759.2  417.49
  4788.1  417.22  4793.3  418.08  4808.9  418.18  4903.9  417.32  4929.4  413.55
  4939.4  412.43  4948.9   409.7  4962.2  411.38  4967.2   410.3  4984.8  411.94
  5004.8  413.48  5034.8  415.35  5064.9  415.91  5162.4  415.29  5167.4  413.06
    5175  412.99  5369.7  414.42  5465.4   416.7  5647.3   422.8  5649.2   422.8
#Mann= 5 ,-1 , 0
  4459.1      .1       0  4929.4     .07       0  4984.8      .1       0
  5369.7     .05       0  5647.3      .1       0
Bank Sta=4929.4,5004.8
XS Rating Curve= 0 ,0
Exp/Cntr=0.3,0.1

Type RM Length L Ch R = 1 ,3030    ,241,241,241
BEGIN DESCRIPTION:
Mapping XS 5f428bd4
END DESCRIPTION:
XS GIS Cut Line= 4
      2300837.63     13441628.58      2300954.82     13442110.38
      2301011.25     13442132.08      2301662.31     13442192.85
#Sta/Elev= 30
    4413  420.93  4435.7  419.98  4452.4     421  4462.7  420.64  4472.3  419.59
  4519.2  417.82  4555.3  417.06    4561  416.31  4575.9  415.98  4586.2  416.93
  4596.5  416.96  4607.8  415.72  4644.4  414.17  4678.8  413.55  4691.3   412.4
    4720  412.57  4761.1  409.97  4802.3  408.37  4910.9  406.17  4933.4  405.54
    4969  405.48  4992.9  404.92  4995.6  404.42  4998.9  404.92  5036.1  405.94
  5066.2  406.04  5216.8  409.38  5548.3  419.39    5608     421  5623.2  420.83
#Mann= 4 ,-1 , 0
    4413      .1       0  4910.9     .07       0  5066.2      .1       0
  5623.2     .05       0
Bank Sta=4910.9,5066.2
XS Rating Curve= 0 ,0
Exp/Cntr=0.3,0.1

Type RM Length L Ch R = 1 ,2789    ,393,393,393
BEGIN DESCRIPTION:
UNT016 IN SUCR 6.0
END DESCRIPTION:
XS GIS Cut Line= 4
      2300637.98     13441715.42       2300876.7     13442279.65
      2301137.12     13442396.84       2301610.2     13442244.93
#Sta/Elev= 30
  4317.7  418.67  4403.8  416.77  4438.7  417.32  4509.4   414.7  4547.3  414.04
    4569  414.27  4585.9  413.19  4655.9  411.02  4677.6  411.32  4729.1  408.69
  4762.6  407.45  4786.2  407.81  4829.6  405.54  4897.3  404.17  4953.4  403.28
  4959.5  403.58  4994.3   402.4    4997   401.9  5005.8  402.82  5011.3  403.58
  5019.2  404.46  5028.9  403.54  5041.1  403.22  5063.1  403.84  5155.7  403.97
  5232.3  405.32  5526.5  414.11  5558.6   414.7  5590.7  416.17  5712.8  419.09
#Mann= 4 ,-1 , 0
  4317.7      .1       0  4729.1      .1       0  4897.3     .07       0
  5005.8      .1       0
#XS Ineff= 1 ,-1
 5018.85 5228.27  404.49
Permanent Ineff=
       T
Bank Sta=4897.3,5011.3
XS Rating Curve= 0 ,0
Exp/Cntr=0.3,0.1

Type RM Length L Ch R = 1 ,2396    ,454,454,454
BEGIN DESCRIPTION:
UNT016 IN SUCR 5.0
END DESCRIPTION:
XS GIS Cut Line= 3
      2300637.74      13442096.9      2300887.72     13442696.85
      2301487.71     13442496.86
#Sta/Elev= 30
    4340  410.56  4349.2  409.97    4425  408.07  4437.5  408.46  4448.3  408.17
  4491.6  406.07  4524.1  405.28  4545.8  405.61  4590.7  403.28  4632.5  402.43
  4663.3  401.23  4697.5  401.48  4715.3  400.07  4739.2  399.44  4744.6  399.77
  4762.5  399.31  4816.1  399.67  4845.3  398.46  4914.1  398.79  4946.1  398.16
  4968.3  397.67  4997.5  397.11  5000.2  396.61  5003.5  397.11  5032.1   398.2
  5190.2  399.87  5316.7  402.13  5495.9  407.19  5538.1  408.01  5622.4  410.96
#Mann= 6 ,-1 , 0
    4340      .1       0    4425     .05       0  4663.3     .16       0
  4968.3     .07       0  5003.5     .16       0  5495.9     .05       0
#XS Ineff= 2 , 0
       0 4914.14  398.89               0
Permanent Ineff=
       T       F
Bank Sta=4946.1,5032.1
XS Rating Curve= 0 ,0
Exp/Cntr=0.3,0.1

Type RM Length L Ch R = 1 ,1942    ,490,490,490
BEGIN DESCRIPTION:
UNT016 IN SUCR 4.0
END DESCRIPTION:
XS GIS Cut Line= 3
      2300587.72     13442346.86      2300593.24     13442870.82
       2301137.7     13443446.83
#Sta/Elev= 30
  4484.6  404.86  4524.6  403.12  4574.6     402  4594.6  402.76  4624.6  400.85
  4704.6  399.64  4774.6  397.01  4884.6   395.7  4959.6  393.77 4963.64  392.36
  4984.6  390.85  4994.4  389.85  5016.2  391.34  5023.1  390.49  5030.4  391.86
  5037.2  392.26  5058.3  392.55  5114.9  394.13  5277.9  395.77  5355.6  398.06
  5419.1  398.85  5475.8  400.46  5483.1  401.18  5525.5  401.54  5595.9  404.07
  5645.7  404.86    5695  407.19  5716.5  406.82    5759  407.87  5801.2  410.04
#Mann= 3 ,-1 , 0
  4484.6     .16       0  4984.6     .07       0  5058.3     .16       0
Bank Sta=4959.6,5114.9
XS Rating Curve= 0 ,0
Exp/Cntr=0.3,0.1

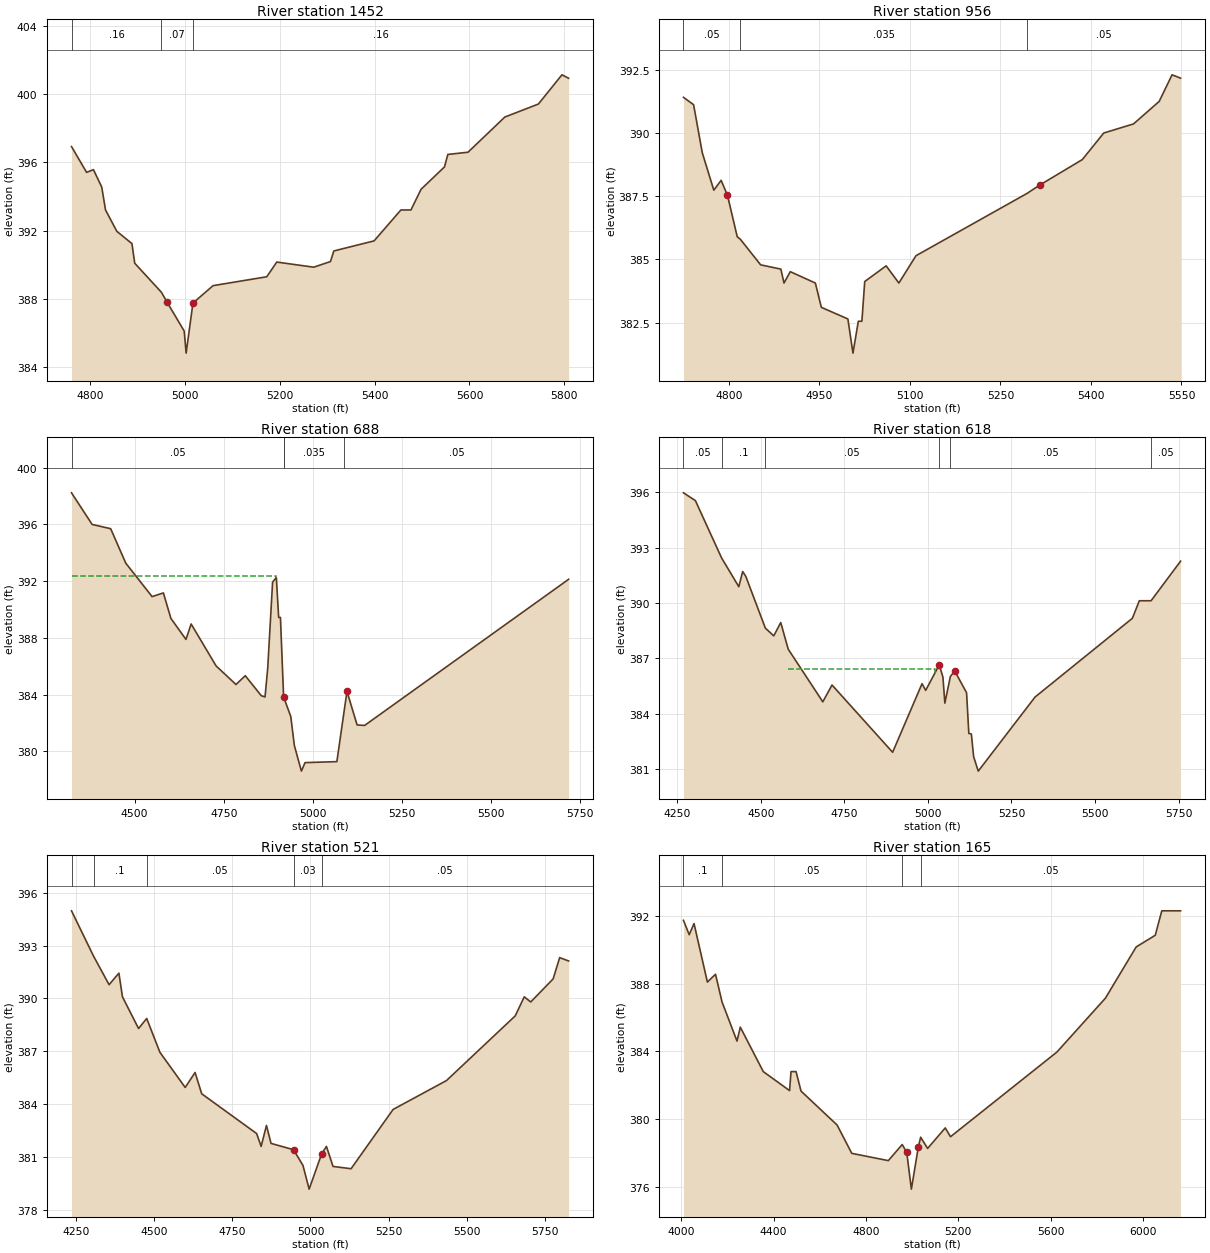
Type RM Length L Ch R = 1 ,1452    ,496,496,496
BEGIN DESCRIPTION:
UNT016 IN SUCR 3.0
END DESCRIPTION:
XS GIS Cut Line= 3
      2300037.73     13442646.87      2300116.67     13442868.21
      2300687.74     13443446.87
#Sta/Elev= 30
  4761.1  396.92  4792.9  395.41  4807.3  395.57  4824.8  394.55  4832.8  393.21
  4856.6  391.96  4888.5  391.24  4894.4  390.09  4950.7  388.39  4962.8   387.8
  4998.7  386.12  5002.7  384.83  5017.1  387.76  5059.5  388.78  5172.7   389.3
  5193.8  390.16  5271.7  389.86    5307  390.19  5314.1  390.81    5399   391.4
  5455.5  393.21  5476.7  393.21    5498  394.42  5547.4  395.73  5554.5  396.46
    5597  396.59  5674.7  398.65  5745.4  399.41    5795  401.12  5809.1  400.92
#Mann= 3 ,-1 , 0
  4761.1     .16       0  4950.7     .07       0  5017.1     .16       0
Bank Sta=4962.8,5017.1
XS Rating Curve= 0 ,0
Exp/Cntr=0.3,0.1

Type RM Length L Ch R = 1 ,956     ,268,268,268
BEGIN DESCRIPTION:
UNT016 IN SUCR 2.0
END DESCRIPTION:
XS GIS Cut Line= 3
      2299737.71     13442746.88      2299655.97      13443028.6
      2300037.75     13443396.88
#Sta/Elev= 30
  4724.7   391.4  4741.5  391.11  4755.9  389.21    4775  387.73  4787.1  388.12
  4797.6  387.53  4813.8  385.89    4819  385.79  4852.6  384.78  4886.1  384.61
  4891.3  384.06  4901.7  384.51  4943.3  384.06  4953.2   383.1  4997.2  382.64
  5005.6  381.29  5014.5  382.55  5020.4  382.55  5025.1  384.12  5060.6  384.74
  5081.7  384.06    5110  385.14  5293.9   387.6    5315  387.93  5385.7  388.94
  5421.2  389.99  5470.6  390.35  5513.1  391.24  5534.4  392.29  5548.5  392.16
#Mann= 3 ,-1 , 0
  4724.7     .05       0    4819    .035       0  5293.9     .05       0
Bank Sta=4797.6,5315
XS Rating Curve= 0 ,0
Exp/Cntr=0.3,0.1

Type RM Length L Ch R = 1 ,688     ,70,70,70
BEGIN DESCRIPTION:
Mapping XS 9448e3f7
END DESCRIPTION:
XS GIS Cut Line= 4
      2299579.83     13442422.87      2299393.19      13442974.1
      2299397.53      13443060.9      2299931.37     13443551.34
#Sta/Elev= 30
  4323.2  398.23    4381     396    4433   395.7  4475.3  393.27  4549.1  390.91
  4580.8  391.17  4601.9  389.37  4644.1  387.89  4658.6  388.98  4728.6  386.02
  4784.3  384.71  4810.4  385.33  4855.3  383.92  4865.8  383.83  4873.3  385.86
    4887  391.93  4897.5  392.26    4904  389.44    4909  389.44  4917.9  383.83
    4938  382.45    4948  380.41  4967.7   378.6    4978   379.2  5067.2  379.27
  5088.2  382.94  5095.6  384.22  5123.9  381.86  5144.9  381.82    5717  392.13
#Mann= 4 ,-1 , 0
  4323.2     .05       0  4917.9     .05       0  4917.9    .035       0
  5088.2     .05       0
#XS Ineff= 2 , 0
       0 4896.36  392.37               0
Permanent Ineff=
       T       T
Bank Sta=4917.9,5095.6
XS Rating Curve= 0 ,0
Exp/Cntr=0.3,0.1

Type RM Length L Ch R = 1 ,618     ,97,97,97
BEGIN DESCRIPTION:
Mapping XS b5442c11
END DESCRIPTION:
XS GIS Cut Line= 5
      2299503.45     13442398.53      2299305.52     13443044.41
      2299331.56     13443086.08      2299404.48     13443122.53
      2299913.84     13443574.72
#Sta/Elev= 30
  4268.7  395.96  4304.4  395.54  4382.7  392.44  4434.3  390.88  4445.9   391.7
  4455.2  391.44  4513.7  388.64  4538.9  388.22  4559.8  388.94  4582.1   387.5
  4685.6  384.65  4713.2  385.56  4894.5  381.92  4982.5  385.63  4993.4  385.27
    5034  386.65    5045  385.99  5050.8  384.58  5067.3  386.02  5080.4  386.32
  5115.8  385.14  5122.5  382.94  5130.1  382.91  5136.8  381.69  5150.7   380.9
  5320.7  384.91  5611.8  389.17  5632.7  390.12  5667.8  390.12    5756  392.26
#Mann= 6 ,-1 , 0
  4268.7     .05       0  4382.7      .1       0  4513.7     .05       0
    5034    .035       0  5067.3     .05       0  5667.8     .05       0
#XS Ineff= 2 ,-1
 4581.15 5020.94  386.43 5081.68 5469.11  386.18
Permanent Ineff=
       T       T
Bank Sta=5034,5080.4
XS Rating Curve= 0 ,0
Exp/Cntr=0.3,0.1

Type RM Length L Ch R = 1 ,521     ,356,356,356
BEGIN DESCRIPTION:
Mapping XS 717481fb
END DESCRIPTION:
XS GIS Cut Line= 5
      2299462.64     13442392.49      2299245.62     13443034.86
      2299245.62     13443126.01      2299319.41     13443173.75
      2299882.79     13443641.79
#Sta/Elev= 30
    4236  394.98  4306.3  392.41  4356.1  390.78  4387.5  391.44  4398.9  390.09
  4450.4  388.29  4476.4  388.86  4518.6  386.94  4599.5  384.94  4631.1  385.79
  4652.3  384.58  4827.9  382.32  4842.3  381.59  4859.4  382.78  4873.9  381.76
    4946   381.4    4976  380.51  4995.8  379.16  5035.9  381.17  5051.1  381.59
  5072.2  380.45  5129.9  380.32  5264.3  383.69  5434.9  385.33  5654.9  389.01
  5683.6  390.09  5704.4   389.8    5776  391.11  5796.9  392.32  5825.5  392.13
#Mann= 5 ,-1 , 0
    4236     .05       0  4306.3      .1       0  4476.4     .05       0
    4946     .03       0  5035.9     .05       0
Bank Sta=4946,5035.9
XS Rating Curve= 0 ,0
Exp/Cntr=0.3,0.1

Type RM Length L Ch R = 1 ,165     ,0,0,0
BEGIN DESCRIPTION:
UNT016 IN SUCR 1.0
END DESCRIPTION:
XS GIS Cut Line= 4
      2299388.82     13442382.99      2298914.89     13442987.12
      2298894.06     13443336.08      2299831.57     13443778.79
#Sta/Elev= 30
  4009.3  391.73  4034.3  390.88  4055.1  391.54    4113  388.09  4148.2  388.55
  4176.4  386.92  4241.3  384.61  4255.7  385.43  4355.2  382.81  4469.1  381.69
  4475.5  382.81  4497.2  382.81  4518.8  381.66  4675.1  379.66  4738.7  377.99
  4897.1  377.56  4957.2  378.51  4976.8  378.05    4997  375.88  5027.3  378.38
  5037.3  378.94  5067.4  378.28  5143.8  379.49  5166.6  378.97  5627.5  383.96
  5837.9  387.14  5971.2  390.16  6053.9  390.85  6082.2  392.29  6163.5  392.29
#Mann= 4 ,-1 , 0
  4009.3      .1       0  4176.4     .05       0  4957.2     .03       0
  5037.3     .05       0
Bank Sta=4976.8,5027.3
XS Rating Curve= 0 ,0
Exp/Cntr=0.3,0.1

Chan Stop Cuts=-1
Use User Specified Reach Order=0
Composite Channel Slope=5