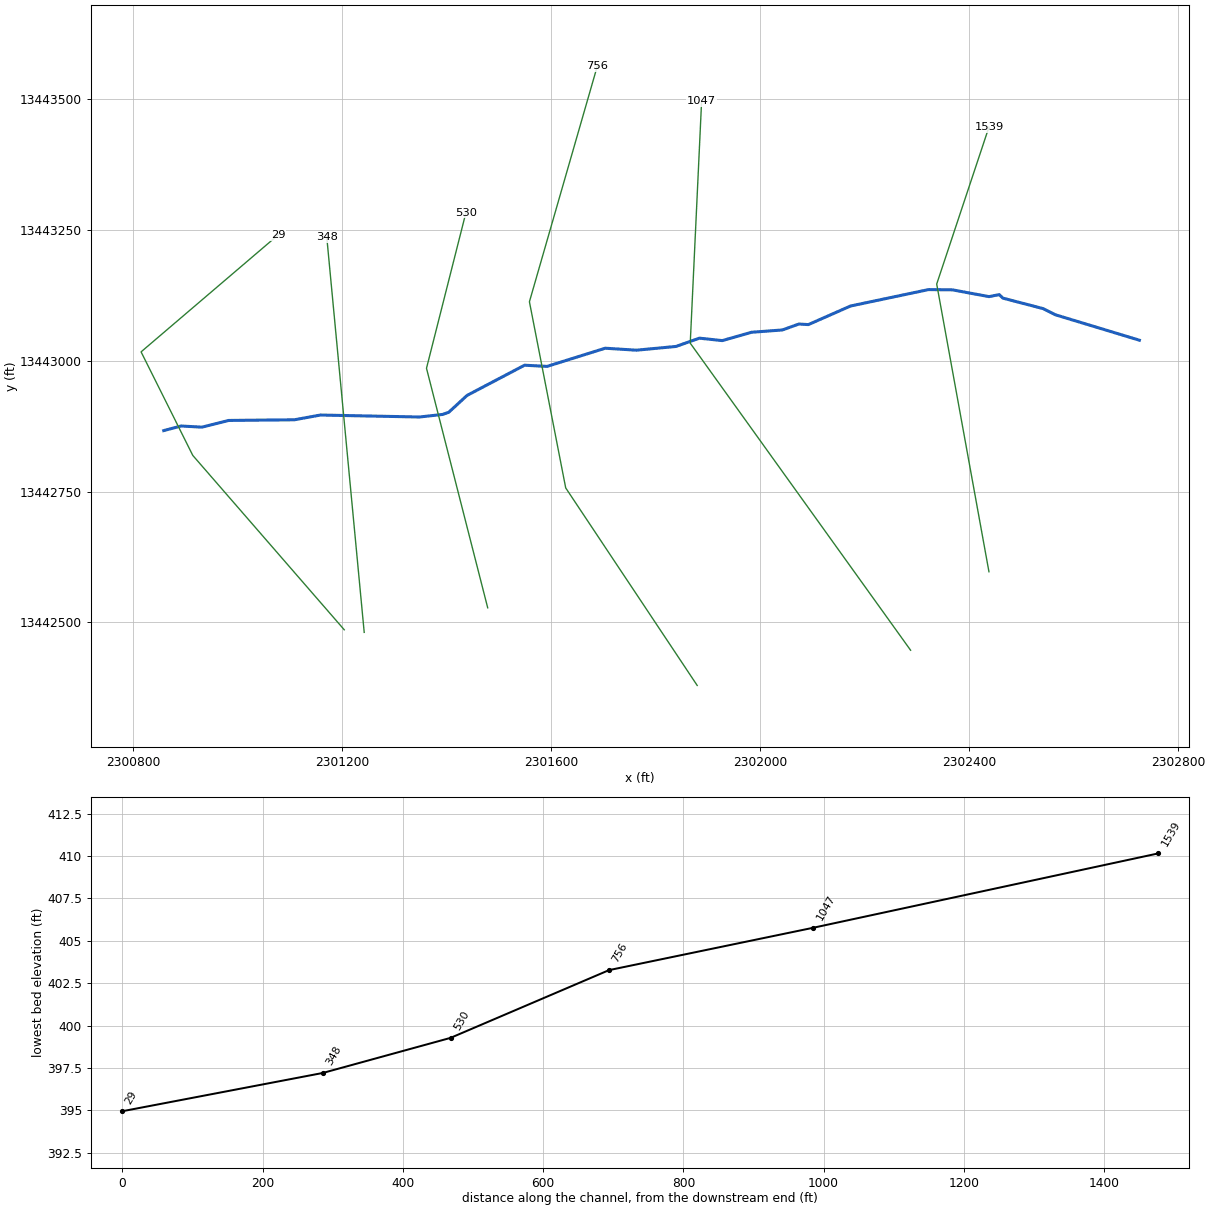
--- UNT017 IN SUCR.prj (project) ---

Proj Title=UNT017 IN SUCR Base Level Engineering
Current Plan=p01
Default Exp/Contr=0.3,0.1
English Units
Geom File=g01
Flow File=f01
Plan File=p01
Y Axis Title=Elevation
X Axis Title(PF)=Main Channel Distance
X Axis Title(XS)=Station
BEGIN DESCRIPTION:
UNT017 IN SUCR
END DESCRIPTION:
DSS Export Rating Curves= 0
DSS Export Rating Curve Sorted= 0
DSS Export Volume Flow Curves= 0
DXF OffsetX= 0
DXF OffsetY= 0
DXF ScaleX= 1
DXF ScaleY= 10

--- UNT017 IN SUCR.p01 (plan) ---

Plan Title=Multiple Run
Short Identifier=Multiple
Geom File=g01
Flow File=f01
Subcritical Flow
K Sum by GR= 0
Std Step Tol= 0.01
Critical Tol= 0.01
Num of Std Step Trials= 20
Max Error Tol= 0.3
Flow Tol Ratio= 0.001
Split Flow NTrial= 30
Split Flow Tol= 0.02
Split Flow Ratio= 0.02
Log Output Level= 0
Friction Slope Method= 1
Unsteady Friction Slope Method= 2
Unsteady Bridges Friction Slope Method= 1
Parabolic Critical Depth
Global Vel Dist=  1 , 1 , 1
Global Log Level= 0
CheckData=True
Encroach Param= -1, 0, 0, 0
BEGIN DESCRIPTION:
Multiple Run
END DESCRIPTION:

--- UNT017 IN SUCR.f01 (steady flow) ---

Flow Title=Multiple
Program Version=4.10
Number of Profiles= 7
Profile Names=10-year,25-year,50-year,1pct_min,100-year,1pct_plu,500-year
River Rch & RM=UNT017 IN SUCR,Reach-1         ,1539
     280     378     458     406     550     743     794
Boundary for River Rch & Prof#=UNT017 IN SUCR,Reach-1         , 1
Up Type= 0
Dn Type= 3
Dn Slope=0.02
Boundary for River Rch & Prof#=UNT017 IN SUCR,Reach-1         , 2
Up Type= 0
Dn Type= 3
Dn Slope=0.02
Boundary for River Rch & Prof#=UNT017 IN SUCR,Reach-1         , 3
Up Type= 0
Dn Type= 3
Dn Slope=0.02
Boundary for River Rch & Prof#=UNT017 IN SUCR,Reach-1         , 4
Up Type= 0
Dn Type= 3
Dn Slope=0.02
Boundary for River Rch & Prof#=UNT017 IN SUCR,Reach-1         , 5
Up Type= 0
Dn Type= 3
Dn Slope=0.02
Boundary for River Rch & Prof#=UNT017 IN SUCR,Reach-1         , 6
Up Type= 0
Dn Type= 3
Dn Slope=0.02
Boundary for River Rch & Prof#=UNT017 IN SUCR,Reach-1         , 7
Up Type= 0
Dn Type= 3
Dn Slope=0.02
DSS Import GetInterval= 0
DSS Import GetPeak= 0
DSS Import FillOption= 0

--- UNT017 IN SUCR.g01 (geometry) ---

Geom Title=Existing Conditions
Program Version=4.10

River Reach=UNT017 IN SUCR  ,Reach-1
Reach XY= 30
      2302725.73     13443039.45      2302564.96     13443088.06
      2302541.35     13443099.87      2302464.47     13443119.88
      2302457.32      13443126.6      2302437.87     13443122.77
      2302367.83     13443135.73      2302322.01     13443136.23
      2302172.84     13443104.86      2302092.04     13443069.31
      2302073.95     13443070.39      2302042.24     13443059.04
      2301983.27     13443054.64      2301927.32     13443038.71
       2301883.5     13443043.36      2301838.65     13443027.53
      2301762.86     13443020.37      2301703.29     13443024.16
      2301591.84      13442989.4      2301548.79     13442991.66
      2301438.84     13442933.98      2301403.59     13442901.63
      2301391.76     13442897.56      2301347.92     13442892.66
       2301157.9     13442896.41      2301108.13     13442887.34
      2300982.49     13442886.08      2300931.35     13442873.26
      2300891.37     13442875.45      2300858.05     13442866.65

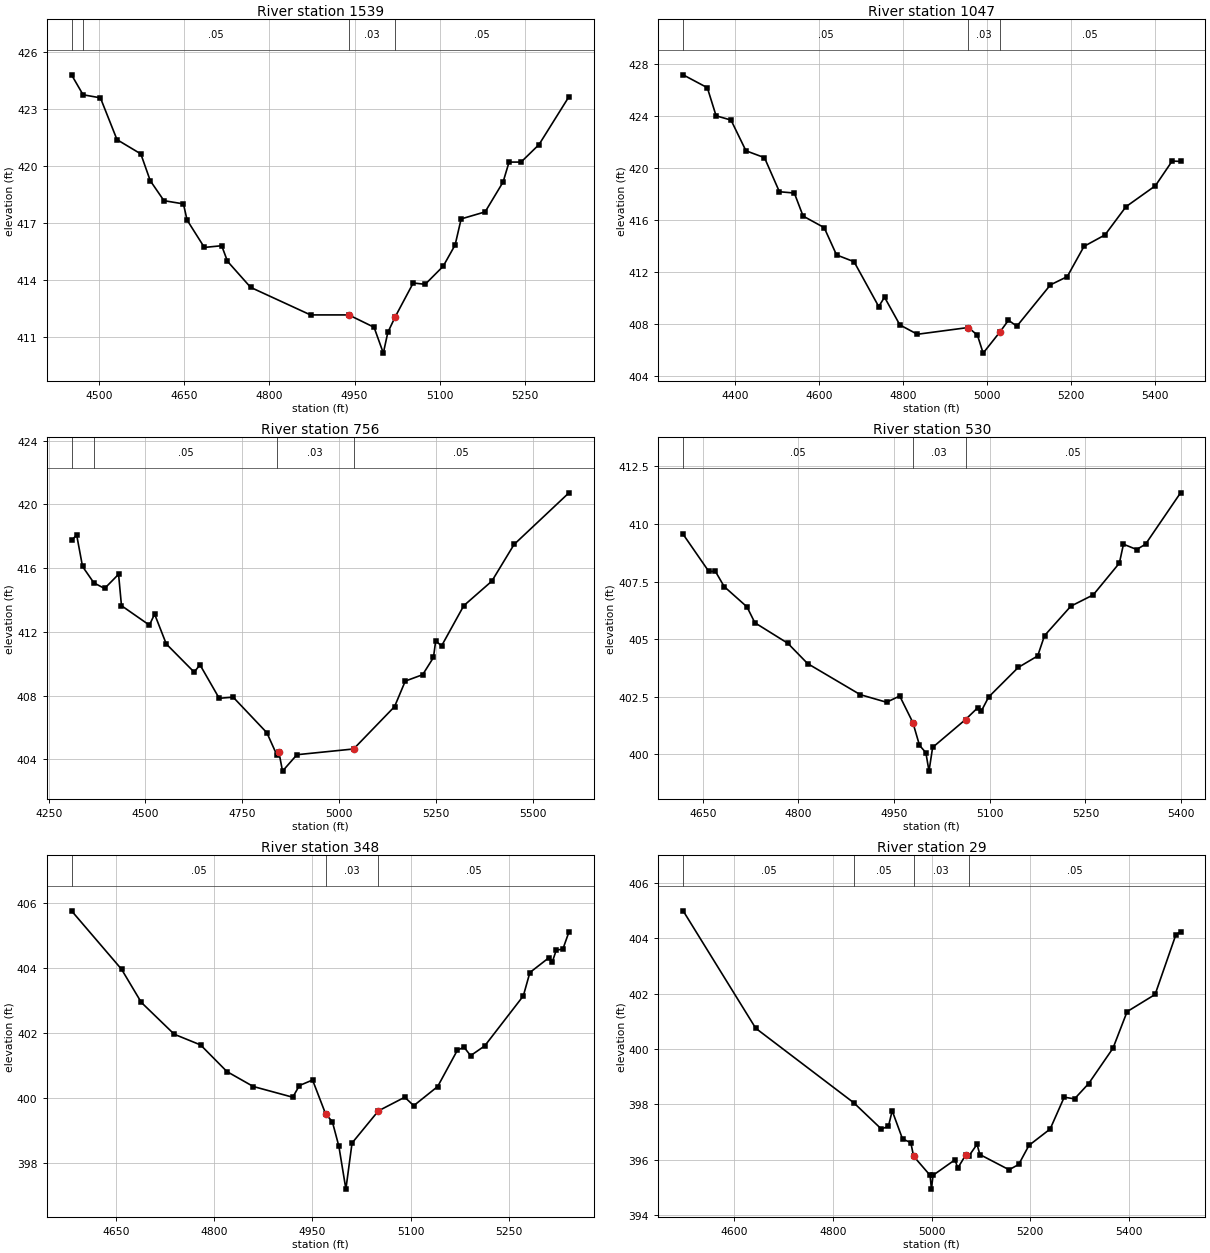
Type RM Length L Ch R = 1 ,1539    ,492,492,492
BEGIN DESCRIPTION:
UNT017 IN SUCR 3.0
END DESCRIPTION:
XS GIS Cut Line= 3
      2302437.72     13442596.88      2302337.72     13443146.85
      2302437.71     13443446.83
#Sta/Elev= 30
    4452   424.8  4472.3  423.75  4502.8  423.59    4532  421.39  4573.9  420.64
  4590.5  419.23  4614.6  418.18  4648.9  418.01  4655.3  417.16  4685.7  415.72
  4716.2  415.81  4726.4  414.99  4767.1  413.62  4872.5  412.17  4939.8  412.17
  4984.3  411.52  5000.6  410.16  5008.5  411.25  5021.5  412.07  5053.2  413.85
  5074.2  413.78  5105.9  414.73  5126.9  415.85  5137.5  417.22  5179.7  417.59
  5211.3  419.16  5221.8  420.21  5242.9  420.21  5274.5  421.13  5327.2  423.65
#Mann= 4 ,-1 , 0
    4452     .05       0  4472.3     .05       0  4939.8     .03       0
  5021.5     .05       0
Bank Sta=4939.8,5021.5
XS Rating Curve= 0 ,0
Exp/Cntr=0.3,0.1

Type RM Length L Ch R = 1 ,1047    ,291,291,291
BEGIN DESCRIPTION:
UNT017 IN SUCR 2.0
END DESCRIPTION:
XS GIS Cut Line= 3
      2302287.72     13442446.85      2301865.95     13443033.79
      2301887.72     13443496.81
#Sta/Elev= 30
  4275.6  427.17  4333.3  426.18  4354.2  424.02  4389.8  423.69  4425.4  421.33
  4469.6   420.8  4505.2  418.18  4540.8  418.08  4561.7  416.31    4612  415.42
  4641.5  413.32  4683.2   412.8  4742.1  409.35  4755.9  410.07  4792.5  407.94
  4834.2  407.22  4955.8  407.74  4977.5  407.15  4991.1  405.77  5031.5  407.41
  5051.5   408.3  5071.5  407.84  5151.6  411.02  5191.6  411.65  5231.7  413.98
  5281.7  414.86  5331.8  417.03  5401.9  418.64  5441.9  420.54  5461.9  420.51
#Mann= 3 , 0 , 0
  4275.6     .05       0  4955.8     .03       0  5031.5     .05       0
Bank Sta=4955.8,5031.5
XS Rating Curve= 0 ,0
Exp/Cntr=0.3,0.1

Type RM Length L Ch R = 1 ,756     ,226,226,226
BEGIN DESCRIPTION:
Mapping XS a9582e6c1
END DESCRIPTION:
XS GIS Cut Line= 4
      2301879.28     13442379.51      2301627.57     13442757.08
      2301558.12     13443112.99      2301687.97     13443563.13
#Sta/Elev= 30
    4309  417.75  4322.3  418.08  4337.4  416.11  4366.7  415.08  4394.4  414.73
  4430.5  415.62    4438  413.65  4510.1  412.43  4523.6  413.12  4553.7  411.25
  4625.8  409.48  4640.8  409.94  4690.4  407.84  4726.5  407.91  4813.5  405.68
  4839.6  404.27  4844.7  404.46    4854  403.27  4891.2   404.3  5037.6  404.66
  5143.5  407.32  5171.1  408.92    5216  409.32  5243.9   410.4  5249.7  411.45
  5264.7  411.12  5322.2  413.65  5394.7  415.19  5452.1  417.49  5593.9  420.73
#Mann= 4 ,-1 , 0
    4309      .1       0  4366.7     .05       0  4839.6     .03       0
  5037.6     .05       0
Bank Sta=4844.7,5037.6
XS Rating Curve= 0 ,0
Exp/Cntr=0.3,0.1

Type RM Length L Ch R = 1 ,530     ,182,182,182
BEGIN DESCRIPTION:
Mapping XS a9582e6c
END DESCRIPTION:
XS GIS Cut Line= 3
      2301478.28     13442527.87      2301361.09     13442985.78
      2301436.62     13443283.58
#Sta/Elev= 30
  4619.3  409.55  4659.5  407.94  4669.9  407.94  4683.7  407.28  4719.4   406.4
  4731.8  405.71  4783.4  404.82  4814.4  403.94    4897  402.59  4938.2  402.26
  4958.9  402.53  4979.5  401.38  4989.9  400.39  4999.9  400.07  5004.8  399.27
  5010.5   400.3  5062.1  401.51  5081.5  402.03  5086.7  401.87  5098.4  402.49
  5144.7  403.77  5175.2  404.27  5185.9  405.15  5227.2  406.43  5262.3  406.92
  5303.3   408.3  5309.7  409.12  5330.4  408.89  5344.3  409.12  5399.2  411.35
#Mann= 3 , 0 , 0
  4619.3     .05       0  4979.5     .03       0  5062.1     .05       0
Bank Sta=4979.5,5062.1
XS Rating Curve= 0 ,0
Exp/Cntr=0.3,0.1

Type RM Length L Ch R = 1 ,348     ,286,286,286
BEGIN DESCRIPTION:
Mapping XS 934a9e52
END DESCRIPTION:
XS GIS Cut Line= 2
      2301241.86     13442480.94      2301170.24     13443236.15
#Sta/Elev= 30
  4582.6  405.77  4658.9  403.97    4689  402.95  4739.2  401.97  4779.4  401.64
  4819.6  400.82  4859.8  400.36    4920  400.03  4930.1  400.39  4950.2  400.56
  4970.2  399.51  4980.3  399.28  4990.3  398.52    5001   397.2  5010.4  398.62
  5050.6  399.61  5090.8  400.03  5104.5  399.77    5141  400.36  5171.1  401.48
  5181.2  401.57  5191.2  401.31  5212.7  401.61  5271.6  403.15  5281.6  403.87
  5310.9  404.33  5315.9   404.2  5321.8  404.56  5331.9  404.59  5341.2  405.12
#Mann= 3 , 0 , 0
  4582.6     .05       0  4970.2     .03       0  5050.6     .05       0
Bank Sta=4970.2,5050.6
XS Rating Curve= 0 ,0
Exp/Cntr=0.3,0.1

Type RM Length L Ch R = 1 ,29      ,0,0,0
BEGIN DESCRIPTION:
UNT017 IN SUCR 1.0
END DESCRIPTION:
XS GIS Cut Line= 4
      2301203.66     13442485.93      2300913.73     13442819.26
      2300814.77     13443017.18      2301076.89     13443240.49
#Sta/Elev= 30
  4496.9  404.99  4643.9  400.75  4842.4  398.06  4898.4  397.11  4912.7  397.21
  4920.3  397.77  4941.3  396.75    4958  396.62  4963.6  396.13    4997  395.44
  4999.8  394.94    5003  395.44  5047.5     396  5053.1   395.7  5069.8  396.19
  5075.4  396.13  5092.2  396.56  5097.8  396.19    5157  395.64  5176.5  395.83
  5197.3  396.52  5240.2  397.11  5268.7  398.26  5289.6   398.2  5318.1  398.75
  5367.5  400.03  5396.1  401.35  5452.8  401.97  5494.9  404.13  5504.3  404.23
#Mann= 4 ,-1 , 0
  4496.9     .05       0  4842.4     .05       0  4963.6     .03       0
  5075.4     .05       0
Bank Sta=4963.6,5069.8
XS Rating Curve= 0 ,0
Exp/Cntr=0.3,0.1

Chan Stop Cuts=-1
Use User Specified Reach Order=0
Composite Channel Slope=5