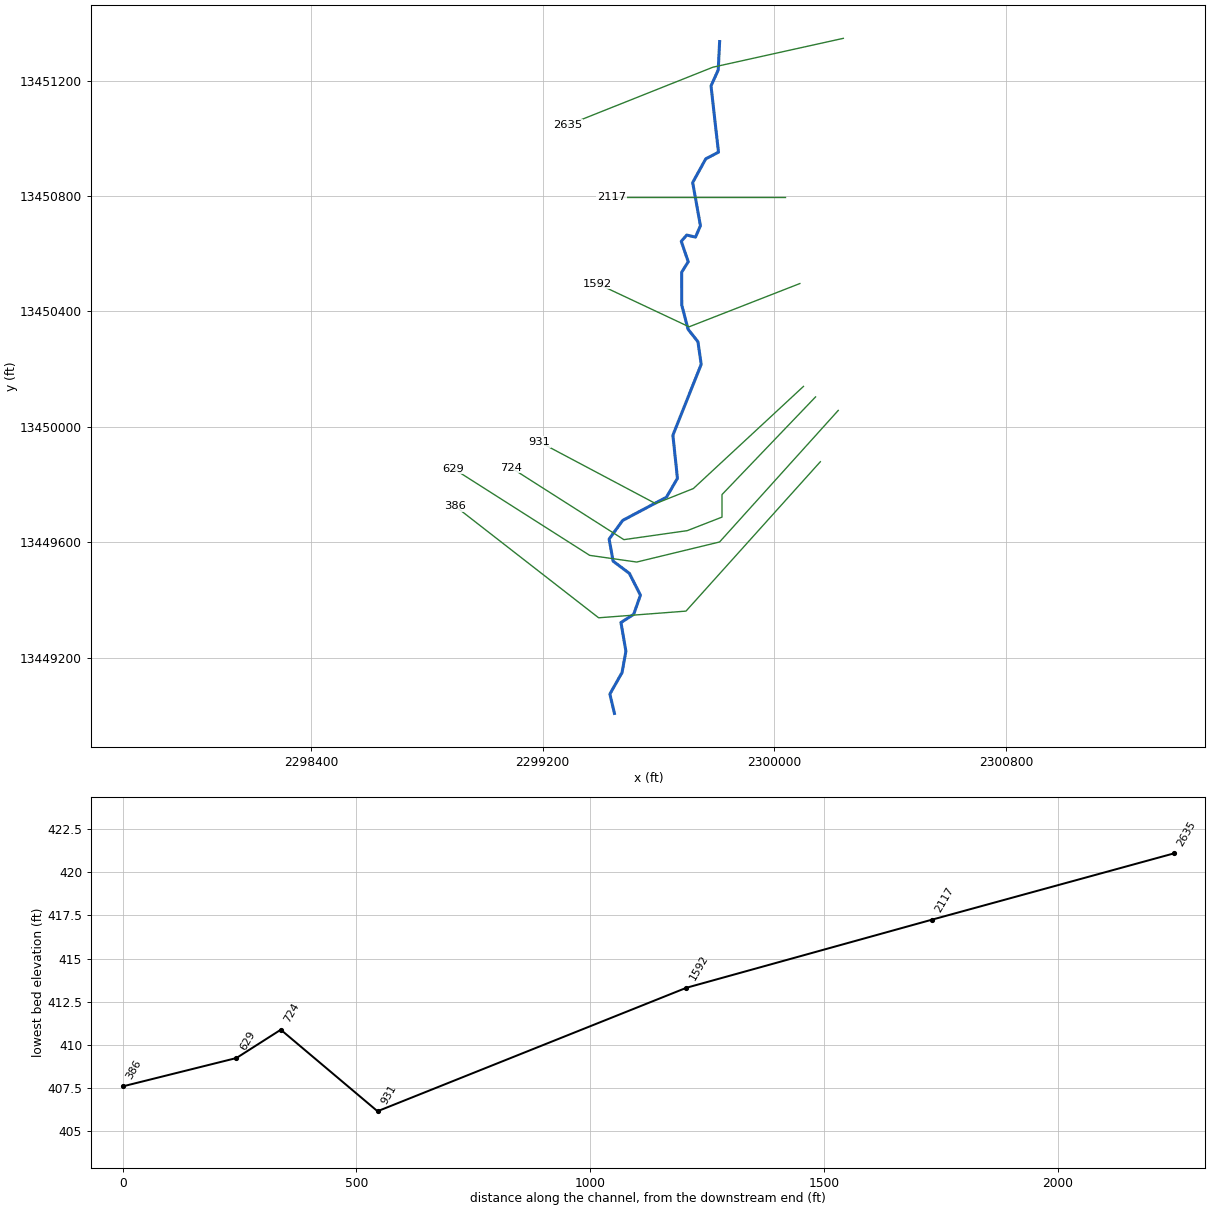
--- UNT019 IN SUCR.prj (project) ---

Proj Title=UNT019 IN SUCR Base Level Engineering
Current Plan=p01
Default Exp/Contr=0.3,0.1
English Units
Geom File=g01
Flow File=f01
Plan File=p01
BEGIN DESCRIPTION:
UNT019 IN SUCR
END DESCRIPTION:

--- UNT019 IN SUCR.p01 (plan) ---

Plan Title=Multiple Run
Short Identifier=Multiple
Geom File=g01
Flow File=f01
Subcritical Flow
K Sum by GR= 0
Std Step Tol= 0.01
Critical Tol= 0.01
Num of Std Step Trials= 20
Max Error Tol= 0.3
Flow Tol Ratio= 0.001
Split Flow NTrial= 30
Split Flow Tol= 0.02
Split Flow Ratio= 0.02
Log Output Level= 0
Friction Slope Method= 1
Unsteady Friction Slope Method= 2
Unsteady Bridges Friction Slope Method= 1
Parabolic Critical Depth
Global Vel Dist=  1 , 1 , 1
Global Log Level= 0
CheckData=True
Encroach Param= -1, 0, 0, 0
BEGIN DESCRIPTION:
Multiple Run
END DESCRIPTION:

--- UNT019 IN SUCR.f01 (steady flow) ---

Flow Title=Multiple
Number of Profiles=7
Profile Names=10-year,25-year,50-year,1pct_min,100-year,1pct_plu,500-year
River Rch & RM= UNT019 IN SUCR,Reach-1,2635
     464     644     792     714     965    1306    1436
Boundary for River Rch & Prof#=UNT019 IN SUCR,Reach-1,1
Up Type=0
Dn Type=3
Dn Slope=0.005
Boundary for River Rch & Prof#=UNT019 IN SUCR,Reach-1,2
Up Type=0
Dn Type=3
Dn Slope=0.005
Boundary for River Rch & Prof#=UNT019 IN SUCR,Reach-1,3
Up Type=0
Dn Type=3
Dn Slope=0.005
Boundary for River Rch & Prof#=UNT019 IN SUCR,Reach-1,4
Up Type=0
Dn Type=3
Dn Slope=0.005
Boundary for River Rch & Prof#=UNT019 IN SUCR,Reach-1,5
Up Type=0
Dn Type=3
Dn Slope=0.005
Boundary for River Rch & Prof#=UNT019 IN SUCR,Reach-1,6
Up Type=0
Dn Type=3
Dn Slope=0.005
Boundary for River Rch & Prof#=UNT019 IN SUCR,Reach-1,7
Up Type=0
Dn Type=3
Dn Slope=0.005

--- UNT019 IN SUCR.g01 (geometry) ---

Geom Title=Existing Conditions

River Reach=UNT019 IN SUCR,Reach-1
Reach XY= 30
      2299810.79     13451335.67      2299805.94     13451237.20
      2299781.01     13451181.83      2299806.86     13450952.20
      2299762.86     13450929.14      2299717.72     13450846.86
      2299744.48     13450697.59      2299727.52     13450657.62
      2299697.33     13450665.05      2299678.39     13450643.24
      2299702.42     13450572.39      2299679.67     13450536.11
      2299680.00     13450422.64      2299701.83     13450338.51
      2299735.84     13450295.14      2299747.17     13450216.83
      2299649.47     13449971.02      2299665.15     13449821.73
      2299627.38     13449756.28      2299476.08     13449675.64
      2299429.36     13449611.17      2299443.25     13449534.40
      2299499.21     13449492.21      2299537.40     13449416.74
      2299514.20     13449350.18      2299470.20     13449321.80
      2299487.26     13449222.25      2299473.94     13449148.37
      2299431.90     13449073.84      2299447.72     13449006.86

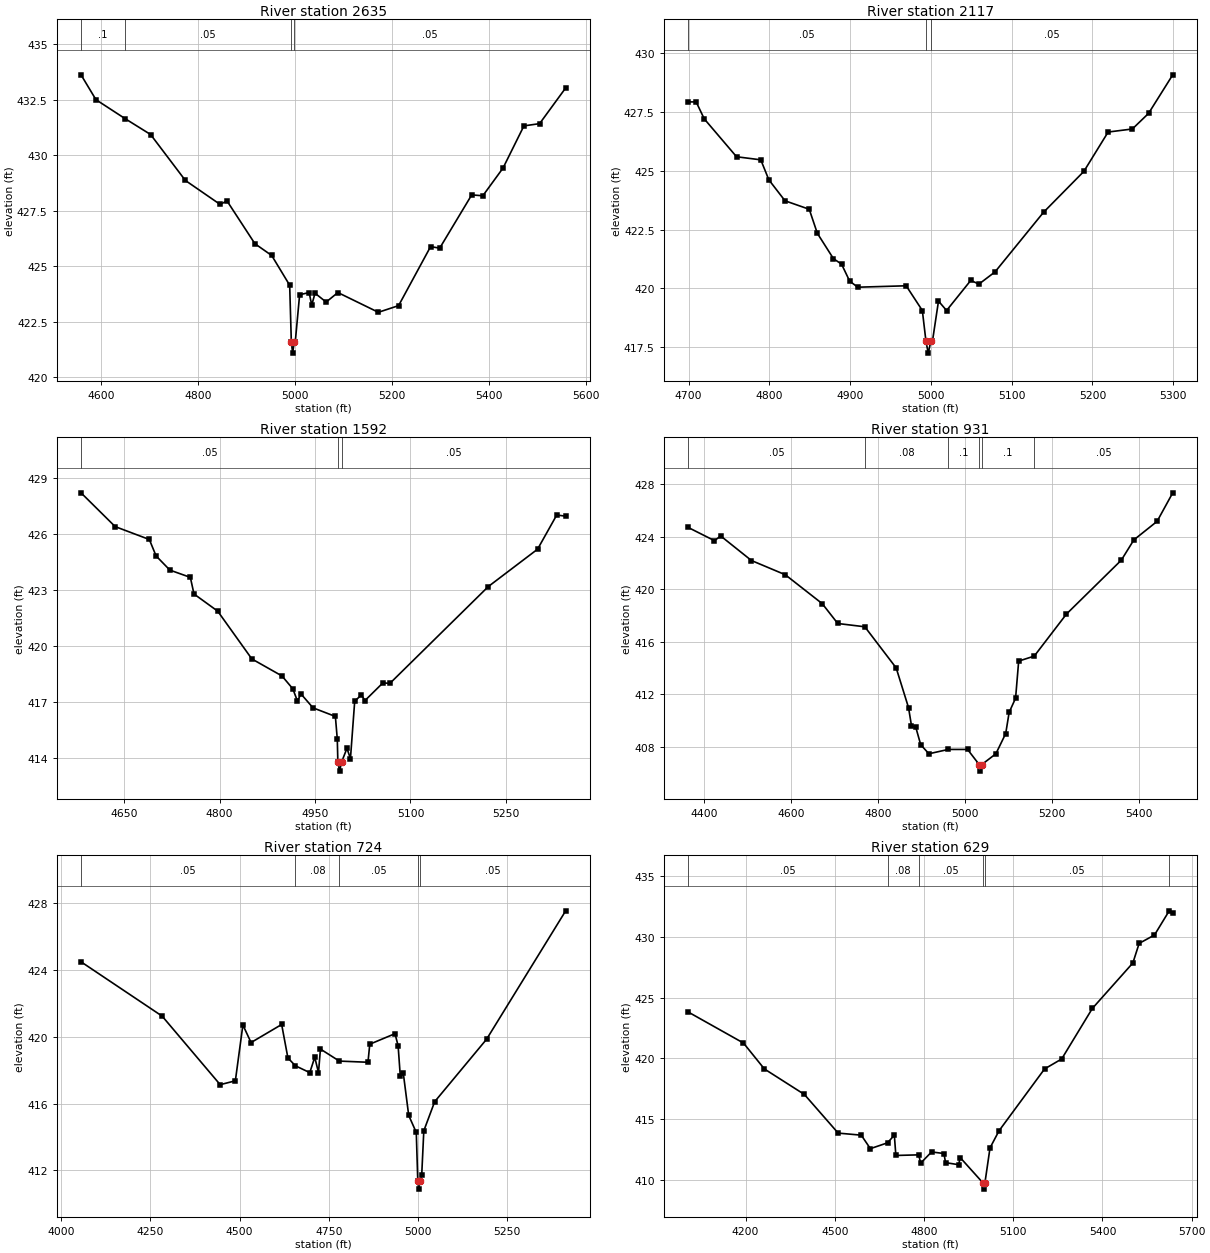
Type RM Length L Ch R = 1,2635,518,518,518
BEGIN DESCRIPTION:
UNT019 IN SUCR 4.0
END DESCRIPTION:
XS GIS Cut Line= 3
      2300237.77     13451346.87      2299787.72     13451246.85
      2299287.76     13451046.87
#Sta/Elev= 30
  4559.3  433.63  4590.1  432.51  4649.9  431.66  4702.8  430.94  4774.5  428.87
  4846.2  427.79  4860.3  427.95  4917.9  426.02  4952.5  425.49  4989.6  424.15
  4993.0  421.59  4995.7  421.09  4999.0  421.59  5001.1  421.59  5010.1  423.72
  5029.7  423.82  5035.1  423.26  5041.9  423.79  5064.8  423.39  5089.0  423.82
  5172.5  422.93  5214.2  423.23  5280.2  425.89  5299.0  425.82  5365.0  428.22
  5387.9  428.18  5429.6  429.43  5472.7  431.33  5505.0  431.43  5558.8  433.04
#Mann=4,-1,0
  4559.3     0.1       0  4649.9    0.05       0  4993.0    0.03       0
  4999.0    0.05       0
Bank Sta=4993,4999
Exp/Cntr=0.3,0.1

Type RM Length L Ch R = 1,2117,525,525,525
BEGIN DESCRIPTION:
UNT019 IN SUCR 3.0
END DESCRIPTION:
XS GIS Cut Line= 3
      2300037.77     13450796.85      2299737.72     13450796.85
      2299437.77     13450796.85
#Sta/Elev= 30
  4699.4  427.92  4709.4  427.92  4719.4  427.20  4759.4  425.59  4789.4  425.46
  4799.4  424.61  4819.4  423.72  4849.4  423.36  4859.4  422.34  4879.4  421.26
  4889.4  421.03  4899.4  420.31  4909.4  420.05  4969.4  420.11  4989.4  419.06
  4993.9  417.75  4996.7  417.25  4999.9  417.75  5001.9  417.75  5009.4  419.46
  5019.4  419.06  5049.4  420.34  5059.4  420.18  5079.4  420.70  5139.4  423.23
  5189.4  424.97  5219.4  426.64  5249.4  426.77  5269.4  427.43  5299.4  429.07
#Mann=3,-1,0
  4699.4    0.05       0  4993.9    0.03       0  4999.9    0.05       0
Bank Sta=4993.9,4999.9
Exp/Cntr=0.3,0.1

Type RM Length L Ch R = 1,1592,661,661,661
BEGIN DESCRIPTION:
UNT019 IN SUCR 2.0
END DESCRIPTION:
XS GIS Cut Line= 3
      2300087.75     13450496.86      2299705.39     13450346.85
      2299387.75     13450496.84
#Sta/Elev= 30
  4582.0  428.22  4635.7  426.41  4689.4  425.72  4700.0  424.84  4721.7  424.08
  4753.9  423.69  4759.6  422.80  4796.9  421.88  4850.6  419.32  4897.9  418.41
  4915.0  417.72  4922.3  417.06  4927.7  417.45  4946.8  416.70  4981.9  416.24
  4984.9  415.03  4985.8  413.81  4988.5  413.31  4991.8  413.81  5000.1  414.53
  5005.6  413.98  5012.3  417.06  5022.8  417.39  5028.4  417.09  5056.7  418.04
  5067.6  418.01  5222.4  423.20  5299.8  425.20  5329.9  427.03  5344.0  426.97
#Mann=3,-1,0
  4582.0    0.05       0  4985.8    0.04       0  4991.8    0.05       0
Bank Sta=4985.8,4991.8
Exp/Cntr=0.3,0.1

Type RM Length L Ch R = 1,931,207,207,207
BEGIN DESCRIPTION:
Mapping XS 027bcffd
END DESCRIPTION:
XS GIS Cut Line= 4
      2300100.25     13450140.35      2299720.02     13449786.16
      2299589.81     13449734.08      2299188.79     13449947.61
#Sta/Elev= 30
  4363.3  424.70  4424.0  423.69  4438.2  424.05  4509.0  422.18  4586.7  421.10
  4671.7  418.90  4707.4  417.39  4769.6  417.14  4841.7  414.01  4870.1  410.99
  4876.9  409.61  4886.9  409.48  4898.1  408.17  4916.9  407.48  4961.5  407.81
  5005.8  407.81  5032.5  406.66  5035.2  406.16  5038.5  406.66  5070.9  407.48
  5093.5  409.02  5101.4  410.63  5116.2  411.71  5123.3  414.53  5159.1  414.91
  5233.2  418.11  5359.3  422.21  5388.1  423.75  5441.5  425.16  5477.5  427.33
#Mann=6,-1,0
  4363.3    0.05       0  4769.6    0.08       0  4961.5     0.1       0
  5032.5    0.07       0  5038.5     0.1       0  5159.1    0.05       0
Bank Sta=5032.5,5038.5
Exp/Cntr=0.3,0.1

Type RM Length L Ch R = 1,724,95,95,95
BEGIN DESCRIPTION:
Mapping XS 6d563a78
END DESCRIPTION:
XS GIS Cut Line= 6
      2300141.87     13450103.85      2299818.97     13449765.33
      2299818.97     13449687.20      2299699.18     13449640.33
      2299480.43     13449609.08      2299091.26     13449858.15
#Sta/Elev= 30
  4055.8  424.48  4283.0  421.23  4445.6  417.13  4488.1  417.36  4509.2  420.70
  4532.1  419.65  4617.8  420.73  4635.3  418.73  4656.2  418.26  4696.6  417.85
  4710.5  418.77  4721.0  417.85  4726.4  419.26  4779.4  418.54  4859.6  418.47
  4864.6  419.55  4935.3  420.18  4944.0  419.46  4950.2  417.62  4958.5  417.82
  4973.7  415.29  4994.9  414.27  4999.1  411.38  5001.8  410.88  5005.1  411.38
  5010.1  411.71  5016.0  414.37  5046.4  416.11  5191.9  419.85  5413.4  427.53
#Mann=5,-1,0
  4055.8    0.05       0  4656.2    0.08       0  4779.4    0.05       0
  4999.1    0.03       0  5005.1    0.05       0
Bank Sta=4999.1,5005.1
Exp/Cntr=0.3,0.1

Type RM Length L Ch R = 1,629,243,243,243
BEGIN DESCRIPTION:
Mapping XS f822aaac
END DESCRIPTION:
XS GIS Cut Line= 5
      2300220.26     13450057.03      2299810.60     13449600.99
      2299524.59     13449531.42      2299362.26     13449554.61
      2298891.75     13449855.42
#Sta/Elev= 30
  4006.6  423.82  4192.9  421.26  4263.1  419.13  4397.7  417.03  4511.3  413.85
  4589.0  413.68  4619.6  412.57  4677.2  413.05  4700.2  413.68  4705.3  412.01
  4782.0  412.06  4788.8  411.38  4825.4  412.30  4867.1  412.17  4872.3  411.42
  4916.5  411.25  4921.5  411.84  4998.7  409.74  5001.5  409.24  5004.7  409.74
  5021.9  412.63  5052.2  414.04  5205.4  419.13  5262.9  419.95  5366.1  424.11
  5502.3  427.85  5523.4  429.46  5575.0  430.15  5624.5  432.14  5636.4  431.96
#Mann=6,-1,0
  4006.6    0.05       0  4677.2    0.08       0  4782.0    0.05       0
  4998.7    0.03       0  5004.7    0.05       0  5624.5     0.1       0
Bank Sta=4998.7,5004.7
Exp/Cntr=0.3,0.1

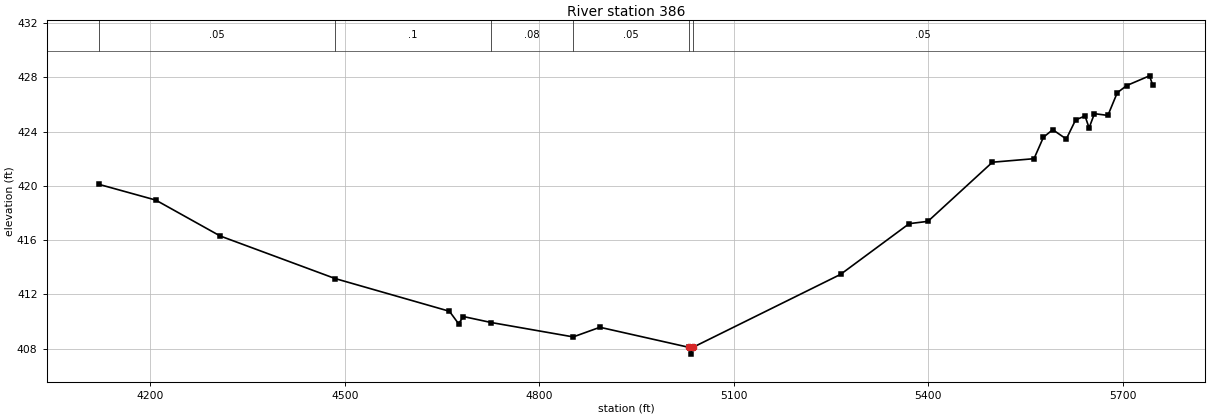
Type RM Length L Ch R = 1,386,0,0,0
BEGIN DESCRIPTION:
UNT019 IN SUCR 1.0
END DESCRIPTION:
XS GIS Cut Line= 4
      2300158.44     13449879.26      2299694.65     13449361.36
      2299393.18     13449338.17      2298898.44     13449724.69
#Sta/Elev= 30
  4121.2  420.11  4208.2  418.96  4307.7  416.31  4485.2  413.17  4661.4  410.76
  4675.5  409.84  4683.0  410.37  4725.9  409.93  4852.4  408.87  4893.6  409.58
  5031.0  408.10  5033.7  407.60  5037.0  408.10  5264.9  413.48  5370.8  417.22
  5399.7  417.39  5499.2  421.75  5563.4  422.01  5577.9  423.59  5592.3  424.15
  5613.2  423.46  5627.6  424.87  5642.1  425.16  5648.4  424.28  5656.6  425.33
  5677.4  425.20  5691.8  426.87  5706.3  427.40  5741.6  428.12  5746.6  427.43
#Mann=6,-1,0
  4121.2    0.05       0  4485.2     0.1       0  4725.9    0.08       0
  4852.4    0.05       0  5031.0    0.03       0  5037.0    0.05       0
Bank Sta=5031,5037
Exp/Cntr=0.3,0.1

Chan Stop Cuts=-1