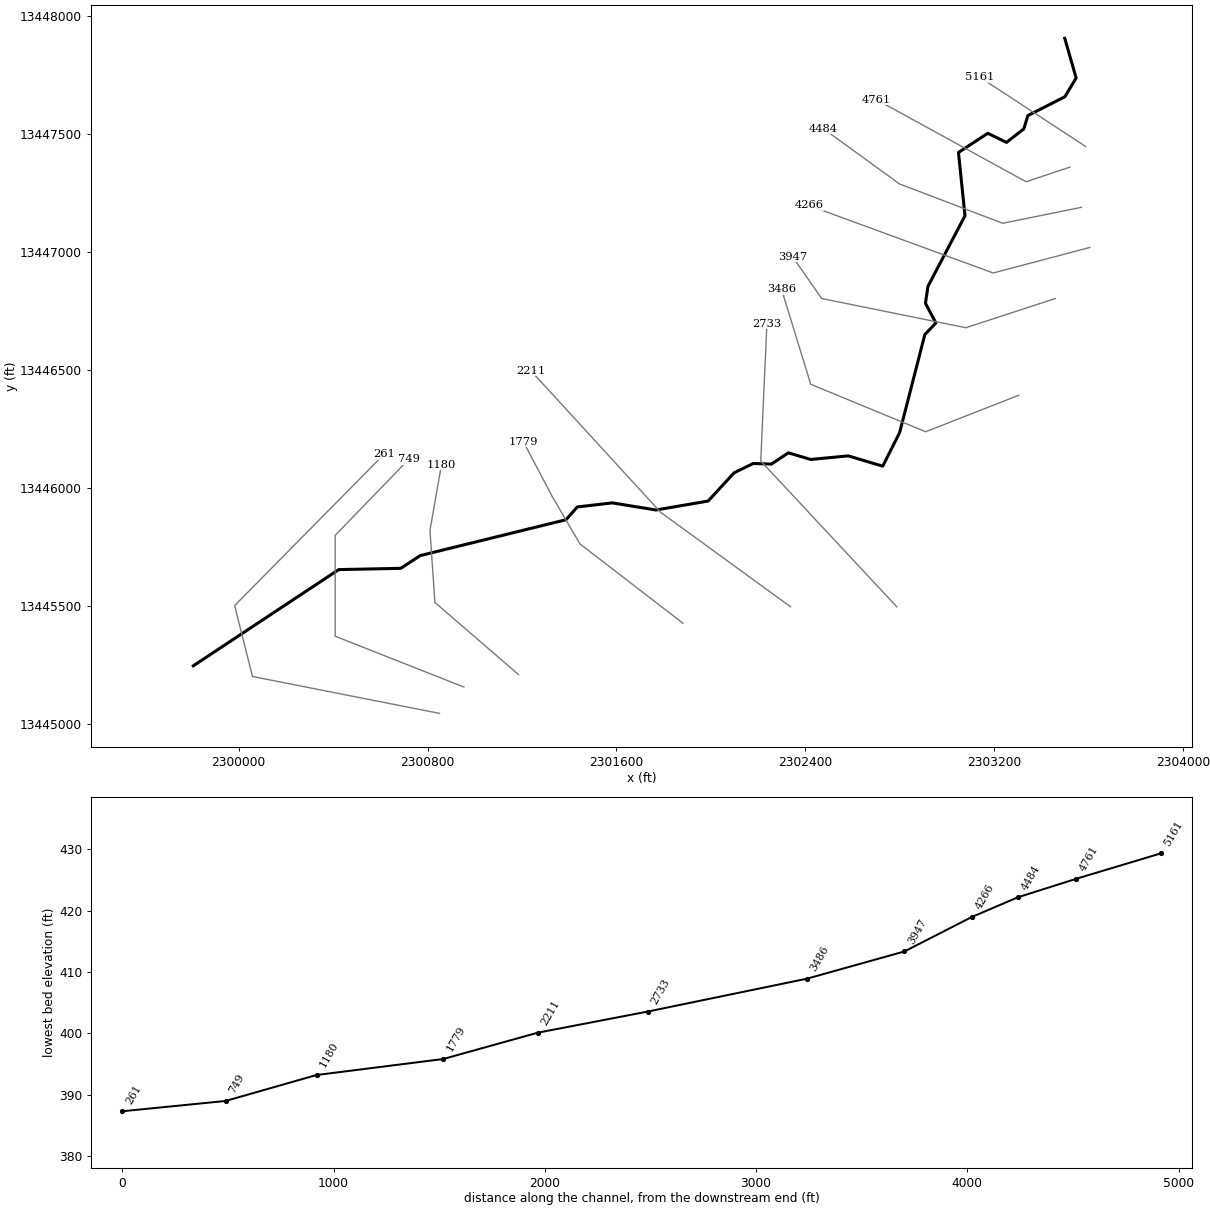
--- UNT020 IN SUCR.prj (project) ---

Proj Title=UNT020 IN SUCR Base Level Engineering
Current Plan=p01
Default Exp/Contr=0.3,0.1
English Units
Geom File=g01
Flow File=f01
Plan File=p01
Y Axis Title=Elevation
X Axis Title(PF)=Main Channel Distance
X Axis Title(XS)=Station
BEGIN DESCRIPTION:
UNT020 IN SUCR
END DESCRIPTION:
DSS Export Rating Curves= 0
DSS Export Rating Curve Sorted= 0
DSS Export Volume Flow Curves= 0
DXF OffsetX= 0
DXF OffsetY= 0
DXF ScaleX= 1
DXF ScaleY= 10

--- UNT020 IN SUCR.p01 (plan) ---

Plan Title=Multiple Run
Short Identifier=Multiple
Geom File=g01
Flow File=f01
Subcritical Flow
K Sum by GR= 0
Std Step Tol= 0.01
Critical Tol= 0.01
Num of Std Step Trials= 20
Max Error Tol= 0.3
Flow Tol Ratio= 0.001
Split Flow NTrial= 30
Split Flow Tol= 0.02
Split Flow Ratio= 0.02
Log Output Level= 0
Friction Slope Method= 1
Unsteady Friction Slope Method= 2
Unsteady Bridges Friction Slope Method= 1
Parabolic Critical Depth
Global Vel Dist=  1 , 1 , 1
Global Log Level= 0
CheckData=True
Encroach Param= -1, 0, 0, 0
BEGIN DESCRIPTION:
Multiple Run
END DESCRIPTION:

--- UNT020 IN SUCR.f01 (steady flow) ---

Flow Title=Multiple
Program Version=4.10
Number of Profiles= 7
Profile Names=10-year,25-year,50-year,1pct_min,100-year,1pct_plu,500-year
River Rch & RM=UNT020 IN SUCR,Reach-1         ,5161
     191     248     293     254     343     464     470
River Rch & RM=UNT020 IN SUCR,Reach-1         ,2733
     440     607     743     666     901    1219    1328
Boundary for River Rch & Prof#=UNT020 IN SUCR,Reach-1         , 1
Up Type= 0
Dn Type= 3
Dn Slope=0.0086
Boundary for River Rch & Prof#=UNT020 IN SUCR,Reach-1         , 2
Up Type= 0
Dn Type= 3
Dn Slope=0.0086
Boundary for River Rch & Prof#=UNT020 IN SUCR,Reach-1         , 3
Up Type= 0
Dn Type= 3
Dn Slope=0.0086
Boundary for River Rch & Prof#=UNT020 IN SUCR,Reach-1         , 4
Up Type= 0
Dn Type= 3
Dn Slope=0.0086
Boundary for River Rch & Prof#=UNT020 IN SUCR,Reach-1         , 5
Up Type= 0
Dn Type= 3
Dn Slope=0.0086
Boundary for River Rch & Prof#=UNT020 IN SUCR,Reach-1         , 6
Up Type= 0
Dn Type= 3
Dn Slope=0.0086
Boundary for River Rch & Prof#=UNT020 IN SUCR,Reach-1         , 7
Up Type= 0
Dn Type= 3
Dn Slope=0.0086
DSS Import GetInterval= 0
DSS Import GetPeak= 0
DSS Import FillOption= 0

--- UNT020 IN SUCR.g01 (geometry) ---

Geom Title=Existing Conditions
Program Version=4.10

River Reach=UNT020 IN SUCR  ,Reach-1
Reach XY= 30
      2303499.35     13447904.98      2303547.53     13447737.01
      2303499.78     13447657.59       2303343.1     13447577.73
      2303325.74      13447521.3      2303252.34     13447464.13
      2303173.39     13447502.75      2303049.09      13447421.5
      2303076.69     13447153.45      2302919.97     13446854.58
      2302909.14     13446782.72      2302953.41     13446699.38
      2302906.53      13446649.9      2302799.76     13446234.54
      2302728.15     13446092.61       2302582.4     13446136.19
      2302422.86     13446121.06      2302328.36     13446149.15
      2302256.91     13446101.55      2302179.44     13446103.84
      2302098.57     13446064.56      2301988.64     13445944.89
       2301767.6       13445907.      2301582.56     13445937.07
      2301434.35     13445919.86      2301386.35     13445865.66
      2300768.98     13445713.79      2300686.51     13445659.84
      2300423.74     13445654.43      2299807.72     13445246.86

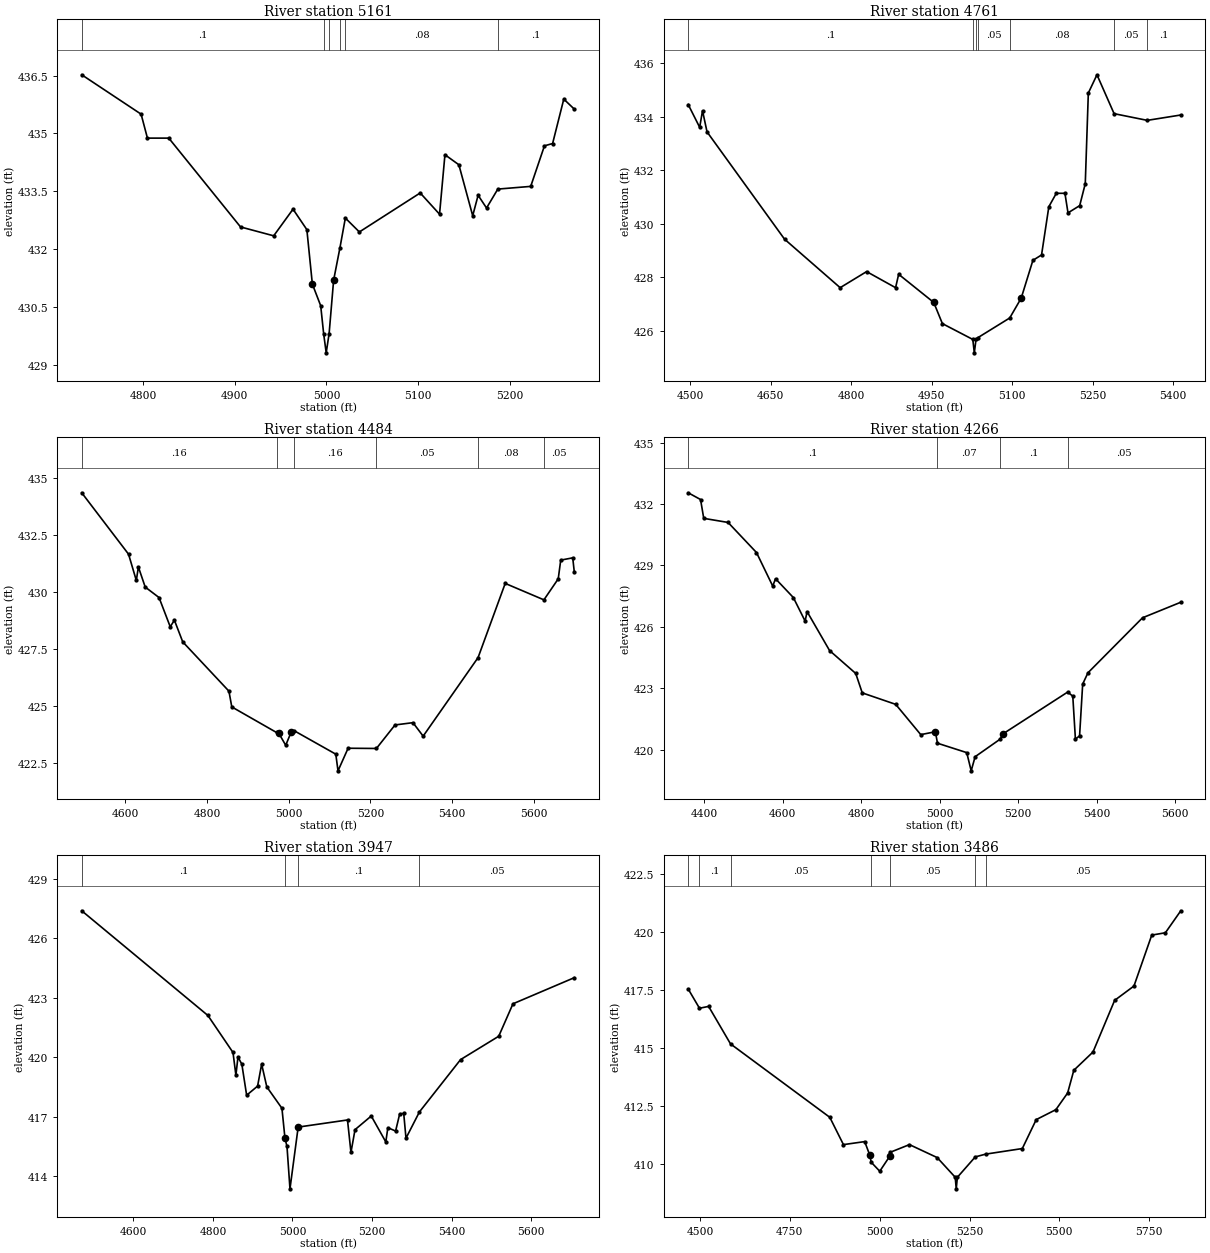
Type RM Length L Ch R = 1 ,5161    ,400,400,400
BEGIN DESCRIPTION:
UNT020 IN SUCR 8.0
END DESCRIPTION:
XS GIS Cut Line= 2
      2303587.69     13447446.87      2303137.88     13447741.29
#Sta/Elev= 30
    4733  436.52  4797.8   435.5  4804.7  434.88    4828  434.88  4906.3  432.58
  4942.5  432.35  4963.6  433.04  4978.7  432.51  4984.7   431.1  4993.8  430.54
    4997  429.82  4999.8  429.32    5003  429.82  5007.9   431.2  5014.8  432.04
  5020.7  432.81    5036  432.45  5102.4  433.46  5123.5  432.91  5129.4  434.45
  5144.6  434.19  5159.7  432.87  5165.6   433.4  5174.8  433.07  5187.1  433.56
    5223  433.63    5238  434.68  5246.9  434.74  5259.1  435.89  5270.6  435.63
#Mann= 6 ,-1 , 0
    4733      .1       0    4997     .07       0    5003      .1       0
  5014.8     .05       0  5020.7     .08       0  5187.1      .1       0
Bank Sta=4984.7,5007.9
XS Rating Curve= 0 ,0
Exp/Cntr=0.3,0.1

Type RM Length L Ch R = 1 ,4761    ,277,277,277
BEGIN DESCRIPTION:
Mapping XS 97684765
END DESCRIPTION:
XS GIS Cut Line= 3
      2303521.02     13447359.31      2303335.47     13447297.46
      2302702.16       13447645.
#Sta/Elev= 30
  4496.3  434.45  4517.7   433.6    4523  434.22  4531.4  433.43  4675.8  429.43
  4779.5  427.62  4828.8  428.22  4882.8  427.62  4888.5  428.12  4953.9  427.07
    4970  426.28  5026.7  425.69  5029.5  425.19  5032.7  425.69  5036.5  425.76
  5095.5  426.49  5116.9  427.23  5138.7  428.64  5154.8  428.84  5168.4  430.64
  5182.3  431.14  5198.4  431.14  5204.1  430.41  5225.9  430.68  5236.3   431.5
    5242  434.88  5258.1  435.56    5290  434.11  5351.8  433.86  5414.3  434.06
#Mann= 7 ,-1 , 0
  4496.3      .1       0  5026.7     .07       0  5032.7      .1       0
  5036.5     .05       0  5095.5     .08       0    5290     .05       0
  5351.8      .1       0
Bank Sta=4953.9,5116.9
XS Rating Curve= 0 ,0
Exp/Cntr=0.3,0.1

Type RM Length L Ch R = 1 ,4484    ,218,218,218
BEGIN DESCRIPTION:
Mapping XS f5853081
END DESCRIPTION:
XS GIS Cut Line= 4
      2303570.14      13447189.2      2303236.85      13447121.5
      2302799.35     13447288.16       2302476.9      13447522.2
#Sta/Elev= 30
    4493  434.35  4607.7  431.66  4626.7  430.51  4631.8   431.1  4648.5  430.22
  4682.4  429.76  4709.8  428.48    4720  428.77  4740.4  427.82  4853.6  425.66
  4860.6  424.97  4970.2  423.85  4975.6  423.82  4992.7  423.29  5005.7  423.85
  5014.1  423.92  5115.4   422.9  5120.8  422.17  5145.5  423.16  5214.9  423.15
  5260.5  424.18  5304.4  424.28  5329.4  423.69  5463.9  427.13  5530.4  430.38
  5625.2  429.66  5660.3  430.58  5666.4   431.4  5695.8   431.5  5699.7  430.87
#Mann= 6 ,-1 , 0
    4493     .16       0  4970.2     .12       0  5014.1     .16       0
  5214.9     .05       0  5463.9     .08       0  5625.2     .05       0
#XS Ineff= 2 , 0
       0                 5014.89       0  423.91
Permanent Ineff=
       F       T
Bank Sta=4975.6,5005.7
XS Rating Curve= 0 ,0
Exp/Cntr=0.3,0.1

Type RM Length L Ch R = 1 ,4266    ,319,319,319
BEGIN DESCRIPTION:
Mapping XS 18ef3ef3
END DESCRIPTION:
XS GIS Cut Line= 3
      2303605.98     13447019.17      2303196.33     13446910.96
      2302415.57     13447196.98
#Sta/Elev= 30
    4359  432.55  4390.5  432.22  4398.6   431.3  4460.6   431.1    4533  429.63
  4574.4  427.99  4581.5  428.35  4626.9  427.43  4656.9  426.28    4662  426.74
  4719.2  424.84  4785.9  423.72  4802.5  422.77  4887.7  422.21  4951.6  420.73
  4988.9  420.87  4994.2  420.31  5068.8  419.85  5080.1  418.96  5090.1  419.65
    5154  420.51  5161.3  420.77    5326  422.81    5339  422.61  5345.7  420.51
  5356.3  420.67  5364.2   423.2  5377.6  423.75  5516.7  426.44  5614.2   427.2
#Mann= 4 ,-1 , 0
    4359      .1       0  4994.2     .07       0    5154      .1       0
    5326     .05       0
Bank Sta=4988.9,5161.3
XS Rating Curve= 0 ,0
Exp/Cntr=0.3,0.1

Type RM Length L Ch R = 1 ,3947    ,461,461,461
BEGIN DESCRIPTION:
UNT020 IN SUCR 7.0
END DESCRIPTION:
XS GIS Cut Line= 4
      2303459.18     13446802.75      2303080.38     13446679.06
      2302469.71     13446802.74      2302346.05      13446980.5
#Sta/Elev= 30
  4470.3   427.4  4787.4  422.11  4850.5  420.24  4857.8  419.09    4863  420.01
  4872.7  419.65  4884.8  418.08  4912.3  418.54  4922.5  419.65  4935.5   418.5
  4973.5  417.42  4981.1  415.91  4986.2  415.49  4993.7  413.35  5014.3  416.47
  5138.3  416.83    5147  415.19  5157.2  416.34    5198  417.03  5234.6  415.72
  5239.7  416.44  5259.2  416.27  5269.4  417.13  5279.6  417.16  5285.3  415.91
  5319.2  417.24  5422.5  419.88  5518.4  421.06  5554.2   422.7  5708.4  424.02
#Mann= 4 ,-1 , 0
  4470.3      .1       0  4981.1     .07       0  5014.3      .1       0
  5319.2     .05       0
Bank Sta=4981.1,5014.3
XS Rating Curve= 0 ,0
Exp/Cntr=0.3,0.1

Type RM Length L Ch R = 1 ,3486    ,753,753,753
BEGIN DESCRIPTION:
UNT020 IN SUCR 6.0
END DESCRIPTION:
XS GIS Cut Line= 4
      2303304.52     13446393.04      2302910.32     13446238.45
      2302423.33     13446439.43      2302299.65     13446841.37
#Sta/Elev= 30
  4467.1  417.55  4498.5  416.72  4523.9   416.8  4584.9  415.18  4861.1  412.01
  4899.1  410.83  4958.3  410.96 4972.52  410.37  4976.3  410.07  5000.2  409.68
 5028.03  410.33  5029.5   410.5  5082.8  410.83    5160  410.27  5210.2  409.42
    5213  408.92  5216.2  409.42    5266   410.3  5295.2  410.42  5396.9  410.66
  5435.6  411.91  5490.3  412.34    5523  413.06  5540.2  414.04  5593.6  414.83
  5653.8  417.06  5707.6  417.68  5757.1  419.88    5795  419.98  5837.9  420.93
#Mann= 7 ,-1 , 0
  4467.1     .05       0  4498.5      .1       0  4584.9     .05       0
  4976.3    .035       0  5029.5     .05       0    5266      .1       0
  5295.2     .05       0
Bank Sta=4972.52,5028.03
XS Rating Curve= 0 ,0
Exp/Cntr=0.3,0.1

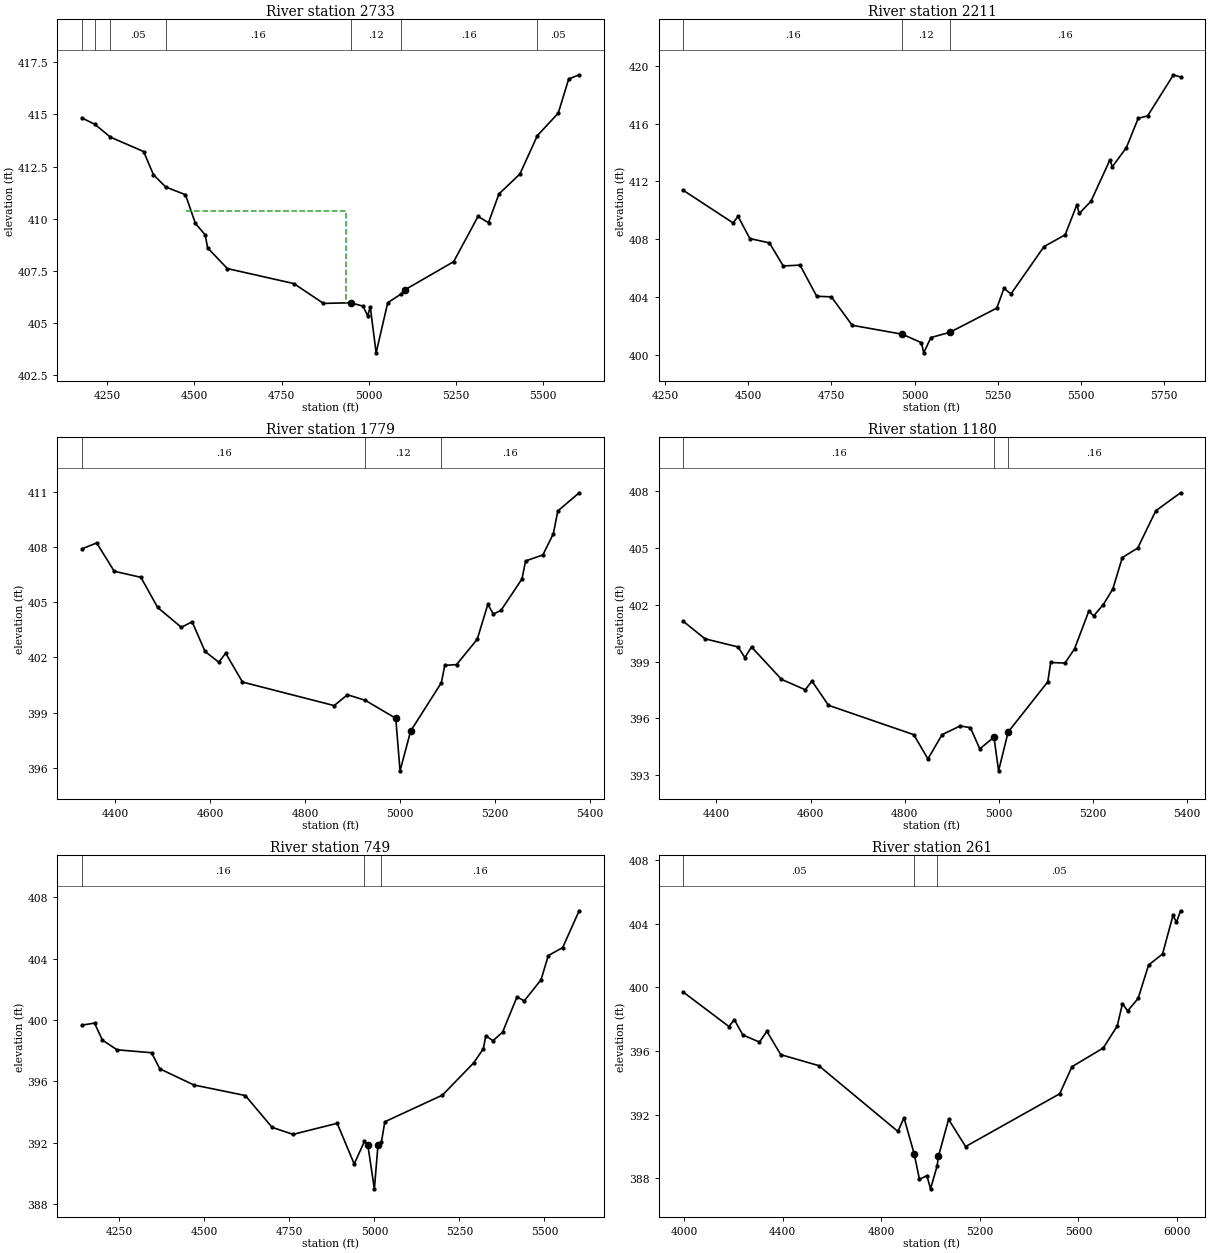
Type RM Length L Ch R = 1 ,2733    ,522,522,522
BEGIN DESCRIPTION:
UNT020 IN SUCR 5.0
END DESCRIPTION:
XS GIS Cut Line= 3
      2302787.74     13445496.83      2302211.41      13446114.7
      2302237.72     13446696.87
#Sta/Elev= 30
    4177  414.83  4214.4  414.52  4258.8  413.91  4354.1  413.22  4382.2  412.11
  4417.6  411.52  4474.3  411.15  4502.6  409.78    4531  409.22  4537.8   408.6
  4594.5  407.61  4785.5  406.89  4870.5  405.94  4948.2  405.97  4983.9  405.81
  4997.5  405.35  5004.9  405.77  5021.7  403.57    5055  405.97  5094.2   406.4
  5104.2  406.59  5244.3  407.94  5314.4  410.11  5344.4  409.81  5374.4  411.19
  5434.5  412.14  5484.6  413.98  5544.6  415.06  5574.7   416.7  5604.7   416.9
#Mann= 7 ,-1 , 0
    4177     .05       0  4214.4      .1       0  4258.8     .05       0
  4417.6     .16       0  4948.2     .12       0  5094.2     .16       0
  5484.6     .05       0
#XS Ineff= 1 ,-1
 4476.18 4936.17410.3812
Permanent Ineff=
       T
Bank Sta=4948.2,5104.2
XS Rating Curve= 0 ,0
Exp/Cntr=0.3,0.1

Type RM Length L Ch R = 1 ,2211    ,448,448,448
BEGIN DESCRIPTION:
UNT020 IN SUCR 4.0
END DESCRIPTION:
XS GIS Cut Line= 3
      2302337.72     13445496.86      2301787.72     13445896.85
      2301237.73     13446496.85
#Sta/Elev= 30
  4304.9  411.38  4454.4  409.12  4469.1  409.58  4504.7  408.04  4563.4  407.74
  4605.1  406.14  4655.4   406.2  4705.6  404.04  4749.6     404  4812.2  402.03
  4962.9  401.41  5020.4  400.82    5027  400.12  5048.8  401.18  5105.5  401.54
  5246.7  403.22  5268.3  404.59  5289.3   404.2  5388.5  407.48  5452.1   408.3
  5487.2  410.37  5494.6  409.78  5529.8  410.63  5586.5  413.48  5593.9  413.02
  5636.1  414.34  5671.6  416.37  5699.9  416.54  5777.6  419.39  5798.9  419.23
#Mann= 3 , 0 , 0
  4304.9     .16       0  4962.9     .12       0  5105.5     .16       0
Bank Sta=4962.9,5105.5
XS Rating Curve= 0 ,0
Exp/Cntr=0.3,0.1

Type RM Length L Ch R = 1 ,1779    ,599,599,599
BEGIN DESCRIPTION:
UNT020 IN SUCR 3.0
END DESCRIPTION:
XS GIS Cut Line= 4
      2301882.28      13445427.2      2301445.51     13445763.26
      2301327.84     13445964.65      2301205.65     13446196.59
#Sta/Elev= 30
  4330.3  407.91  4361.3  408.23  4398.2  406.69  4454.3  406.36  4489.6  404.72
  4539.5  403.64  4562.2  403.94  4589.3  402.33  4618.3  401.74  4632.8  402.23
  4668.2  400.66  4861.2  399.38  4889.1  399.97  4926.3  399.67  4990.8  398.69
  4999.8  395.83  5022.2     398  5086.7  400.62    5094  401.57  5118.7  401.61
  5162.3  402.99  5184.6  404.89  5196.2  404.36  5212.3  404.56  5256.4  406.27
  5264.1  407.25  5300.4  407.58  5322.5  408.73  5331.9  409.97  5376.8  410.96
#Mann= 3 ,-1 , 0
  4330.3     .16       0  4926.3     .12       0  5086.7     .16       0
Bank Sta=4990.8,5022.2
XS Rating Curve= 0 ,0
Exp/Cntr=0.3,0.1

Type RM Length L Ch R = 1 ,1180    ,431,431,431
BEGIN DESCRIPTION:
UNT020 IN SUCR 2.0
END DESCRIPTION:
XS GIS Cut Line= 4
      2301185.28     13445209.79      2300831.13     13445515.33
      2300810.29     13445820.89       2300858.9     13446098.66
#Sta/Elev= 30
  4329.7  401.12  4375.7   400.2    4446  399.77  4460.2  399.21  4474.5  399.77
  4538.1  398.06  4588.6  397.51  4602.8  397.97  4637.9  396.69    4819  395.14
  4849.1  393.86  4879.2  395.14  4917.6   395.6  4939.3  395.51  4959.3  394.39
  4989.4  395.01  4999.2  393.23  5019.5  395.28  5103.7  397.93  5109.8  398.95
  5140.2  398.92  5160.5  399.67    5191  401.67  5201.1  401.41  5221.4     402
  5241.7  402.82    5262  404.49  5294.7  404.99  5333.1  406.96  5385.7  407.91
#Mann= 3 , 0 , 0
  4329.7     .16       0  4989.4     .12       0  5019.5     .16       0
Bank Sta=4989.4,5019.5
XS Rating Curve= 0 ,0
Exp/Cntr=0.3,0.1

Type RM Length L Ch R = 1 ,749     ,488,488,488
BEGIN DESCRIPTION:
UNT020 IN SUCR 2.0
END DESCRIPTION:
XS GIS Cut Line= 4
      2300953.74     13445156.98      2300408.61     13445372.26
      2300408.61     13445799.34      2300720.94     13446122.08
#Sta/Elev= 30
  4139.8  399.67  4176.7   399.8    4200  398.69    4243  398.06  4344.4  397.87
  4368.8  396.82  4468.8  395.77  4620.3  395.08  4698.8  393.01  4760.5  392.55
  4890.5  393.27  4940.5  390.62  4970.5  392.09  4980.5  391.86  4999.8     389
  5010.5  391.86  5020.5  392.03  5030.5  393.37  5200.1  395.11    5292  397.21
  5320.3  398.13  5327.5  398.98  5348.6  398.65  5376.9  399.21  5419.3  401.51
  5440.6  401.25    5490  402.62  5511.3   404.2  5553.6  404.72  5602.1  407.12
#Mann= 3 ,-1 , 0
  4139.8     .16       0  4970.5     .12       0  5020.5     .16       0
Bank Sta=4980.5,5010.5
XS Rating Curve= 0 ,0
Exp/Cntr=0.3,0.1

Type RM Length L Ch R = 1 ,261     ,0,0,0
BEGIN DESCRIPTION:
UNT020 IN SUCR 1.0
END DESCRIPTION:
XS GIS Cut Line= 4
      2300850.56     13445045.39      2300058.42     13445201.65
      2299982.82     13445501.98      2300615.32     13446142.66
#Sta/Elev= 30
  3996.9   399.7  4181.7  397.54  4203.7  397.97  4238.2  397.01  4305.6  396.56
  4335.7  397.24  4392.1  395.77  4546.1  395.08  4867.5  390.94  4892.2   391.8
  4933.4  389.53  4954.9  387.93    4985  388.16  4999.8  387.33  5026.2  388.75
  5031.9  389.37    5073   391.7  5142.1  389.99    5524  393.31  5573.5  395.01
  5700.7  396.19  5757.3  397.57  5778.6  398.98  5799.7  398.52  5842.2  399.31
  5884.6  401.41  5941.2   402.1  5983.6  404.53  5997.7   404.1  6014.3  404.82
#Mann= 3 ,-1 , 0
  3996.9     .05       0  4933.4     .03       0  5026.2     .05       0
Bank Sta=4933.4,5031.9
XS Rating Curve= 0 ,0
Exp/Cntr=0.3,0.1

Chan Stop Cuts=-1
Use User Specified Reach Order=0
Composite Channel Slope=5