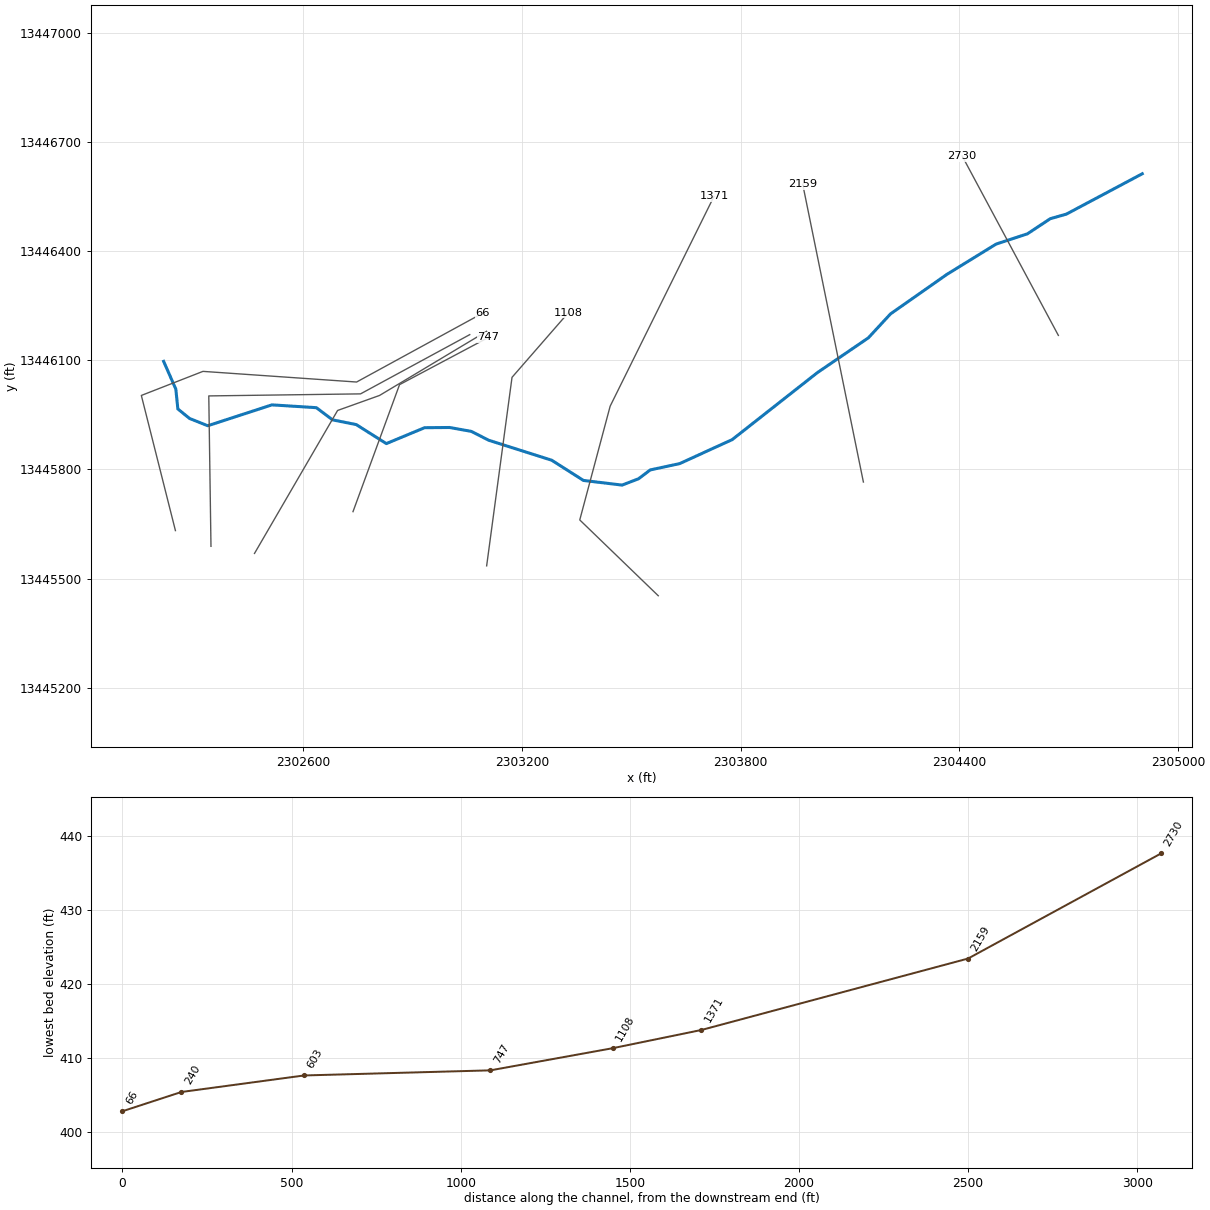
--- UNT021 IN SUCR.prj (project) ---

Proj Title=UNT021 IN SUCR Base Level Engineering
Current Plan=p01
Default Exp/Contr=0.3,0.1
English Units
Geom File=g01
Flow File=f01
Plan File=p01
Y Axis Title=Elevation
X Axis Title(PF)=Main Channel Distance
X Axis Title(XS)=Station
BEGIN DESCRIPTION:
UNT021 IN SUCR
END DESCRIPTION:
DSS Export Rating Curves= 0
DSS Export Rating Curve Sorted= 0
DSS Export Volume Flow Curves= 0
DXF OffsetX= 0
DXF OffsetY= 0
DXF ScaleX= 1
DXF ScaleY= 10

--- UNT021 IN SUCR.p01 (plan) ---

Plan Title=Multiple Run
Short Identifier=Multiple
Geom File=g01
Flow File=f01
Subcritical Flow
K Sum by GR= 0
Std Step Tol= 0.01
Critical Tol= 0.01
Num of Std Step Trials= 20
Max Error Tol= 0.3
Flow Tol Ratio= 0.001
Split Flow NTrial= 30
Split Flow Tol= 0.02
Split Flow Ratio= 0.02
Log Output Level= 0
Friction Slope Method= 1
Unsteady Friction Slope Method= 2
Unsteady Bridges Friction Slope Method= 1
Parabolic Critical Depth
Global Vel Dist=  1 , 1 , 1
Global Log Level= 0
CheckData=True
Encroach Param= -1, 0, 0, 0
BEGIN DESCRIPTION:
Multiple Run
END DESCRIPTION:

--- UNT021 IN SUCR.f01 (steady flow) ---

Flow Title=Multiple
Program Version=4.10
Number of Profiles= 7
Profile Names=10-year,25-year,50-year,1pct_min,100-year,1pct_plu,500-year
River Rch & RM=UNT021 IN SUCR,Reach-1         ,2730
     158     204     239     207     279     378     379
Boundary for River Rch & Prof#=UNT021 IN SUCR,Reach-1         , 1
Up Type= 0
Dn Type= 3
Dn Slope=0.0079
Boundary for River Rch & Prof#=UNT021 IN SUCR,Reach-1         , 2
Up Type= 0
Dn Type= 3
Dn Slope=0.0079
Boundary for River Rch & Prof#=UNT021 IN SUCR,Reach-1         , 3
Up Type= 0
Dn Type= 3
Dn Slope=0.0079
Boundary for River Rch & Prof#=UNT021 IN SUCR,Reach-1         , 4
Up Type= 0
Dn Type= 3
Dn Slope=0.0079
Boundary for River Rch & Prof#=UNT021 IN SUCR,Reach-1         , 5
Up Type= 0
Dn Type= 3
Dn Slope=0.0079
Boundary for River Rch & Prof#=UNT021 IN SUCR,Reach-1         , 6
Up Type= 0
Dn Type= 3
Dn Slope=0.0079
Boundary for River Rch & Prof#=UNT021 IN SUCR,Reach-1         , 7
Up Type= 0
Dn Type= 3
Dn Slope=0.0079
DSS Import GetInterval= 0
DSS Import GetPeak= 0
DSS Import FillOption= 0

--- UNT021 IN SUCR.g01 (geometry) ---

Geom Title=Existing Conditions
Program Version=4.10

River Reach=UNT021 IN SUCR  ,Reach-1
Reach XY= 30
      2304901.43     13446612.24      2304693.36     13446501.35
      2304649.26     13446488.85      2304586.42     13446447.18
      2304500.65     13446419.06      2304365.58     13446335.72
      2304210.97     13446227.14       2304150.3     13446161.41
      2304010.54     13446065.92      2303777.03     13445881.89
      2303632.93     13445815.92       2303552.2     13445798.56
      2303520.09     13445774.26      2303474.95      13445756.9
      2303368.95     13445769.68      2303282.03     13445825.19
      2303109.09     13445880.16       2303061.7      13445904.4
      2303002.17     13445915.13      2302933.43     13445914.58
       2302828.5     13445870.88      2302746.05     13445923.06
      2302680.84     13445936.15      2302636.68     13445969.59
      2302514.64     13445977.26       2302338.8     13445919.95
      2302288.88     13445939.91      2302256.73     13445966.11
       2302251.2     13446020.56      2302217.72     13446096.86

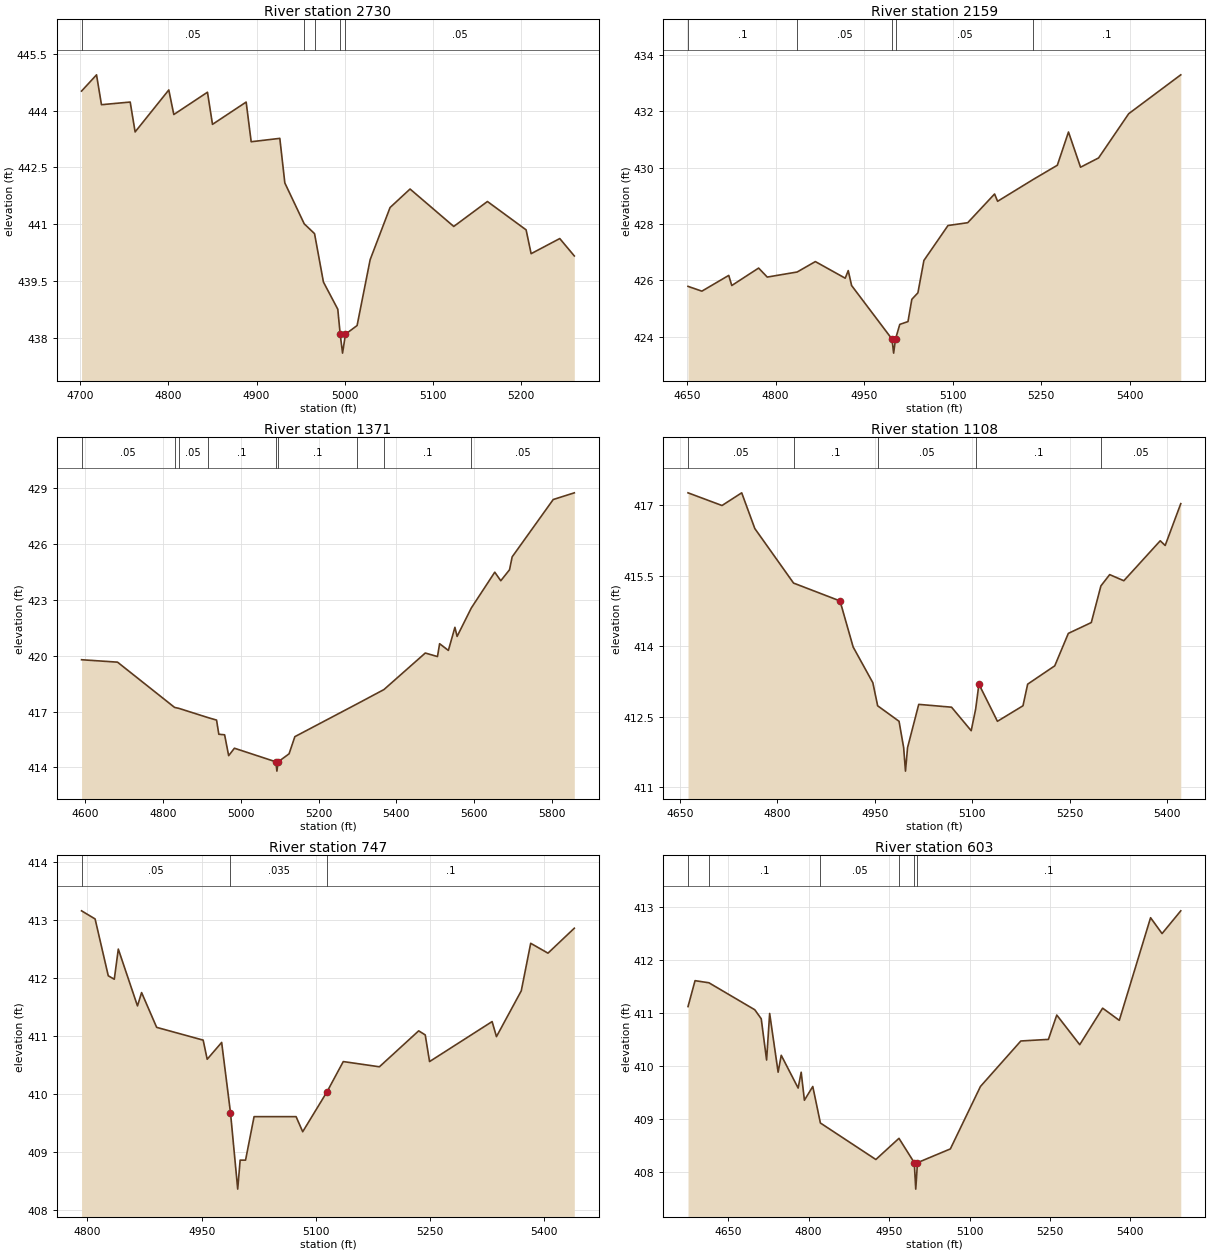
Type RM Length L Ch R = 1 ,2730    ,571,571,571
BEGIN DESCRIPTION:
UNT021 IN SUCR 2.0
END DESCRIPTION:
XS GIS Cut Line= 2
      2304671.38     13446168.15      2304407.51     13446661.17
#Sta/Elev= 30
  4701.4  444.52  4718.4  444.95    4724  444.16  4756.6  444.23  4762.2  443.44
  4800.4  444.55  4806.1   443.9  4844.3  444.49    4850  443.64  4888.2  444.23
  4893.9  443.18  4926.4  443.27  4932.1  442.09  4954.1  441.01  4965.8  440.75
  4975.9  439.47  4992.2  438.75  4994.9  438.09  4997.6  437.59  5000.9  438.09
  5014.1  438.32  5028.9  440.06  5051.5  441.44  5074.2  441.93  5123.8  440.94
    5162   441.6  5205.9  440.85  5211.6  440.22  5244.1  440.62  5260.6  440.16
#Mann= 5 ,-1 , 0
  4701.4     .05       0  4954.1      .1       0  4965.8     .05       0
  4994.9    .035       0  5000.9     .05       0
Bank Sta=4994.9,5000.9
XS Rating Curve= 0 ,0
Exp/Cntr=0.3,0.1

Type RM Length L Ch R = 1 ,2159    ,788,788,788
BEGIN DESCRIPTION:
Mapping XS f5541c8a
END DESCRIPTION:
XS GIS Cut Line= 2
      2304136.69     13445765.32      2303970.32     13446583.27
#Sta/Elev= 30
  4651.5  425.79    4675  425.62  4720.5  426.18  4725.6  425.82  4771.1  426.44
  4785.7  426.12  4836.4   426.3  4867.2  426.67  4917.8  426.08  4922.9  426.35
  4928.6  425.82    4997  423.92  4999.8  423.42    5003  423.92  5010.2  424.44
  5024.1  424.54  5030.6  425.33  5040.9  425.56  5051.1  426.71  5091.9  427.95
  5125.3  428.05  5170.8  429.07  5175.9  428.81  5236.6  429.59  5277.1  430.09
    5296  431.27  5316.4  430.02    5347  430.35    5398  431.92  5486.2   433.3
#Mann= 5 ,-1 , 0
  4651.5      .1       0  4836.4     .05       0    4997    .035       0
    5003     .05       0  5236.6      .1       0
Bank Sta=4997,5003
XS Rating Curve= 0 ,0
Exp/Cntr=0.3,0.1

Type RM Length L Ch R = 1 ,1371    ,263,263,263
BEGIN DESCRIPTION:
Mapping XS a6609f851
END DESCRIPTION:
XS GIS Cut Line= 4
      2303574.15     13445452.86       2303358.9     13445661.16
      2303442.24     13445973.66      2303726.95     13446550.02
#Sta/Elev= 30
  4591.2  419.78  4683.6  419.65  4830.2  417.22  4841.2  417.17    4915  416.68
    4938  416.54  4943.8  415.78  4958.7  415.75  4969.1  414.63  4983.9  415.03
  5090.3   414.3    5093   413.8  5096.3   414.3  5124.3  414.73  5139.1  415.65
  5299.9  417.42  5368.1  418.18  5474.2  420.14  5505.5  419.95    5511  420.64
  5533.5  420.28  5550.3  421.52  5555.9  421.03  5592.5  422.56  5652.7  424.48
  5668.1  424.02  5690.6  424.61  5697.3   425.3  5802.8  428.38    5857  428.74
#Mann= 9 ,-1 , 0
  4591.2     .05       0  4830.2      .1       0  4841.2     .05       0
    4915      .1       0  5090.3     .07       0  5096.3      .1       0
  5299.9     .05       0  5368.1      .1       0  5592.5     .05       0
Bank Sta=5090.3,5096.3
XS Rating Curve= 0 ,0
Exp/Cntr=0.3,0.1

Type RM Length L Ch R = 1 ,1108    ,361,361,361
BEGIN DESCRIPTION:
Mapping XS cea65b27
END DESCRIPTION:
XS GIS Cut Line= 3
      2303103.56     13445535.01      2303173.14     13446052.93
      2303327.75     13446230.74
#Sta/Elev= 30
  4662.5  417.26  4714.8  416.99  4745.1  417.26  4765.3   416.5  4824.9  415.34
  4896.4  414.96  4916.6  413.98  4946.9  413.22  4954.3  412.73  4987.2   412.4
  4994.3  411.84  4997.1  411.34  5000.3  411.84  5017.5  412.76    5068   412.7
  5098.2   412.2  5105.1  412.66  5110.1  413.19  5138.6   412.4  5177.9  412.73
  5185.1  413.19  5226.8  413.58  5247.7  414.27    5283   414.5  5297.8  415.28
  5311.3  415.52  5333.1  415.39  5389.1  416.24  5396.7  416.14  5420.7  417.03
#Mann= 5 ,-1 , 0
  4662.5     .05       0  4824.9      .1       0  4954.3     .05       0
  5105.1      .1       0  5297.8     .05       0
Bank Sta=4896.4,5110.1
XS Rating Curve= 0 ,0
Exp/Cntr=0.3,0.1

Type RM Length L Ch R = 1 ,747     ,551,551,551
BEGIN DESCRIPTION:
Mapping XS a6609f85
END DESCRIPTION:
XS GIS Cut Line= 3
      2302737.06     13445683.91      2302864.67     13446032.87
      2303108.28     13446162.45
#Sta/Elev= 30
  4792.2  413.16    4810  413.02  4827.3  412.04  4835.2  411.98  4840.5   412.5
  4865.7  411.52  4871.1  411.75  4890.9  411.15    4952  410.93  4957.3   410.6
  4976.3  410.89  4987.9  409.68  4997.4  408.36  5000.6  408.86  5007.7  408.86
  5018.9  409.61  5074.1  409.61  5082.8  409.35  5114.8  410.04  5136.1  410.56
  5183.6  410.47  5235.2  411.09  5243.8  411.02  5249.5  410.56  5331.7  411.25
  5337.4  410.99    5370  411.78  5382.4   412.6  5405.1  412.43  5439.7  412.86
#Mann= 3 , 0 , 0
  4792.2     .05       0  4987.9    .035       0  5114.8      .1       0
Bank Sta=4987.9,5114.8
XS Rating Curve= 0 ,0
Exp/Cntr=0.3,0.1

Type RM Length L Ch R = 1 ,603     ,363,363,363
BEGIN DESCRIPTION:
UNT021 IN SUCR 1.2
END DESCRIPTION:
XS GIS Cut Line= 4
      2302466.93     13445569.12       2302694.8     13445961.93
      2302809.82     13446003.17      2303103.38     13446179.39
#Sta/Elev= 30
  4575.2  411.12  4588.3  411.61  4614.2  411.57  4699.7  411.06  4711.7  410.89
  4721.7  410.11  4727.4  410.99  4743.2  409.88    4749   410.2  4780.5  409.58
  4786.2  409.88  4792.2  409.35  4807.8  409.61    4822  408.92  4925.4  408.23
  4968.5  408.63    4997  408.17  4999.8  407.67    5003  408.17  5064.3  408.43
  5120.4  409.61  5195.7  410.47  5247.1   410.5  5262.7  410.96  5305.5   410.4
  5348.2  411.09  5379.3  410.86  5437.6   412.8    5459   412.5  5493.9  412.93
#Mann= 6 ,-1 , 0
  4575.2     .05       0  4614.2      .1       0    4822     .05       0
  4968.5      .1       0    4997     .07       0    5003      .1       0
Bank Sta=4997,5003
XS Rating Curve= 0 ,0
Exp/Cntr=0.3,0.1

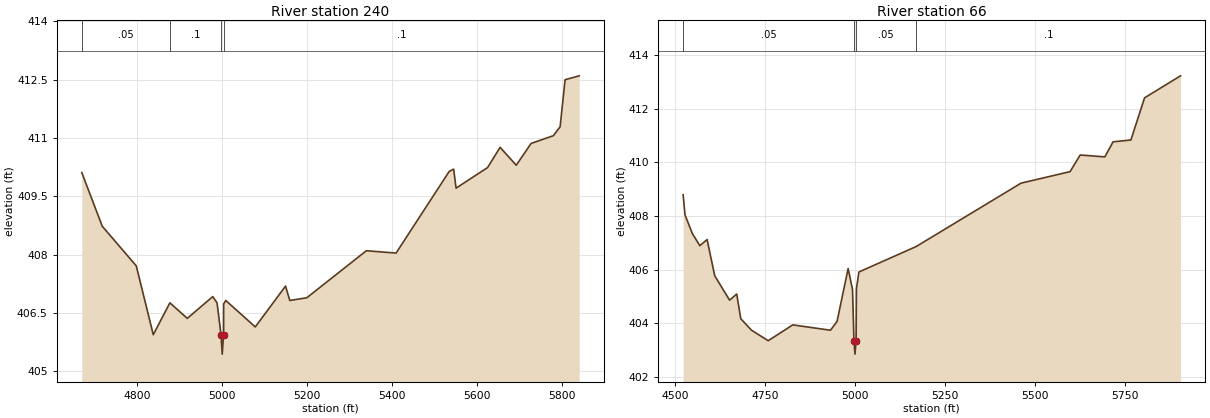
Type RM Length L Ch R = 1 ,240     ,174,174,174
BEGIN DESCRIPTION:
UNT021 IN SUCR 1.1
END DESCRIPTION:
XS GIS Cut Line= 4
      2302347.58     13445588.66      2302341.57      13446001.9
      2302757.74     13446007.51      2303057.18     13446170.25
#Sta/Elev= 30
  4669.4  410.11  4717.6  408.73  4797.6  407.71  4837.6  405.94  4876.7  406.76
  4917.6  406.36  4977.6  406.92  4987.6  406.76    4997  405.94  4999.8  405.44
    5003  405.94  5003.2  406.73  5008.2  406.82  5077.6  406.14  5148.8  407.19
  5158.8  406.82  5198.8  406.89  5338.9   408.1  5408.9  408.04  5533.8  410.14
  5544.3   410.2    5550  409.71  5624.1  410.24  5653.6  410.76  5691.6   410.3
  5726.5  410.86    5779  411.06  5794.8  411.29  5806.5   412.5  5839.7   412.6
#Mann= 4 ,-1 , 0
  4669.4     .05       0  4876.7      .1       0    4997     .07       0
    5003      .1       0
Bank Sta=4997,5003
XS Rating Curve= 0 ,0
Exp/Cntr=0.3,0.1

Type RM Length L Ch R = 1 ,66      ,0,0,0
BEGIN DESCRIPTION:
UNT021 IN SUCR 1.0
END DESCRIPTION:
XS GIS Cut Line= 5
      2302250.09     13445631.83      2302156.61     13446003.17
      2302325.61     13446069.33      2302746.89     13446040.06
      2303091.91     13446228.85
#Sta/Elev= 30
  4523.1  408.79  4528.3  408.04  4548.5  407.35  4569.5  406.89  4589.6  407.12
  4610.8  405.77    4652  404.86  4671.8  405.09    4683  404.17  4712.9  403.74
  4759.2  403.35  4827.3  403.94    4932  403.74  4950.2  404.07  4980.9  406.04
  4993.1  405.25    4997  403.35  4999.8  402.85    5003  403.35  5003.9  405.28
  5010.7  405.91  5169.8  406.86  5460.5  409.22  5596.6  409.65  5624.7  410.27
  5693.1   410.2  5715.9  410.76  5765.4  410.83  5803.3   412.4  5903.1  413.22
#Mann= 4 ,-1 , 0
  4523.1     .05       0    4997     .03       0    5003     .05       0
  5169.8      .1       0
Bank Sta=4997,5003
XS Rating Curve= 0 ,0
Exp/Cntr=0.3,0.1

Chan Stop Cuts=-1
Use User Specified Reach Order=0
Composite Channel Slope=5