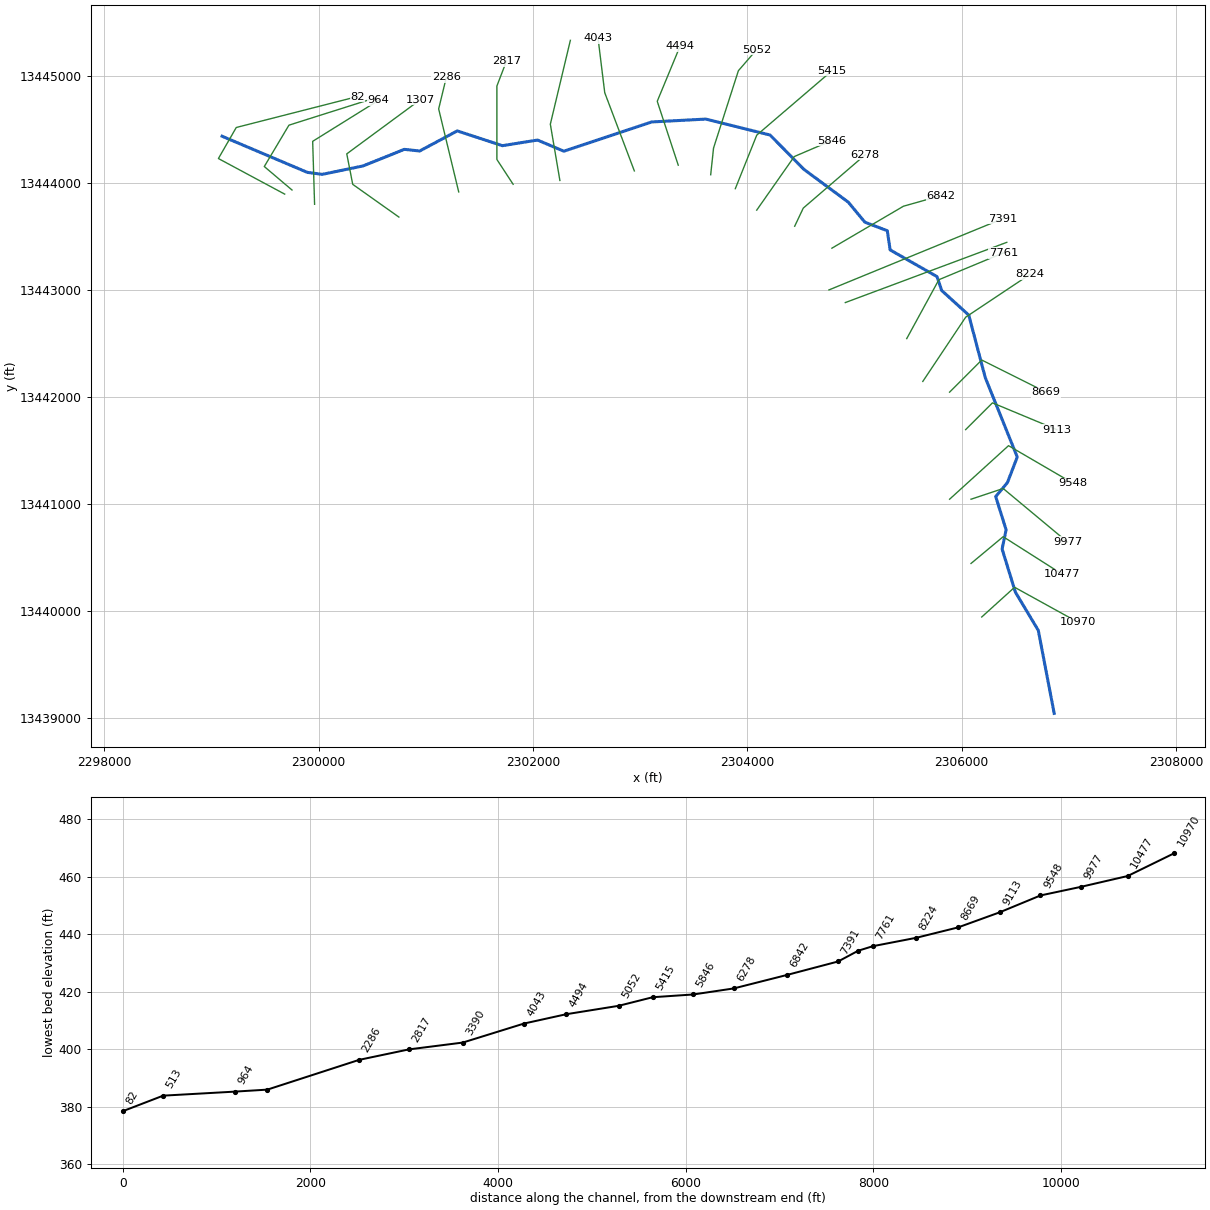
--- UNT022 IN SUCR.prj (project) ---

Proj Title=UNT022 IN SUCR Base Level Engineering
Current Plan=p01
Default Exp/Contr=0.3,0.1
English Units
Geom File=g01
Flow File=f01
Plan File=p01
Y Axis Title=Elevation
X Axis Title(PF)=Main Channel Distance
X Axis Title(XS)=Station
BEGIN DESCRIPTION:
UNT022 IN SUCR
END DESCRIPTION:
DSS Export Rating Curves= 0
DSS Export Rating Curve Sorted= 0
DSS Export Volume Flow Curves= 0
DXF OffsetX= 0
DXF OffsetY= 0
DXF ScaleX= 1
DXF ScaleY= 10

--- UNT022 IN SUCR.p01 (plan) ---

Plan Title=Multiple Run
Short Identifier=Multiple
Geom File=g01
Flow File=f01
Subcritical Flow
K Sum by GR= 0
Std Step Tol= 0.01
Critical Tol= 0.01
Num of Std Step Trials= 20
Max Error Tol= 0.3
Flow Tol Ratio= 0.001
Split Flow NTrial= 30
Split Flow Tol= 0.02
Split Flow Ratio= 0.02
Log Output Level= 0
Friction Slope Method= 1
Unsteady Friction Slope Method= 2
Unsteady Bridges Friction Slope Method= 1
Parabolic Critical Depth
Global Vel Dist=  1 , 1 , 1
Global Log Level= 0
CheckData=True
Encroach Param= -1, 0, 0, 0
BEGIN DESCRIPTION:
Multiple Run
END DESCRIPTION:

--- UNT022 IN SUCR.f01 (steady flow) ---

Flow Title=Multiple
Program Version=4.10
Number of Profiles= 7
Profile Names=10-year,25-year,50-year,1pct_min,100-year,1pct_plu,500-year
River Rch & RM=UNT022 IN SUCR,Reach-1         ,10970
     568     797     989     897    1212    1640    1829
River Rch & RM=UNT022 IN SUCR,Reach-1         ,7391
     744    1059    1325    1210    1636    2213    2506
Boundary for River Rch & Prof#=UNT022 IN SUCR,Reach-1         , 1
Up Type= 0
Dn Type= 3
Dn Slope=0.01
Boundary for River Rch & Prof#=UNT022 IN SUCR,Reach-1         , 2
Up Type= 0
Dn Type= 3
Dn Slope=0.01
Boundary for River Rch & Prof#=UNT022 IN SUCR,Reach-1         , 3
Up Type= 0
Dn Type= 3
Dn Slope=0.01
Boundary for River Rch & Prof#=UNT022 IN SUCR,Reach-1         , 4
Up Type= 0
Dn Type= 3
Dn Slope=0.01
Boundary for River Rch & Prof#=UNT022 IN SUCR,Reach-1         , 5
Up Type= 0
Dn Type= 3
Dn Slope=0.01
Boundary for River Rch & Prof#=UNT022 IN SUCR,Reach-1         , 6
Up Type= 0
Dn Type= 3
Dn Slope=0.01
Boundary for River Rch & Prof#=UNT022 IN SUCR,Reach-1         , 7
Up Type= 0
Dn Type= 3
Dn Slope=0.01
DSS Import GetInterval= 0
DSS Import GetPeak= 0
DSS Import FillOption= 0

--- UNT022 IN SUCR.g01 (geometry) ---

Geom Title=Existing Conditions
Program Version=4.10

River Reach=UNT022 IN SUCR  ,Reach-1
Reach XY= 30
      2306863.83     13439046.72      2306715.54     13439821.58
      2306501.76     13440178.61      2306377.72     13440581.88
      2306415.11     13440761.32       2306317.9     13441071.61
      2306427.56     13441201.92      2306519.15     13441440.85
      2306220.25     13442183.82       2306066.7     13442766.01
      2305814.03     13442996.12      2305770.32      13443125.7
      2305332.92     13443374.98      2305306.25     13443554.17
      2305096.76     13443634.24      2304942.14     13443821.22
      2304527.36     13444127.86      2304211.74     13444448.27
      2303612.65     13444597.03      2303107.32     13444570.14
      2302287.52     13444297.06       2302041.7     13444401.15
      2301713.56     13444348.59      2301292.96     13444486.62
      2300941.87      13444298.9      2300798.93     13444314.23
      2300411.73     13444159.01      2300032.67      13444080.8
      2299894.04     13444099.21      2299097.72     13444436.86

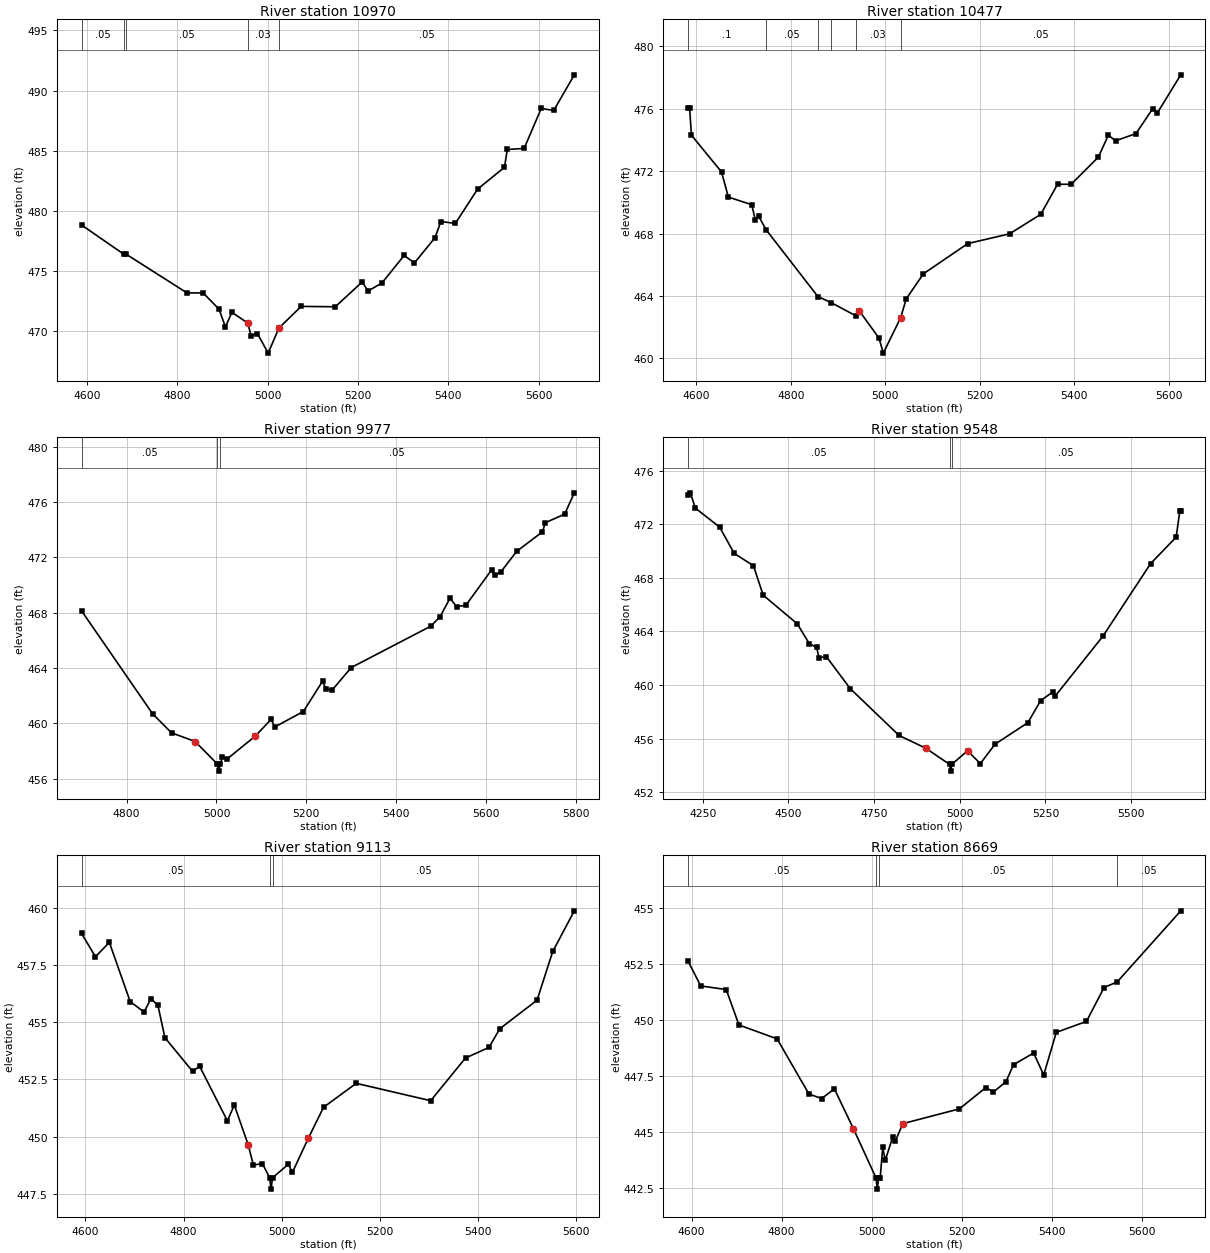
Type RM Length L Ch R = 1 ,10970   ,493,493,493
BEGIN DESCRIPTION:
UNT022 IN SUCR 17.0
END DESCRIPTION:
XS GIS Cut Line= 3
      2306187.71     13439946.85      2306494.24     13440224.46
      2307087.68     13439896.88
#Sta/Elev= 30
  4587.5  478.84  4681.2  476.41  4686.5  476.41    4821   473.2  4856.8   473.2
    4892  471.85  4906.2  470.37  4920.4  471.59  4955.5   470.7    4963  469.65
  4977.1  469.82  5000.8   468.2  5024.6  470.28  5073.9  472.08  5149.5  472.05
  5209.1  474.11    5222  473.36  5252.7  474.02    5302  476.31  5324.8  475.69
  5370.5  477.79  5383.3  479.13  5415.4  478.97  5464.7  481.82  5524.2  483.63
  5530.5  485.11  5567.8   485.2  5605.6  488.52  5633.3  488.35  5678.9  491.31
#Mann= 5 ,-1 , 0
  4587.5     .05       0  4681.2      .1       0  4686.5     .05       0
  4955.5     .03       0  5024.6     .05       0
Bank Sta=4955.5,5024.6
XS Rating Curve= 0 ,0
Exp/Cntr=0.3,0.1

Type RM Length L Ch R = 1 ,10477   ,500,500,500
BEGIN DESCRIPTION:
UNT022 IN SUCR 16.0
END DESCRIPTION:
XS GIS Cut Line= 3
      2306087.72     13440446.85      2306387.72     13440696.85
      2306937.69     13440346.88
#Sta/Elev= 30
  4582.6  476.08  4585.9  476.08  4589.8  474.31  4653.5  471.95  4667.9  470.34
  4717.3  469.85  4725.1  468.86  4731.7  469.13  4747.6  468.25  4857.3  463.96
  4885.4  463.57  4937.3  462.73  4945.1  463.03  4986.7  461.29  4995.7  460.33
  5032.4   462.6  5044.2  463.81  5080.6  465.42  5174.6  467.36  5262.7  467.98
  5328.7  469.23  5364.3  471.16  5393.1  471.16  5450.6   472.9  5471.8  474.31
    5487  473.95  5530.2  474.41  5565.8  476.02  5575.1  475.72    5625  478.18
#Mann= 6 ,-1 , 0
  4582.6      .1       0  4747.6     .05       0  4857.3      .1       0
  4885.4     .05       0  4937.3     .03       0  5032.4     .05       0
Bank Sta=4945.1,5032.4
XS Rating Curve= 0 ,0
Exp/Cntr=0.3,0.1

Type RM Length L Ch R = 1 ,9977    ,429,429,429
BEGIN DESCRIPTION:
UNT022 IN SUCR 15.0
END DESCRIPTION:
XS GIS Cut Line= 3
      2306087.72     13441046.86      2306387.72     13441146.85
      2306987.76     13440646.82
#Sta/Elev= 30
  4699.6  468.14  4857.7   460.7  4899.9  459.32  4952.6  458.69  5002.3  457.05
    5005  456.55  5008.3  457.05  5013.2  457.55    5023  457.41  5086.8  459.09
  5121.9   460.3  5129.7  459.74  5193.5  460.86  5236.5  463.06    5243   462.5
  5257.3   462.4  5300.2  464.04  5477.3  467.03  5498.1  467.72  5520.2  469.06
  5534.6  468.44  5555.4  468.54  5612.7   471.1  5619.2   470.7  5633.5  470.96
  5668.6  472.44  5725.9  473.85  5732.4  474.51  5775.4  475.13  5796.9  476.67
#Mann= 3 ,-1 , 0
  4699.6     .05       0  5002.3     .03       0  5008.3     .05       0
Bank Sta=4952.6,5086.8
XS Rating Curve= 0 ,0
Exp/Cntr=0.3,0.1

Type RM Length L Ch R = 1 ,9548    ,435,435,435
BEGIN DESCRIPTION:
UNT022 IN SUCR 14.0
END DESCRIPTION:
XS GIS Cut Line= 3
       2305887.7     13441046.84      2306437.72     13441546.85
      2307037.68     13441196.88
#Sta/Elev= 30
  4207.1  474.15  4214.2  474.34  4228.4   473.2  4299.4  471.78  4341.9  469.82
    4398   468.9  4426.4   466.7  4525.7  464.57  4560.9  463.09  4582.5   462.8
  4589.2  462.04  4610.9  462.11  4681.1  459.71  4823.1  456.23  4900.8  455.28
  4970.6  454.07  4973.3  453.57  4976.6  454.07  5022.8  455.09    5060  454.13
    5103  455.58  5198.9  457.19  5236.1  458.83  5273.3  459.51  5279.1  459.19
  5418.1  463.65    5557  469.06  5631.4  471.03  5642.2  472.97    5645  472.97
#Mann= 3 ,-1 , 0
  4207.1     .05       0  4970.6     .03       0  4976.6     .05       0
Bank Sta=4900.8,5022.8
XS Rating Curve= 0 ,0
Exp/Cntr=0.3,0.1

Type RM Length L Ch R = 1 ,9113    ,444,444,444
BEGIN DESCRIPTION:
UNT022 IN SUCR 13.0
END DESCRIPTION:
XS GIS Cut Line= 3
      2306037.71     13441696.85      2306287.72     13441946.85
      2306887.76     13441696.84
#Sta/Elev= 30
  4592.3  458.89  4620.6  457.87  4648.9   458.5  4691.3  455.91  4719.6  455.45
  4733.7  456.04  4747.9  455.74    4762  454.33  4818.6  452.85  4832.7  453.08
  4889.3  450.69  4903.4  451.38  4931.7  449.64  4942.3  448.75  4960.5  448.82
  4975.4   448.2  4978.1   447.7  4981.4   448.2  5013.6  448.79  5021.7  448.43
  5054.2  449.93  5085.1  451.28  5151.7  452.33  5303.4  451.57  5374.3  453.44
    5422   453.9  5444.2  454.72    5520  455.97    5552   458.1  5595.9  459.88
#Mann= 3 ,-1 , 0
  4592.3     .05       0  4975.4     .03       0  4981.4     .05       0
Bank Sta=4931.7,5054.2
XS Rating Curve= 0 ,0
Exp/Cntr=0.3,0.1

Type RM Length L Ch R = 1 ,8669    ,445,445,445
BEGIN DESCRIPTION:
UNT022 IN SUCR 12.0
END DESCRIPTION:
XS GIS Cut Line= 3
       2305887.7     13442046.83      2306187.72     13442346.85
       2306787.7     13442046.86
#Sta/Elev= 30
  4592.1  452.62  4620.4  451.51    4677  451.35  4705.3  449.77  4790.1  449.15
  4860.8  446.69  4889.1  446.49  4917.4  446.92  4959.8  445.14  5009.9  442.95
  5012.6  442.45  5015.9  442.95  5019.2  442.95  5024.8  444.32  5030.4  443.73
  5047.1  444.78  5052.7  444.59  5069.5  445.37  5195.3  446.03    5254  446.98
  5270.8  446.78  5298.7  447.24  5315.5     448  5360.2  448.52  5382.6  447.54
  5410.5  449.44  5477.6  449.93  5516.7  451.44  5545.9  451.69  5687.2  454.86
#Mann= 4 ,-1 , 0
  4592.1     .05       0  5009.9     .03       0  5015.9     .05       0
  5545.9     .05       0
Bank Sta=4959.8,5069.5
XS Rating Curve= 0 ,0
Exp/Cntr=0.3,0.1

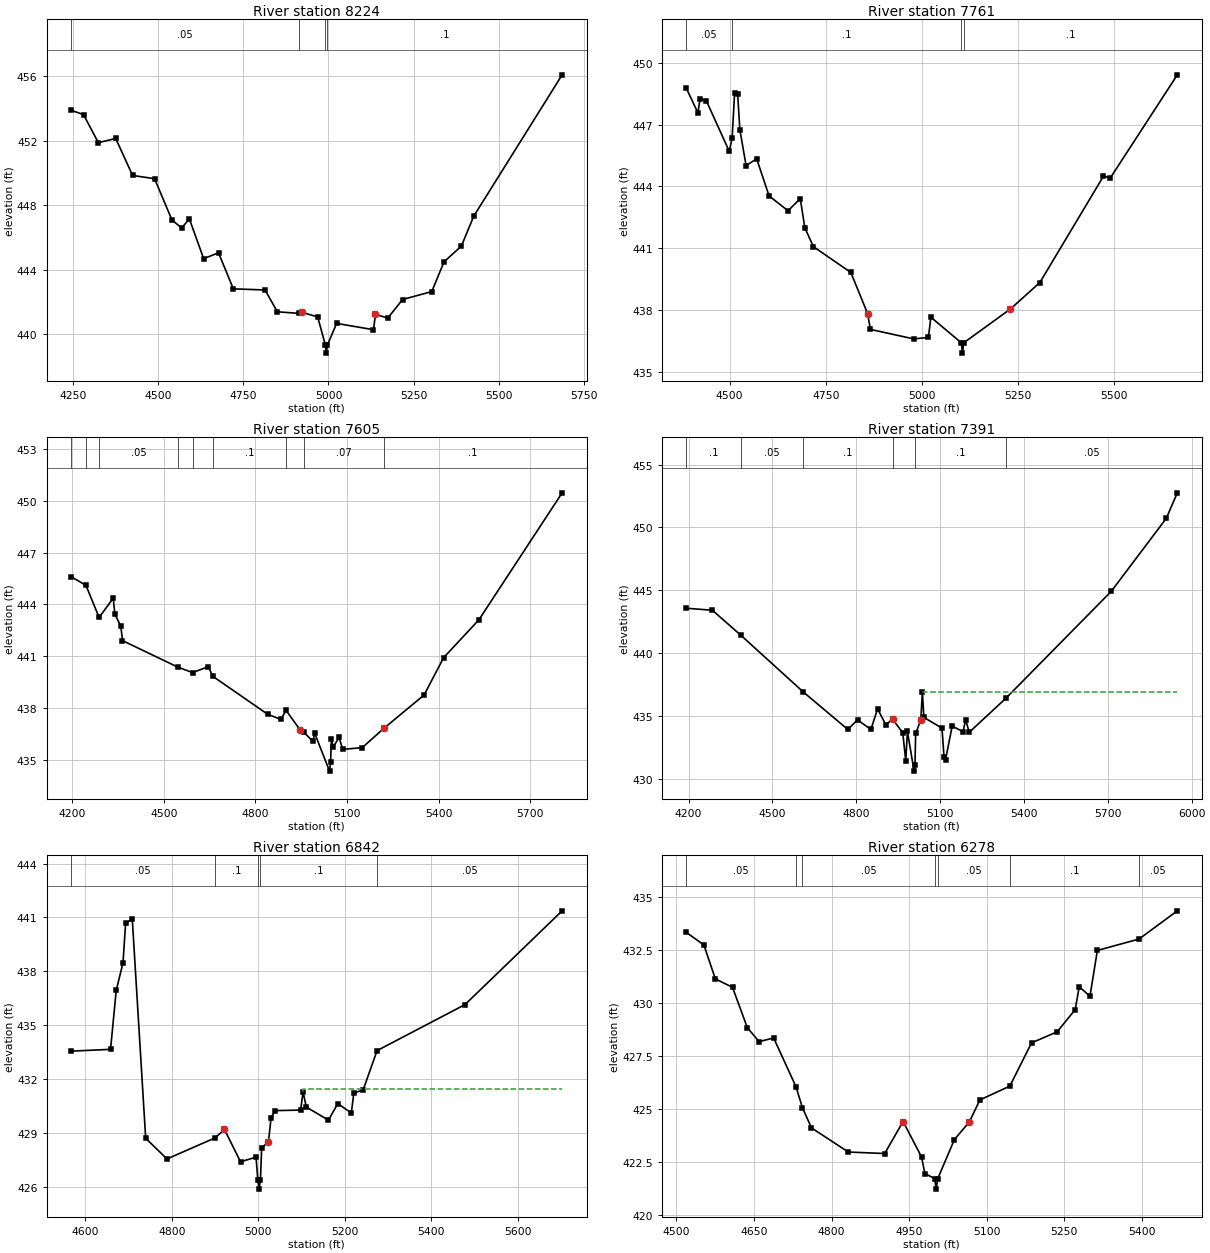
Type RM Length L Ch R = 1 ,8224    ,463,463,463
BEGIN DESCRIPTION:
UNT022 IN SUCR 11.0
END DESCRIPTION:
XS GIS Cut Line= 3
       2305637.7     13442146.83      2306037.72     13442746.85
      2306637.68     13443146.83
#Sta/Elev= 30
  4244.2  453.87  4280.3  453.61  4323.9  451.87  4374.9  452.13  4424.5  449.84
  4489.1  449.64  4540.2  447.08  4568.7  446.59  4591.3  447.15  4633.3  444.69
  4676.9  445.05  4720.5  442.82  4813.6  442.75  4849.7   441.4  4912.9   441.3
  4921.8  441.37  4968.3  441.08  4990.9  439.34  4993.6  438.84  4996.9  439.34
  5023.9  440.68  5132.1  440.29  5138.1  441.24  5174.2  441.01  5217.7  442.16
  5303.4  442.65  5339.4  444.49  5390.5  445.47  5426.5  447.31  5686.4  456.07
#Mann= 4 ,-1 , 0
  4244.2     .05       0  4912.9      .1       0  4990.9     .07       0
  4996.9      .1       0
Bank Sta=4921.8,5138.1
XS Rating Curve= 0 ,0
Exp/Cntr=0.3,0.1

Type RM Length L Ch R = 1 ,7761    ,156,156,156
BEGIN DESCRIPTION:
UNT022 IN SUCR 10.0
END DESCRIPTION:
XS GIS Cut Line= 3
      2305487.73     13442546.88      2305787.72     13443096.85
      2306387.75     13443346.87
#Sta/Elev= 30
  4387.5  448.75  4417.4  447.57  4423.1  448.26  4439.2  448.16    4499   445.7
  4506.4  446.35  4512.8  448.52  4520.8  448.46  4526.5  446.75  4542.7  445.01
  4570.2  445.34  4602.5  443.54  4651.8  442.82  4683.6  443.41  4695.5  441.99
  4717.8  441.08  4815.1  439.83  4858.8  437.83  4865.9  437.07  4978.4  436.61
  5016.7  436.68  5023.2  437.66  5102.5  436.42  5105.3  435.92  5108.5  436.42
  5230.1  438.06  5306.5  439.34  5471.7  444.49  5490.1  444.42    5664  449.41
#Mann= 4 ,-1 , 0
  4387.5     .05       0  4506.4      .1       0  5102.5     .07       0
  5108.5      .1       0
Bank Sta=4858.8,5230.1
XS Rating Curve= 0 ,0
Exp/Cntr=0.3,0.1

Type RM Length L Ch R = 1 ,7605    ,214,214,214
BEGIN DESCRIPTION:
Mapping XS 422c7378
END DESCRIPTION:
XS GIS Cut Line= 2
       2304914.5      13442883.4      2306421.44      13443445.9
#Sta/Elev= 30
  4196.4   445.6  4244.7   445.1  4287.8  443.24  4334.1  444.36  4339.4  443.44
  4359.1  442.72  4364.4   441.9  4547.3  440.35  4594.1  440.05  4646.2  440.39
  4659.7  439.84  4840.3  437.63  4883.3  437.34  4900.4  437.86    4947  436.71
  4957.7  436.61  4988.5  436.06  4993.8  436.55  5042.8  434.34  5046.1  434.84
  5049.1  436.22  5054.5  435.73  5074.1  436.29  5085.8   435.6  5149.8   435.7
  5220.3  436.81  5352.6  438.75  5416.5  440.91  5532.4  443.11  5804.9  450.46
#Mann= 9 ,-1 , 0
  4196.4     .05       0  4244.7      .1       0  4287.8     .05       0
  4547.3      .1       0  4594.1     .08       0  4659.7      .1       0
  4900.4     .08       0  4957.7     .07       0  5220.3      .1       0
Bank Sta=4947,5220.3
XS Rating Curve= 0 ,0
Exp/Cntr=0.3,0.1

Type RM Length L Ch R = 1 ,7391    ,549,549,549
BEGIN DESCRIPTION:
UNT022 IN SUCR 9.0
END DESCRIPTION:
XS GIS Cut Line= 2
      2304761.67     13443001.44      2306386.64     13443668.09
#Sta/Elev= 30
  4192.4  443.57  4285.4  443.41  4387.2  441.42  4610.7   436.9  4769.8  433.92
  4804.6  434.68  4852.5  433.92  4876.5  435.56  4905.9  434.28  4929.9  434.74
  4966.4  433.66  4977.2  431.43  4983.2  433.76    5007   430.6  5010.2   431.1
  5012.6   433.6  5031.2  434.68  5036.6  436.94    5042  434.88  5106.9  434.02
    5114  431.76  5119.4   431.5  5143.3  434.19  5182.5  433.73  5191.3  434.71
  5204.2  433.69  5335.8  436.41  5712.2  444.91  5909.1  450.72  5948.8  452.76
#Mann= 6 ,-1 , 0
  4192.4      .1       0  4387.2     .05       0  4610.7      .1       0
  4929.9     .07       0  5010.2      .1       0  5335.8     .05       0
#XS Ineff= 2 , 0
                         5036.65          436.93
Permanent Ineff=
       T       T
Bank Sta=4929.9,5031.2
XS Rating Curve= 0 ,0
Exp/Cntr=0.3,0.1

Type RM Length L Ch R = 1 ,6842    ,564,564,564
BEGIN DESCRIPTION:
UNT022 IN SUCR 8.0
END DESCRIPTION:
XS GIS Cut Line= 3
      2304789.32     13443391.41      2305457.41     13443783.35
      2305803.82     13443881.06
#Sta/Elev= 30
  4567.7  433.56  4658.6  433.66  4671.7  436.94  4687.4  438.48  4693.4  440.68
  4708.8  440.91  4739.8  428.71    4789  427.56    4900  428.73  4921.9   429.2
    4959   427.4  4994.8  427.66    4999  426.38  5001.7  425.88    5005  426.38
  5007.8  428.18  5023.5  428.51  5029.6  429.86  5039.1  430.25  5097.8  430.28
  5103.6   431.3  5110.8  430.45  5162.2  429.72  5183.7  430.64    5215  430.12
  5220.8  431.23  5242.3   431.4  5274.5  433.59  5477.7  436.15  5702.2  441.37
#Mann= 5 ,-1 , 0
  4567.7     .05       0    4900      .1       0    4999     .07       0
    5005      .1       0  5274.5     .05       0
#XS Ineff= 2 , 0
                         5103.67          431.46
Permanent Ineff=
       T       T
Bank Sta=4921.9,5023.5
XS Rating Curve= 0 ,0
Exp/Cntr=0.3,0.1

Type RM Length L Ch R = 1 ,6278    ,432,432,432
BEGIN DESCRIPTION:
UNT022 IN SUCR 7.0
END DESCRIPTION:
XS GIS Cut Line= 3
      2304441.89     13443596.27      2304522.07     13443765.54
       2305099.6      13444263.1
#Sta/Elev= 30
  4519.2  433.33    4553  432.74  4575.2  431.14  4608.4  430.74    4637  428.84
  4659.7  428.18    4688  428.35    4731  426.06  4743.7  425.06  4761.1  424.11
  4832.4  422.97  4902.7   422.9  4938.3  424.41    4974  422.74  4980.6  421.95
  4999.5  421.72  5002.3  421.22  5005.5  421.72  5037.6  423.56  5066.1  424.38
    5087  425.43  5144.8  426.08  5186.8  428.12  5236.2  428.64  5271.3  429.69
    5279  430.77  5299.8  430.32  5314.1  432.48  5394.8  433.02  5468.8  434.35
#Mann= 7 ,-1 , 0
  4519.2     .05       0    4731      .1       0  4743.7     .05       0
  4999.5    .035       0  5005.5     .05       0  5144.8      .1       0
  5394.8     .05       0
Bank Sta=4938.3,5066.1
XS Rating Curve= 0 ,0
Exp/Cntr=0.3,0.1

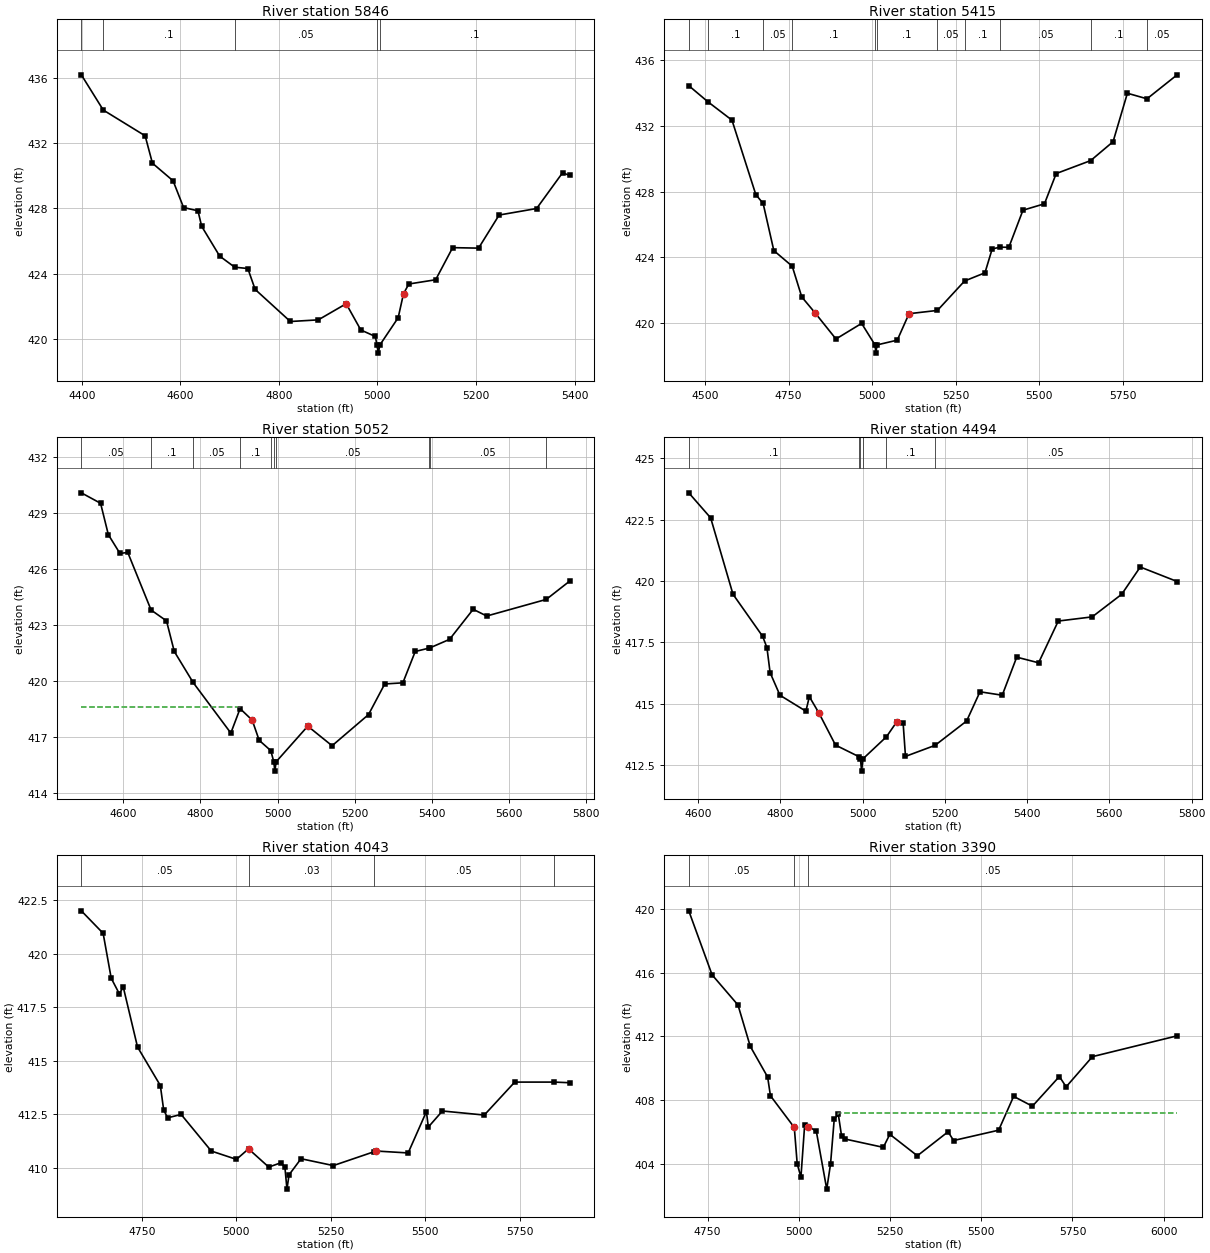
Type RM Length L Ch R = 1 ,5846    ,431,431,431
BEGIN DESCRIPTION:
UNT022 IN SUCR 6.0
END DESCRIPTION:
XS GIS Cut Line= 3
      2304087.71     13443746.84      2304437.72     13444246.85
      2304787.69     13444396.84
#Sta/Elev= 30
  4399.1  436.19  4443.6  434.03  4528.6  432.45  4543.4  430.77  4585.3  429.69
  4606.6  428.05  4635.8  427.85  4643.3   426.9  4679.9  425.07  4710.4  424.39
    4737  424.31  4751.8  423.03  4823.3  421.06    4880  421.16  4936.6  422.15
  4966.3  420.54  4995.9  420.14    4999  419.62  5001.8  419.12    5005  419.62
  5042.1  421.29    5053  422.77  5063.8  423.36  5118.2  423.62  5152.7  425.59
  5205.3  425.56    5247  427.59  5323.1  427.99  5375.7  430.18  5390.2  430.02
#Mann= 5 ,-1 , 0
  4399.1     .05       0  4443.6      .1       0  4710.4     .05       0
    4999    .035       0    5005      .1       0
Bank Sta=4936.6,5053
XS Rating Curve= 0 ,0
Exp/Cntr=0.3,0.1

Type RM Length L Ch R = 1 ,5415    ,363,363,363
BEGIN DESCRIPTION:
UNT022 IN SUCR 5.0
END DESCRIPTION:
XS GIS Cut Line= 3
      2303887.74      13443946.9      2304087.72     13444446.85
       2304787.7     13445046.84
#Sta/Elev= 30
  4451.5  434.45  4508.7  433.47  4580.7  432.35    4652  427.82  4673.9  427.28
  4705.9  424.41  4760.9  423.46  4789.4  421.59  4828.4  420.64  4891.7  419.03
  4968.4  419.98  5008.4  418.67  5011.1  418.17  5014.4  418.67    5075  418.96
  5110.2  420.57  5195.2  420.77  5276.3  422.56  5337.3  423.06  5358.8  424.51
  5382.2  424.62  5408.7  424.61  5450.9  426.87  5515.2  427.26  5550.3   429.1
  5653.4  429.89  5720.4  431.04  5763.2  433.99  5821.8  433.65  5911.9  435.11
#Mann= 11 ,-1 , 0
  4451.5     .05       0  4508.7      .1       0  4673.9     .05       0
  4760.9      .1       0  5008.4     .07       0  5014.4      .1       0
  5195.2     .05       0  5276.3      .1       0  5382.2     .05       0
  5653.4      .1       0  5821.8     .05       0
Bank Sta=4828.4,5110.2
XS Rating Curve= 0 ,0
Exp/Cntr=0.3,0.1

Type RM Length L Ch R = 1 ,5052    ,558,558,558
BEGIN DESCRIPTION:
UNT022 IN SUCR 4.0
END DESCRIPTION:
XS GIS Cut Line= 4
        2303658.     13444077.27      2303684.73     13444326.74
      2303916.33     13445048.28      2304084.57     13445243.09
#Sta/Elev= 30
  4491.2  430.09  4541.1  429.53  4561.2  427.85  4591.4  426.84  4611.5   426.9
  4672.1  423.81    4712  423.23  4732.2  421.59    4781  419.93  4878.8  417.22
  4902.8  418.53  4934.2  417.91  4952.3  416.83  4982.3  416.28  4990.2  415.68
  4992.9  415.18  4996.2  415.68  5078.3  417.59  5141.3  416.54  5235.8  418.21
  5277.8  419.85  5324.8  419.91  5356.9  421.59  5392.6  421.77  5394.5  421.78
  5445.9  422.24  5507.1  423.85  5542.3  423.49  5696.6  424.38  5757.3  425.36
#Mann= 10 ,-1 , 0
  4491.2     .05       0  4672.1      .1       0    4781     .05       0
  4902.8      .1       0  4982.3     .05       0  4990.2     .03       0
  4996.2     .05       0  5392.6      .1       0  5394.5     .05       0
  5696.6      .1       0
#XS Ineff= 2 , 0
         4903.93   418.6
Permanent Ineff=
       T       T
Bank Sta=4934.2,5078.3
XS Rating Curve= 0 ,0
Exp/Cntr=0.3,0.1

Type RM Length L Ch R = 1 ,4494    ,451,451,451
BEGIN DESCRIPTION:
UNT022 IN SUCR 3.0
END DESCRIPTION:
XS GIS Cut Line= 3
      2303355.15     13444166.35      2303159.16     13444763.23
      2303372.84     13445279.63
#Sta/Elev= 30
  4577.6  423.59  4630.8  422.57  4685.1  419.46  4757.1  417.75  4767.6  417.29
  4775.3  416.27  4799.2  415.35  4862.3   414.7  4870.7  415.29  4893.9  414.63
  4934.3  413.32  4992.3  412.84    4995  412.76  4997.7  412.26    5001  412.76
  5058.2  413.66  5083.3  414.27  5098.7  414.21  5104.4  412.86  5176.4  413.31
    5253   414.3  5285.5  415.49  5339.6  415.35  5374.8   416.9    5428  416.67
  5475.8  418.37  5558.3  418.54    5630  419.46  5675.1  420.57  5764.7  419.98
#Mann= 6 ,-1 , 0
  4577.6      .1       0  4992.3     .05       0    4995     .03       0
    5001     .05       0  5058.2      .1       0  5176.4     .05       0
Bank Sta=4893.9,5083.3
XS Rating Curve= 0 ,0
Exp/Cntr=0.3,0.1

Type RM Length L Ch R = 1 ,4043    ,653,653,653
BEGIN DESCRIPTION:
UNT022 IN SUCR 2.0
END DESCRIPTION:
XS GIS Cut Line= 3
      2302945.38     13444112.91      2302669.22      13444843.4
      2302606.87     13445351.13
#Sta/Elev= 30
  4590.2  422.01  4647.9  420.96  4669.3  418.86  4690.6  418.14  4701.3  418.44
  4738.9  415.65  4799.3  413.85  4808.2   412.7  4818.8  412.34  4854.3   412.5
  4934.1  410.79  5000.7   410.4  5032.7  410.89  5086.2  410.04  5118.3  410.24
    5129  410.04  5134.4  409.01    5140  409.68  5171.7  410.43  5257.2  410.11
  5365.4  410.76  5370.3  410.79  5455.2   410.7  5503.5  412.63  5508.6  411.91
  5545.9  412.66  5656.7  412.47  5737.3  414.01  5841.9  414.01  5882.7  413.98
#Mann= 4 ,-1 , 0
  4590.2     .05       0  5032.7     .03       0  5365.4     .05       0
  5841.9      .1       0
Bank Sta=5032.7,5370.3
XS Rating Curve= 0 ,0
Exp/Cntr=0.3,0.1

Type RM Length L Ch R = 1 ,3390    ,573,573,573
BEGIN DESCRIPTION:
Mapping XS 567a4603
END DESCRIPTION:
XS GIS Cut Line= 3
      2302250.55     13444023.82      2302161.47     13444549.43
      2302348.37     13445332.63
#Sta/Elev= 30
  4698.5  419.91  4762.4  415.88  4833.4  413.98    4867  411.38  4914.6  409.45
  4922.3  408.27  4987.7  406.27  4995.7  403.97  5005.9  403.15    5016   406.4
  5026.1  406.33    5048  406.04  5076.6  402.39    5087  403.97  5097.1  406.79
  5108.4  407.09  5117.4  405.71  5127.6  405.54  5231.6  405.02  5249.5  405.84
  5324.9  404.49  5409.1     406  5424.3  405.45  5547.7   406.1  5588.8  408.23
  5640.2  407.61  5714.1  409.48  5732.7  408.83  5804.7  410.73  6036.8  412.04
#Mann= 3 , 0 , 0
  4698.5     .05       0  4987.7     .03       0  5026.1     .05       0
#XS Ineff= 2 ,-1
 5027.23 5098.43  406.17 5106.81  6036.8  407.17
Permanent Ineff=
       T       T
Bank Sta=4987.7,5026.1
XS Rating Curve= 0 ,0
Exp/Cntr=0.3,0.1

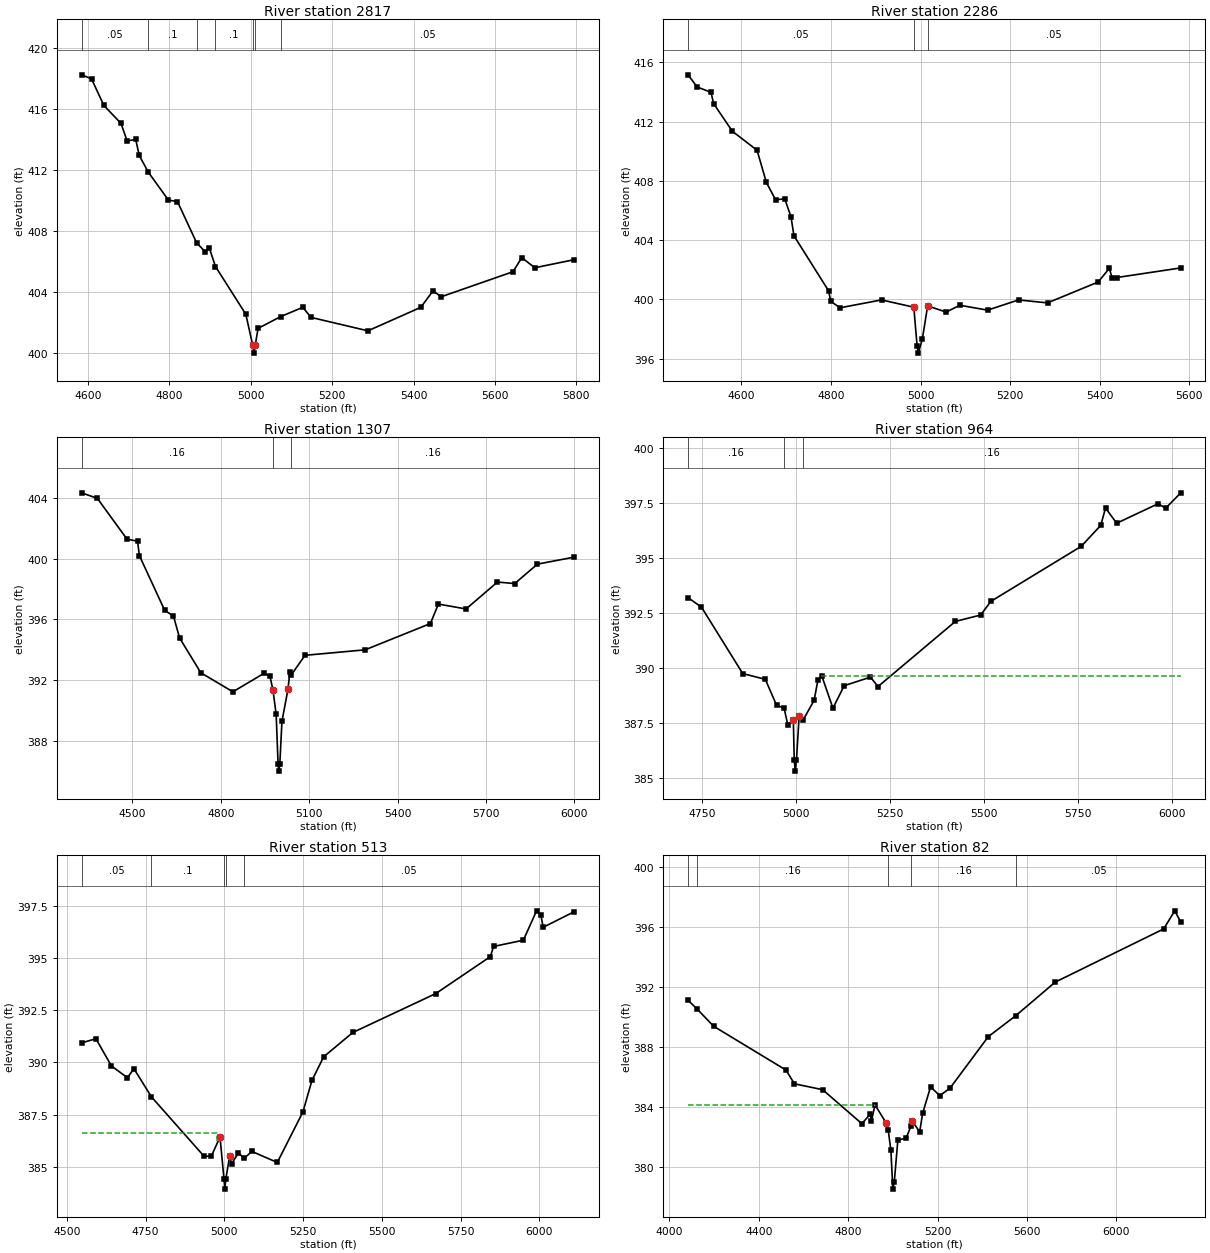
Type RM Length L Ch R = 1 ,2817    ,531,531,531
BEGIN DESCRIPTION:
Mapping XS 12983440
END DESCRIPTION:
XS GIS Cut Line= 4
      2301814.06     13443988.23      2301662.62     13444219.84
      2301662.62     13444905.75      2301751.71     13445137.38
#Sta/Elev= 30
  4584.1  418.24  4608.6  417.98  4638.8  416.24    4681  415.06  4696.1  413.91
  4717.2  414.01  4725.8  412.96  4748.1  411.87  4797.5  410.04  4819.8  409.94
  4866.9  407.24  4887.8  406.66  4897.8  406.92  4913.2  405.69  4987.8  402.56
  5004.8  400.52  5007.6  400.02  5010.8  400.52  5017.8  401.64  5073.3  402.41
  5127.8  403.02  5147.8  402.36  5287.8  401.48  5417.8  403.02  5447.8   404.1
  5467.8  403.71  5644.3  405.35  5665.8  406.27  5697.9  405.61  5794.9  406.14
#Mann= 7 ,-1 , 0
  4584.1     .05       0  4748.1      .1       0  4866.9     .05       0
  4913.2      .1       0  5004.8     .07       0  5010.8      .1       0
  5073.3     .05       0
Bank Sta=5004.8,5010.8
XS Rating Curve= 0 ,0
Exp/Cntr=0.3,0.1

Type RM Length L Ch R = 1 ,2286    ,979,979,979
BEGIN DESCRIPTION:
Mapping XS f58e6bc6
END DESCRIPTION:
XS GIS Cut Line= 3
      2301306.29     13443917.01      2301119.24     13444691.96
      2301190.51     13444985.94
#Sta/Elev= 30
    4481  415.16  4501.4  414.34  4532.3  413.98  4538.1  413.22    4580  411.35
  4635.1  410.07  4655.7  407.91  4676.3  406.73  4696.9  406.79  4710.8  405.58
  4717.4   404.3  4794.6  400.59  4799.7  399.87  4820.3  399.44  4912.9  399.97
  4984.9  399.48  4992.2  396.88  4994.9  396.38    5004  397.34  5015.8  399.57
  5056.9  399.15  5087.8  399.61  5149.5  399.28  5218.6  399.97  5283.3  399.77
  5396.4  401.18  5421.2   402.1  5427.3  401.48  5437.6  401.48  5580.7  402.13
#Mann= 3 , 0 , 0
    4481     .05       0  4984.9     .03       0  5015.8     .05       0
Bank Sta=4984.9,5015.8
XS Rating Curve= 0 ,0
Exp/Cntr=0.3,0.1

Type RM Length L Ch R = 1 ,1307    ,343,343,343
BEGIN DESCRIPTION:
Mapping XS 0bb2211d
END DESCRIPTION:
XS GIS Cut Line= 4
      2300747.82     13443681.98      2300317.24     13443987.55
      2300261.68     13444272.27       2300949.2     13444779.23
#Sta/Elev= 30
  4327.6  404.33  4381.1  403.97  4481.9  401.28  4517.6  401.15  4523.9   400.2
  4609.9  396.59  4639.4  396.23  4660.3  394.78  4732.4  392.49  4841.2  391.24
  4946.6  392.45    4967  392.26  4977.1  391.37    4988  389.76  4994.5  386.52
  4997.3  386.02  5000.5  386.52  5007.7   389.3  5028.1   391.4  5034.5  392.55
  5039.6  392.36  5086.1  393.64  5289.9     394  5511.5  395.73  5538.5  397.01
  5632.6  396.69    5739  398.46  5797.6  398.36  5874.8  399.64  5999.9   400.1
#Mann= 3 ,-1 , 0
  4327.6     .16       0  4977.1     .07       0  5039.6     .16       0
#XS Ineff= 2 , 0
          4944.5  392.41
Permanent Ineff=
       T       T
Bank Sta=4977.1,5028.1
XS Rating Curve= 0 ,0
Exp/Cntr=0.3,0.1

Type RM Length L Ch R = 1 ,964     ,768,768,768
BEGIN DESCRIPTION:
Mapping XS 01feb259
END DESCRIPTION:
XS GIS Cut Line= 3
      2299961.21     13443801.14      2299943.39     13444389.09
      2300557.82       13444772.
#Sta/Elev= 30
    4712  393.21  4747.7  392.78  4857.8  389.76  4917.8   389.5  4947.8  388.32
  4967.8  388.19  4977.8  387.43  4992.5  387.66  4994.8  385.83  4997.6  385.33
  5000.8  385.83  5007.9  387.83  5017.9  387.63  5047.9  388.55  5057.9  389.47
  5067.9  389.67  5097.9  388.19  5127.9  389.21  5197.9   389.6  5217.9  389.17
    5424  392.13  5491.2  392.42  5518.4  393.04  5759.1  395.54    5811  396.49
  5823.8  397.28  5853.5  396.59  5963.2  397.47  5984.5  397.28  6024.2  397.97
#Mann= 3 ,-1 , 0
    4712     .16       0  4967.8     .07       0  5017.9     .16       0
#XS Ineff= 2 , 0
                         5067.02          389.67
Permanent Ineff=
       T       T
Bank Sta=4992.5,5007.9
XS Rating Curve= 0 ,0
Exp/Cntr=0.3,0.1

Type RM Length L Ch R = 1 ,513     ,431,431,431
XS GIS Cut Line= 4
      2299750.18     13443934.68      2299491.92     13444153.87
      2299721.96     13444540.16        2300462.     13444774.54
#Sta/Elev= 30
  4546.4  390.94    4592  391.14  4641.4  389.83    4692  389.27  4712.8   389.7
  4768.3  388.35  4935.2   385.5  4958.4   385.5    4986  386.42  4998.6  384.42
  5001.3  383.92  5004.6  384.42  5016.6   385.5    5023  385.14  5044.4  385.66
  5062.9   385.4  5087.2  385.73  5167.9   385.2  5249.4  387.63    5278  389.14
  5315.1  390.27  5407.8  391.44  5671.4  393.31  5844.3  395.08  5854.8  395.57
  5949.2  395.87  5991.1  397.28  6004.8  397.08  6012.1  396.49    6111  397.24
#Mann= 5 ,-1 , 0
  4546.4     .05       0  4768.3      .1       0  4998.6     .07       0
  5004.6      .1       0  5062.9     .05       0
#XS Ineff= 2 , 0
       0 4977.66   386.6               0
Permanent Ineff=
       T       F
Bank Sta=4986,5016.6
XS Rating Curve= 0 ,0
Exp/Cntr=0.3,0.1

Type RM Length L Ch R = 1 ,82      ,0,0,0
BEGIN DESCRIPTION:
UNT022 IN SUCR 1.0
END DESCRIPTION:
XS GIS Cut Line= 4
      2299682.03     13443896.37      2299063.64     13444228.57
      2299230.31      13444518.5      2300362.04     13444807.76
#Sta/Elev= 30
  4083.5  391.11  4122.4  390.55  4198.5  389.37  4521.6  386.45  4559.7  385.53
  4685.6  385.14  4861.2  382.87  4898.5   383.5  4904.3  383.07  4920.1  384.12
    4969  382.94    4979  382.45  4991.1   381.1  4999.8   378.5  5006.4     379
  5022.2  381.76  5059.5  381.92  5081.1  382.71  5086.9  383.04  5119.9  382.32
  5133.1  383.56  5168.7  385.33  5209.6  384.74  5255.6  385.24  5426.9  388.68
  5550.7  390.09  5726.2  392.32  6211.3  395.87    6261  397.08    6288  396.33
#Mann= 5 ,-1 , 0
  4083.5     .05       0  4122.4     .16       0    4979     .07       0
  5081.1     .16       0  5550.7     .05       0
#XS Ineff= 2 , 0
          4919.5  384.11
Permanent Ineff=
       T       T
Bank Sta=4969,5086.9
XS Rating Curve= 0 ,0
Exp/Cntr=0.3,0.1

Chan Stop Cuts=-1
Use User Specified Reach Order=0
Composite Channel Slope=5