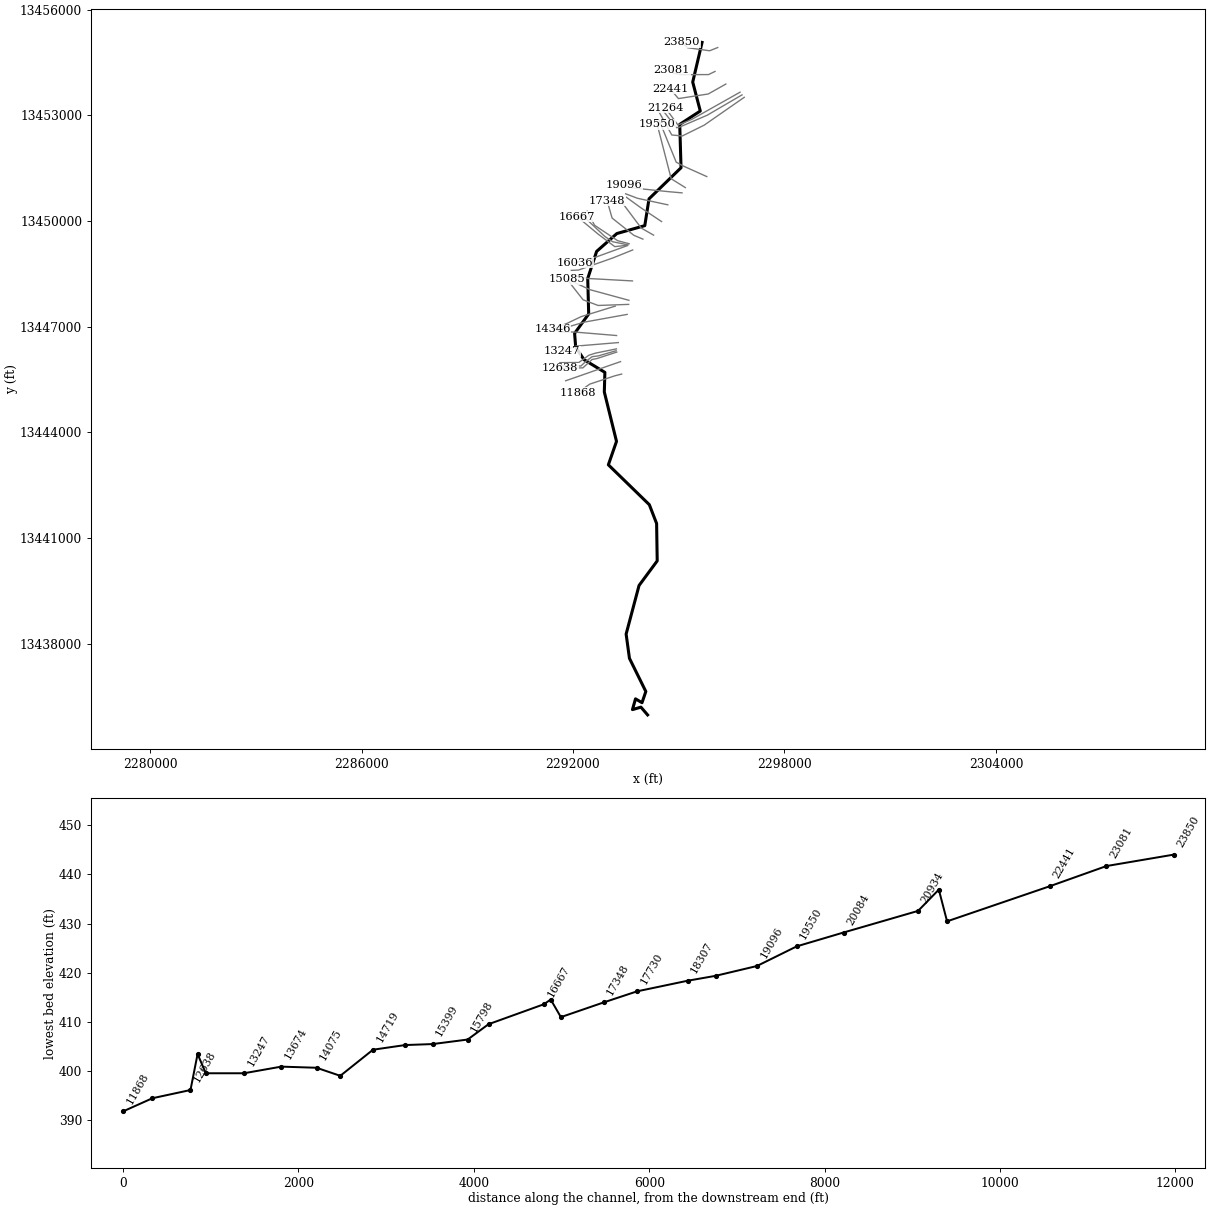
--- UNT023 IN SUCR.prj (project) ---

Proj Title=UNT023 IN SUCR Base Level Engineering
Current Plan=p01
Default Exp/Contr=0.3,0.1
English Units
Geom File=g01
Flow File=f01
Plan File=p01
Y Axis Title=Elevation
X Axis Title(PF)=Main Channel Distance
X Axis Title(XS)=Station
BEGIN DESCRIPTION:
UNT023 IN SUCR
END DESCRIPTION:
DSS Export Rating Curves= 0
DSS Export Rating Curve Sorted= 0
DSS Export Volume Flow Curves= 0
DXF OffsetX= 0
DXF OffsetY= 0
DXF ScaleX= 1
DXF ScaleY= 10

--- UNT023 IN SUCR.p01 (plan) ---

Plan Title=Multiple Run
Short Identifier=Multiple
Geom File=g01
Flow File=f01
Subcritical Flow
K Sum by GR= 0
Std Step Tol= 0.01
Critical Tol= 0.01
Num of Std Step Trials= 20
Max Error Tol= 0.3
Flow Tol Ratio= 0.001
Split Flow NTrial= 30
Split Flow Tol= 0.02
Split Flow Ratio= 0.02
Log Output Level= 0
Friction Slope Method= 1
Unsteady Friction Slope Method= 2
Unsteady Bridges Friction Slope Method= 1
Parabolic Critical Depth
Global Vel Dist=  1 , 1 , 1
Global Log Level= 0
CheckData=True
Encroach Param= -1, 0, 0, 0
BEGIN DESCRIPTION:
Multiple Run
END DESCRIPTION:

--- UNT023 IN SUCR.f01 (steady flow) ---

Flow Title=Multiple
Program Version=4.10
Number of Profiles= 7
Profile Names=10-year,25-year,50-year,1pct_min,100-year,1pct_plu,500-year
River Rch & RM=UNT023 IN SUCR,Reach-1         ,23850
     524     734     908     822    1112    1503    1671
River Rch & RM=UNT023 IN SUCR,Reach-1         ,22441
     793    1135    1426    1308    1768    2391    2730
River Rch & RM=UNT023 IN SUCR,Reach-1         ,19096
    1332    1960    2507    2337    3160    4274    5044
River Rch & RM=UNT023 IN SUCR,Reach-1         ,18624
    1332    1960    2507    2337    3160    4274    5044
River Rch & RM=UNT023 IN SUCR,Reach-1         ,15798
    1373    2021    2585    2409    3258    4405    5198
River Rch & RM=UNT023 IN SUCR,Reach-1         ,14346
    1611    2387    3067    2871    3882    5250    6249
River Rch & RM=UNT023 IN SUCR,Reach-1         ,14075
    1611    2387    3067    2871    3882    5250    6249
River Rch & RM=UNT023 IN SUCR,Reach-1         ,9842
    1615    2390    3069    2869    3880    5247    6232
River Rch & RM=UNT023 IN SUCR,Reach-1         ,7512
    1645    2432    3121    2916    3943    5333    6325
River Rch & RM=UNT023 IN SUCR,Reach-1         ,3340
    1809    2685    3455    3235    4374    5916    7050
Boundary for River Rch & Prof#=UNT023 IN SUCR,Reach-1         , 1
Up Type= 0
Dn Type= 3
Dn Slope=0.00322
Boundary for River Rch & Prof#=UNT023 IN SUCR,Reach-1         , 2
Up Type= 0
Dn Type= 3
Dn Slope=0.00322
Boundary for River Rch & Prof#=UNT023 IN SUCR,Reach-1         , 3
Up Type= 0
Dn Type= 3
Dn Slope=0.00322
Boundary for River Rch & Prof#=UNT023 IN SUCR,Reach-1         , 4
Up Type= 0
Dn Type= 3
Dn Slope=0.00322
Boundary for River Rch & Prof#=UNT023 IN SUCR,Reach-1         , 5
Up Type= 0
Dn Type= 3
Dn Slope=0.00322
Boundary for River Rch & Prof#=UNT023 IN SUCR,Reach-1         , 6
Up Type= 0
Dn Type= 3
Dn Slope=0.00322
Boundary for River Rch & Prof#=UNT023 IN SUCR,Reach-1         , 7
Up Type= 0
Dn Type= 3
Dn Slope=0.00322
DSS Import GetInterval= 0
DSS Import GetPeak= 0
DSS Import FillOption= 0

--- UNT023 IN SUCR.g01 (geometry) ---

Geom Title=Existing Conditions
Program Version=4.10

River Reach=UNT023 IN SUCR  ,Reach-1
Reach XY= 30
      2295662.56     13455067.54      2295397.94     13453942.07
      2295612.45     13453120.52      2295029.25     13452741.36
      2295066.24     13451510.19      2294157.72     13450626.85
      2294037.87     13449866.57      2293245.28      13449641.9
      2292671.25      13449135.4      2292418.91     13448366.77
      2292445.99     13447358.85      2292046.53     13446808.31
      2292076.92     13446419.85      2292313.46     13446061.78
      2292905.51     13445700.92      2292889.46     13445144.62
      2293235.38     13443742.02       2293004.3     13443076.61
      2294166.92     13441944.64      2294373.31      13441409.7
      2294390.23     13440348.68      2293874.99     13439651.06
      2293508.31      13438271.6      2293602.39     13437584.07
      2294067.44     13436641.55      2293959.13     13436323.52
      2293774.66     13436432.75      2293688.14     13436127.07
      2293927.85     13436197.62      2294117.72     13435976.85

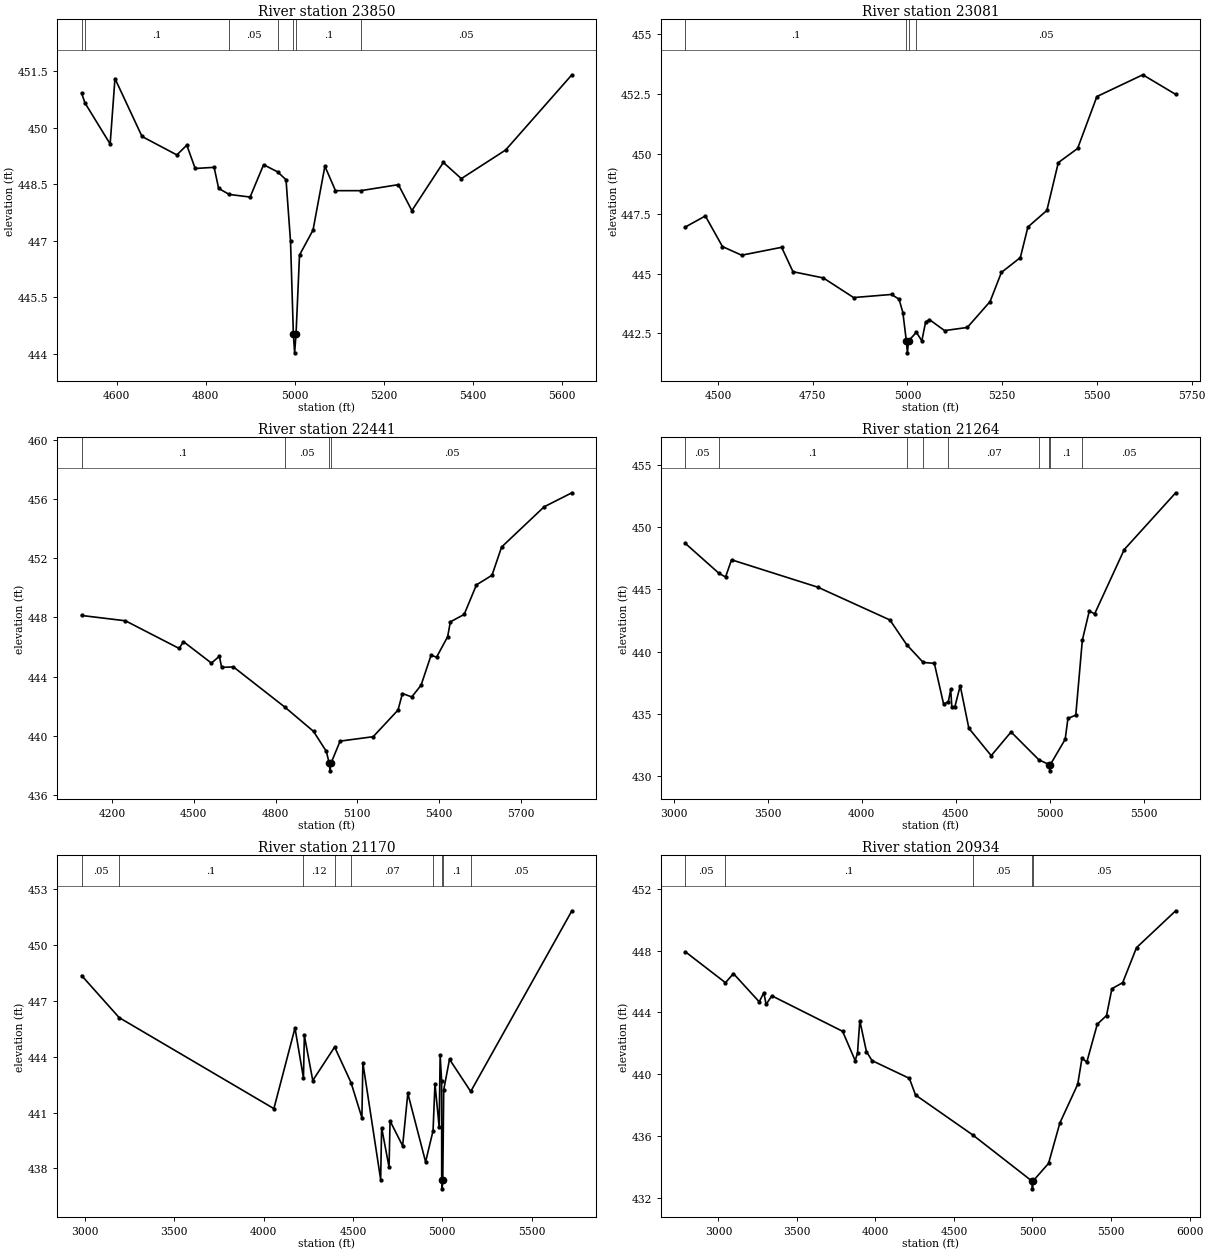
Type RM Length L Ch R = 1 ,23850   ,769,769,769
BEGIN DESCRIPTION:
UNT023 IN SUCR 13.0
END DESCRIPTION:
XS GIS Cut Line= 4
      2296107.32     13454922.63        2295876.     13454830.62
      2295252.93     13454917.38      2295087.29     13455067.24
#Sta/Elev= 30
  4521.3  450.92  4528.9  450.66  4585.4  449.57  4596.2  451.31    4657  449.77
  4735.3  449.28  4757.6  449.54  4776.4  448.92    4819  448.95  4829.1  448.39
  4852.9  448.23  4899.8  448.16  4930.1  449.02  4961.5  448.83  4980.5  448.62
  4990.6  446.98    4997  444.52  4999.8  444.02    5003  444.52  5010.8  446.62
  5041.1  447.28  5067.8  448.98  5091.6  448.33  5148.4  448.33  5232.9  448.49
  5263.2   447.8  5333.9  449.08  5374.3  448.65  5473.8  449.41  5622.7  451.41
#Mann= 7 ,-1 , 0
  4521.3     .05       0  4528.9      .1       0  4852.9     .05       0
  4961.5      .1       0    4997     .07       0    5003      .1       0
  5148.4     .05       0
Bank Sta=4997,5003
XS Rating Curve= 0 ,0
Exp/Cntr=0.3,0.1

Type RM Length L Ch R = 1 ,23081   ,640,640,640
BEGIN DESCRIPTION:
Mapping XS 22273ead
END DESCRIPTION:
XS GIS Cut Line= 5
      2296031.09     13454244.35      2295847.08     13454154.98
      2295079.42     13454152.35      2294855.96     13454194.41
      2294808.61     13454275.95
#Sta/Elev= 30
    4414  446.95  4466.6  447.41  4511.8  446.13  4562.4  445.77  4667.9   446.1
  4697.9  445.08  4777.9  444.82  4857.9     444  4957.9  444.13  4977.9  443.93
  4987.9  443.37    4997  442.19  4999.8  441.69    5003  442.19  5023.5  442.55
  5037.9  442.19  5047.9  442.98  5057.9  443.08  5097.9  442.62  5157.9  442.75
  5217.9  443.83  5247.9  445.05  5297.9  445.67  5317.9  446.95  5367.9  447.64
  5398.1  449.64    5449  450.23  5499.9   452.4  5621.1  453.31  5707.9  452.49
#Mann= 4 ,-1 , 0
    4414      .1       0    4997     .07       0    5003      .1       0
  5023.5     .05       0
Bank Sta=4997,5003
XS Rating Curve= 0 ,0
Exp/Cntr=0.3,0.1

Type RM Length L Ch R = 1 ,22441   ,1177,1177,1177
BEGIN DESCRIPTION:
Mapping XS 860a9768
END DESCRIPTION:
XS GIS Cut Line= 4
      2296337.76       13453886.       2295838.6     13453603.86
      2294992.24     13453473.65       2294753.5     13453755.81
#Sta/Elev= 30
  4088.1  448.13    4249  447.77    4446   445.9  4461.9  446.36  4564.4  444.91
  4593.6  445.37    4602  444.62  4645.2  444.65  4833.3  441.94  4939.2  440.29
  4986.1  438.94    4997  438.12  4999.8  437.62    5003  438.12  5036.7  439.63
  5158.1  439.93  5249.2  441.73  5265.5  442.85  5299.8  442.62  5333.8  443.41
  5370.6  445.44  5390.8  445.31  5431.3  446.69  5441.4   447.7    5492   448.2
  5537.1   450.2  5594.2  450.85  5629.4  452.76  5785.4  455.48  5887.4  456.43
#Mann= 4 ,-1 , 0
  4088.1      .1       0  4833.3     .05       0    4997     .03       0
    5003     .05       0
Bank Sta=4997,5003
XS Rating Curve= 0 ,0
Exp/Cntr=0.3,0.1

Type RM Length L Ch R = 1 ,21264   ,94,94,94
BEGIN DESCRIPTION:
Mapping XS 5993b51d
END DESCRIPTION:
XS GIS Cut Line= 5
      2296741.44     13453655.24      2295373.37      13452884.4
      2295109.48     13452773.29      2294977.54     13452724.68
      2294616.41     13453217.75
#Sta/Elev= 30
  3061.5  448.69  3240.4  446.29  3275.1     446  3306.8  447.38  3766.3  445.18
  4149.3  442.55  4238.5  440.57  4326.7  439.14  4385.8  439.07  4435.3  435.79
  4460.5     436  4472.9  436.98  4478.7   435.6  4494.6  435.56  4523.5  437.27
  4569.4  433.86  4688.3  431.66  4794.1  433.56  4941.6  431.33    4997  430.94
  4999.8  430.44    5003  430.94  5081.9  432.97  5096.6  434.65  5138.3  434.91
  5173.2  440.93  5210.2  443.27  5238.6  443.04  5396.1   448.2  5669.9  452.76
#Mann= 9 ,-1 , 0
  3061.5     .05       0  3240.4      .1       0  4238.5     .07       0
  4326.7     .12       0  4460.5     .07       0  4941.6      .1       0
    4997     .07       0    5003      .1       0  5173.2     .05       0
Bank Sta=4997,5003
XS Rating Curve= 0 ,0
Exp/Cntr=0.3,0.1

Type RM Length L Ch R = 1 ,21170   ,236,236,236
BEGIN DESCRIPTION:
Mapping XS 1c764b4c
END DESCRIPTION:
XS GIS Cut Line= 5
      2296796.94     13453578.82      2295810.87     13453002.45
      2295005.32     13452655.23      2294928.93     13452648.29
      2294533.24     13453161.99
#Sta/Elev= 30
  2981.3  448.36  3191.4   446.1  4057.6  441.21  4175.7  445.54  4223.1  442.86
  4228.2  445.14  4275.2  442.72  4397.6  444.52  4489.3  442.61  4550.3  440.72
  4555.7  443.67  4655.3   437.4  4660.7  440.19  4702.3  438.06  4707.8  440.55
  4778.3  439.21  4807.3  442.03  4906.8  438.35  4948.6  440.02  4959.3  442.55
  4982.8  440.22  4988.3  444.09  4996.6  442.68    4997   437.4  4999.8   436.9
    5003   437.4  5008.3  442.22  5040.7  443.86  5159.4  442.13  5725.8  451.84
#Mann= 9 ,-1 , 0
  2981.3     .05       0  3191.4      .1       0  4223.1     .12       0
  4397.6      .1       0  4489.3     .07       0  4948.6      .1       0
    4997     .07       0    5003      .1       0  5159.4     .05       0
Bank Sta=4997,5003
XS Rating Curve= 0 ,0
Exp/Cntr=0.3,0.1

Type RM Length L Ch R = 1 ,20934   ,850,850,850
BEGIN DESCRIPTION:
Mapping XS e95d2ef4
END DESCRIPTION:
XS GIS Cut Line= 5
      2296859.48     13453509.39      2295720.59     13452717.73
      2295102.54     13452412.18      2294803.93     13452439.95
      2294443.04     13453092.32
#Sta/Elev= 30
  2790.1  447.93  3045.1  445.93  3095.9  446.52    3260  444.69  3289.7  445.28
  3303.7  444.52  3340.3  445.08  3790.9  442.78    3871  440.88  3885.9  441.37
  3900.5  443.47  3942.6  441.47  3978.4  440.88  4216.1  439.73  4255.4  438.65
  4621.5  436.05    4997  433.07  4999.8  432.57    5003  433.07  5102.4  434.22
  5174.5  436.84  5287.9  439.34  5315.4  441.04  5345.8  440.78  5412.7  443.24
  5471.5   443.8  5505.8  445.54  5574.3  445.93  5662.4   448.2    5912  450.59
#Mann= 5 ,-1 , 0
  2790.1     .05       0  3045.1      .1       0  4621.5     .05       0
    4997     .04       0    5003     .05       0
Bank Sta=4997,5003
XS Rating Curve= 0 ,0
Exp/Cntr=0.3,0.1

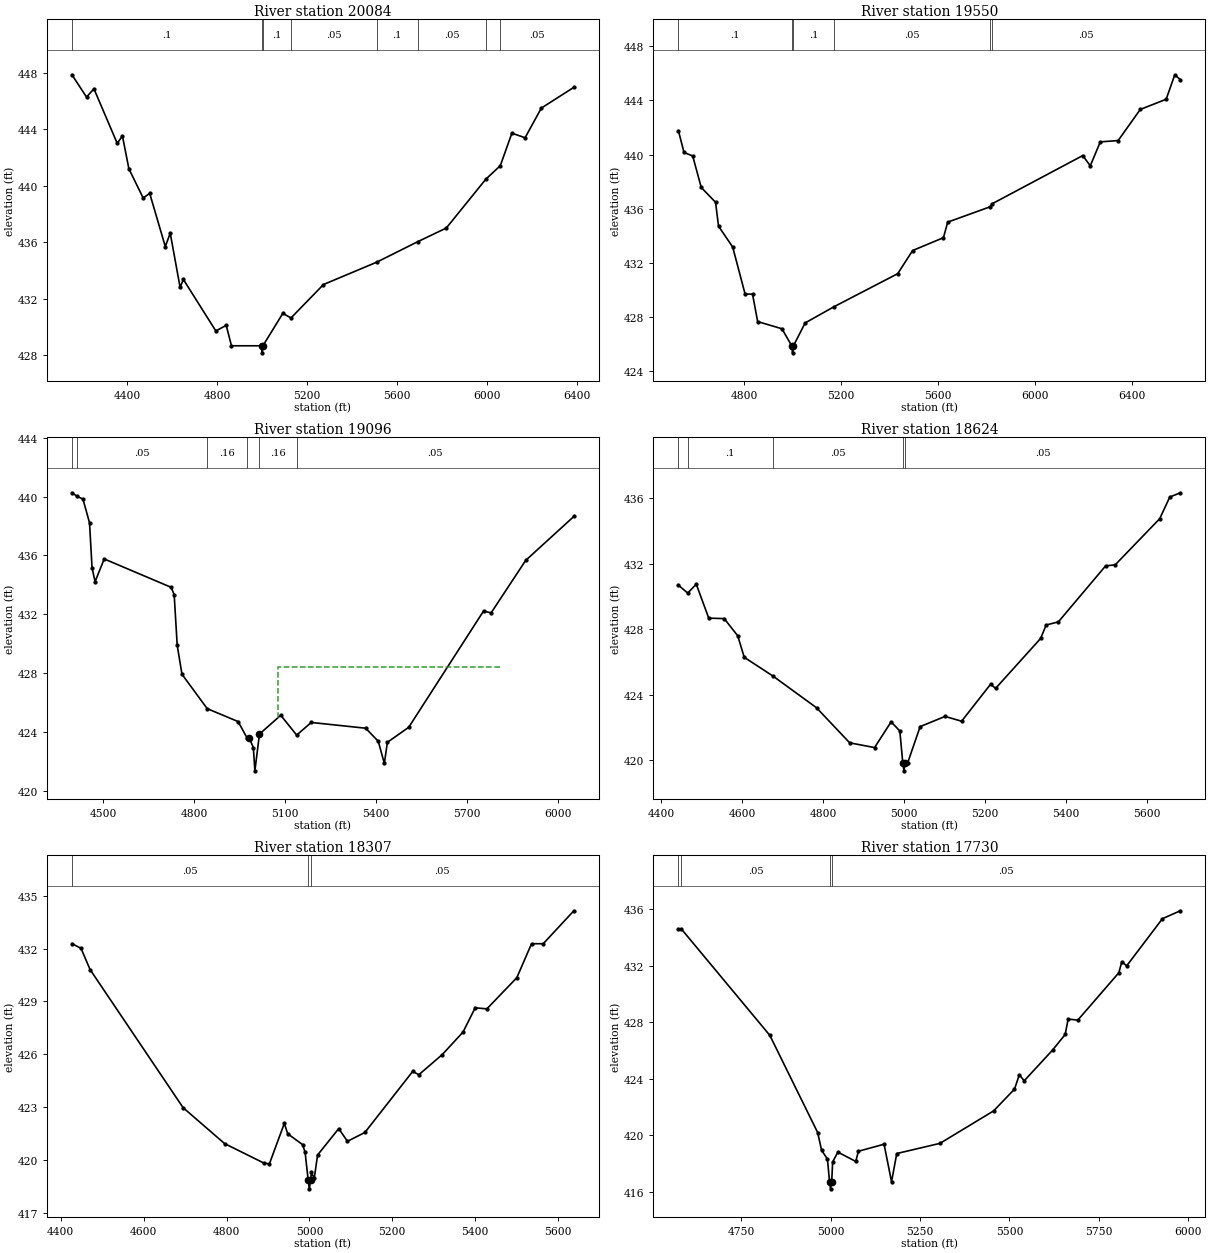
Type RM Length L Ch R = 1 ,20084   ,534,534,534
BEGIN DESCRIPTION:
Mapping XS 4727b0c5
END DESCRIPTION:
XS GIS Cut Line= 4
      2295796.97      13451259.4      2295116.43     13451564.95
      2294928.93     13451669.12      2294449.75      13452849.7
#Sta/Elev= 30
  4152.8  447.87  4217.7  446.29  4250.6  446.88  4354.4  443.01  4377.6  443.54
  4406.3  441.21  4469.9  439.14  4498.9  439.47  4568.4   435.7  4590.4  436.65
  4634.3  432.81  4648.9  433.37  4793.4  429.72  4839.7  430.12  4862.9  428.67
    4997  428.67  4999.8  428.17    5003  428.67  5091.8  430.97  5127.9  430.64
  5272.7  433.01  5509.3  434.59  5691.6  436.04  5819.4  437.01  5995.3  440.47
    6060  441.43  6111.4  443.73  6170.3  443.41  6242.6  445.51  6387.4  446.98
#Mann= 8 ,-1 , 0
  4152.8      .1       0    4997     .07       0    5003      .1       0
  5127.9     .05       0  5509.3      .1       0  5691.6     .05       0
  5995.3      .1       0    6060     .05       0
Bank Sta=4997,5003
XS Rating Curve= 0 ,0
Exp/Cntr=0.3,0.1

Type RM Length L Ch R = 1 ,19550   ,454,454,454
BEGIN DESCRIPTION:
UNT023 IN SUCR 12.0
END DESCRIPTION:
XS GIS Cut Line= 3
      2295187.72     13450946.86      2294787.72     13451196.85
      2294387.72     13452746.87
#Sta/Elev= 30
  4528.5  441.77  4551.5  440.16  4587.5   439.9  4622.8  437.57  4681.8  436.48
  4694.2  434.71  4752.6  433.17  4803.9  429.69  4834.5  429.69  4855.7  427.66
    4956  427.13    4997  425.85  4999.8  425.35    5003  425.85  5051.8  427.56
  5171.2  428.76    5434   431.2  5495.6  432.91  5622.8  433.86  5640.5  435.01
  5815.1  436.14  5824.4  436.37  6198.2  439.93  6229.2  439.17  6270.5  440.94
  6344.4  441.04  6435.7  443.34  6542.6  444.09  6578.1   445.9    6601  445.54
#Mann= 6 ,-1 , 0
  4528.5      .1       0    4997     .07       0    5003      .1       0
  5171.2     .05       0  5815.1      .1       0  5824.4     .05       0
Bank Sta=4997,5003
XS Rating Curve= 0 ,0
Exp/Cntr=0.3,0.1

Type RM Length L Ch R = 1 ,19096   ,472,472,472
BEGIN DESCRIPTION:
UNT023 IN SUCR 11.0
END DESCRIPTION:
XS GIS Cut Line= 4
      2295093.83     13450797.08      2294731.57     13450828.78
      2293730.82     13450932.93      2293454.55     13451009.92
#Sta/Elev= 30
    4396  440.26  4413.9  440.01  4432.3  439.83    4454  438.22  4462.4  435.14
  4472.4  434.22  4502.5  435.76  4723.4  433.83  4733.4  433.33  4743.4  429.89
  4759.1  427.92  4842.4  425.58  4944.5   424.7  4974.7  423.56  4981.1  423.59
  4994.8  422.93  4999.8  421.35  5014.9  423.85  5085.2  425.13  5137.7  423.78
  5185.8  424.64  5365.4  424.25    5407  423.36  5427.1  421.85  5437.1  423.29
  5507.5  424.31  5754.6  432.22  5779.4  432.09  5893.6  435.66  6052.6  438.65
#Mann= 6 ,-1 , 0
    4396      .1       0  4413.9     .05       0  4842.4     .16       0
  4974.7     .12       0  5014.9     .16       0  5137.7     .05       0
#XS Ineff= 1 ,-1
 5076.81 5812.32 428.382
Permanent Ineff=
       T
Bank Sta=4981.1,5014.9
XS Rating Curve= 0 ,0
Exp/Cntr=0.3,0.1

Type RM Length L Ch R = 1 ,18624   ,317,317,317
BEGIN DESCRIPTION:
UNT023 IN SUCR 10.0
END DESCRIPTION:
XS GIS Cut Line= 3
      2294690.84     13450457.45      2293830.44     13450643.12
      2293495.34     13450769.92
#Sta/Elev= 30
  4443.4  430.68  4466.3   430.2  4487.5  430.74  4518.2  428.67  4556.5  428.64
  4589.8  427.59  4605.8  426.28  4676.4  425.14  4784.2   423.2    4866  421.06
  4927.4  420.77  4968.3  422.34  4989.8  421.78    4997  419.85  4999.8  419.35
    5003  419.85  5009.3  419.85  5039.9  422.05  5101.3  422.67  5142.2  422.38
  5213.9  424.64    5226  424.38  5337.2  427.43  5350.8  428.25  5380.9  428.44
  5497.6  431.86  5521.1  431.92  5631.1  434.74  5655.9  436.06  5681.9  436.32
#Mann= 5 ,-1 , 0
  4443.4     .05       0  4466.3      .1       0  4676.4     .05       0
    4997     .03       0    5003     .05       0
Bank Sta=4997,5003
XS Rating Curve= 0 ,0
Exp/Cntr=0.3,0.1

Type RM Length L Ch R = 1 ,18307   ,577,577,577
BEGIN DESCRIPTION:
UNT023 IN SUCR 9.0
END DESCRIPTION:
XS GIS Cut Line= 3
      2294514.18     13449982.01      2293916.48     13450380.48
      2293517.98      13450670.3
#Sta/Elev= 30
    4427  432.28  4448.8  432.02  4470.8  430.81  4695.2  422.97  4795.3  420.93
  4890.5  419.82  4903.5  419.78  4939.5  422.08  4947.5  421.49  4983.6  420.87
  4989.6  420.44    4997  418.86  4999.8  418.36    5003  418.86  5004.6  419.29
  5011.7  418.96  5019.7  420.28  5070.7  421.78  5091.8  421.06  5133.8  421.56
  5249.3  425.03    5264  424.84  5320.4  425.98  5370.6  427.26    5400  428.64
  5428.2  428.58  5500.5  430.35    5536  432.28  5564.2  432.28  5638.1  434.15
#Mann= 3 ,-1 , 0
    4427     .05       0    4997     .03       0    5003     .05       0
Bank Sta=4997,5003
XS Rating Curve= 0 ,0
Exp/Cntr=0.3,0.1

Type RM Length L Ch R = 1 ,17730   ,382,382,382
BEGIN DESCRIPTION:
UNT023 IN SUCR 8.0
END DESCRIPTION:
XS GIS Cut Line= 3
      2294287.69     13449596.87      2293937.72     13449796.85
       2293337.7     13450596.88
#Sta/Elev= 30
  4574.5  434.61  4583.1  434.59    4830  427.07  4963.9  420.18  4974.7  418.93
  4991.1  418.31    4997   416.7  4999.8   416.2    5003   416.7  5005.7  418.11
  5020.3   418.8  5070.3  418.14  5077.6  418.86  5149.4  419.36  5170.3   416.7
  5184.9   418.7  5305.7  419.42  5455.7  421.72    5514  423.26  5527.6  424.28
  5541.1  423.85  5620.3  426.02  5655.7  427.13    5664  428.22  5691.1  428.15
  5805.7   431.5    5814  432.28  5827.6  431.99  5927.6  435.33  5977.6  435.89
#Mann= 4 ,-1 , 0
  4574.5     .08       0  4583.1     .05       0    4997     .03       0
    5003     .05       0
Bank Sta=4997,5003
XS Rating Curve= 0 ,0
Exp/Cntr=0.3,0.1

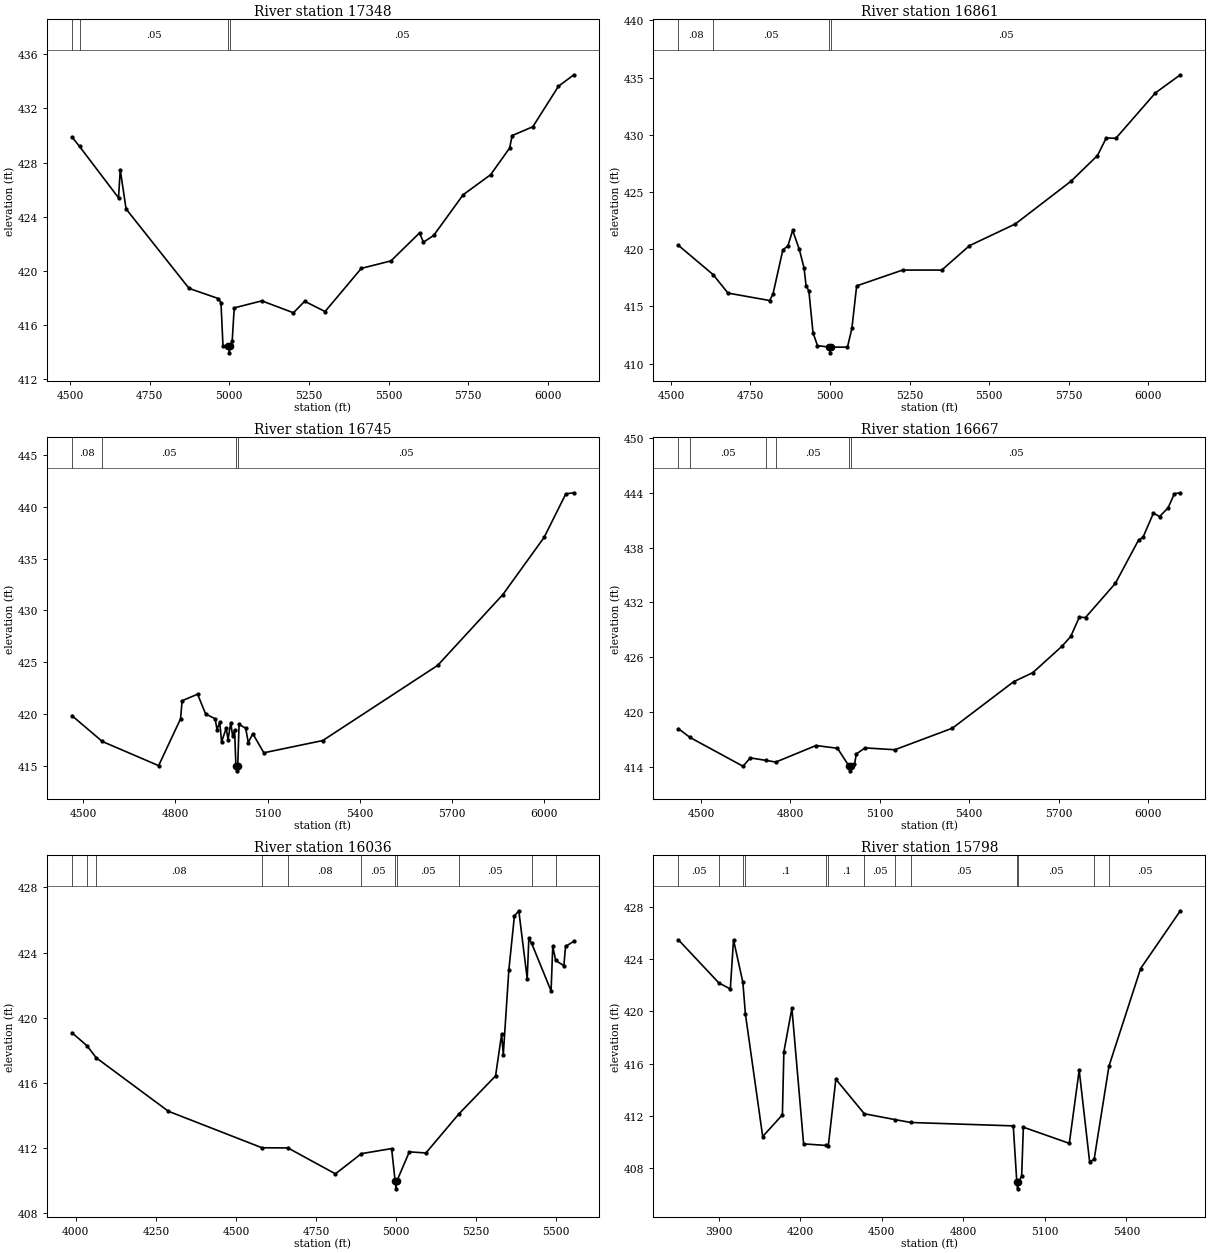
Type RM Length L Ch R = 1 ,17348   ,487,487,487
BEGIN DESCRIPTION:
UNT023 IN SUCR 7.0
END DESCRIPTION:
XS GIS Cut Line= 4
      2293984.42     13449483.87      2293726.29     13449592.55
      2293110.44     13450081.61      2292970.06     13450570.67
#Sta/Elev= 30
    4506  429.89  4529.7  429.19  4652.2  425.39  4657.6  427.46  4675.9  424.57
  4873.6   418.7  4965.6  417.95  4973.7  417.65  4980.1  414.44    4997  414.44
  4999.8  413.94    5003  414.44  5008.9   414.8  5015.3  417.26  5101.8  417.78
  5201.2   416.9  5236.4  417.75  5300.5  416.99  5414.2  420.18  5507.2  420.73
    5597   422.8  5609.2  422.11  5641.2  422.61    5734  425.62  5820.2   427.1
  5879.7  429.07  5887.7  429.99  5952.5  430.64    6033  433.63  6081.3  434.48
#Mann= 4 ,-1 , 0
    4506     .08       0  4529.7     .05       0    4997     .03       0
    5003     .05       0
Bank Sta=4997,5003
XS Rating Curve= 0 ,0
Exp/Cntr=0.3,0.1

Type RM Length L Ch R = 1 ,16861   ,116,116,116
BEGIN DESCRIPTION:
UNT023 IN SUCR 6.0
END DESCRIPTION:
XS GIS Cut Line= 4
      2293594.95     13449352.56      2293268.93     13449438.59
      2292612.33     13449877.84      2292404.03     13450276.32
#Sta/Elev= 30
  4523.6  420.34  4632.8  417.78  4679.3  416.17  4810.3  415.52  4820.7  416.08
  4851.7  419.95  4867.4  420.28  4882.5  421.65  4903.5  419.98  4918.5  418.34
  4924.5  416.83  4933.5  416.34  4946.5   412.7  4960.5  411.58    4997  411.45
  4999.8  410.95    5003  411.45  5054.7  411.45  5068.6  413.09  5083.6   416.8
  5227.8  418.18  5350.9  418.18  5437.9  420.31  5582.1  422.21  5757.3  425.95
    5840  428.18  5867.7  429.72  5897.9  429.69  6022.3  433.66  6100.4  435.24
#Mann= 4 ,-1 , 0
  4523.6     .08       0  4632.8     .05       0    4997     .03       0
    5003     .05       0
Bank Sta=4997,5003
XS Rating Curve= 0 ,0
Exp/Cntr=0.3,0.1

Type RM Length L Ch R = 1 ,16745   ,78,78,78
BEGIN DESCRIPTION:
UNT023 IN SUCR 6.1
END DESCRIPTION:
XS GIS Cut Line= 4
      2293564.38      13449319.6      2293125.11     13449409.88
      2292902.89     13449560.92      2292234.51     13450190.42
#Sta/Elev= 30
  4462.8  419.85  4561.8  417.36  4745.2  415.03  4816.7  419.55  4821.8  421.29
  4872.1  421.92  4898.4  420.01  4929.4  419.55  4935.4   418.5  4944.3  419.23
  4950.4  417.32  4965.3  418.64  4971.4  417.55  4980.3  419.19  4986.3  417.88
  4992.7  418.47    4997  415.03  4999.8  414.53    5003  415.03  5007.3     419
    5029  418.64  5037.2  417.26  5052.1  418.11    5088  416.27  5279.9  417.45
  5654.5   424.7  5866.9  431.53  6001.2  437.04    6072  441.24  6098.1  441.34
#Mann= 4 ,-1 , 0
  4462.8     .08       0  4561.8     .05       0    4997     .03       0
    5003     .05       0
Bank Sta=4997,5003
XS Rating Curve= 0 ,0
Exp/Cntr=0.3,0.1

Type RM Length L Ch R = 1 ,16667   ,631,631,631
BEGIN DESCRIPTION:
UNT023 IN SUCR 6.2
END DESCRIPTION:
XS GIS Cut Line= 4
      2293507.36     13449305.36      2293186.04     13449270.52
      2292722.25     13449619.17      2292121.73     13450118.31
#Sta/Elev= 30
  4424.1  418.18  4463.2  417.22  4641.1  414.07  4665.1  414.99  4718.5  414.71
  4750.9  414.53  4885.9  416.34  4957.9  416.04    4997  414.07  4999.8  413.57
    5003  414.07    5015  414.27  5021.2  415.42  5050.4  416.08  5150.4  415.88
  5343.6  418.24  5549.4  423.33  5613.2  424.31  5712.1  427.23  5740.7  428.28
  5769.4  430.38  5790.2  430.35  5890.5  434.09  5968.6  438.85  5982.9  439.11
  6018.1  441.77  6038.9   441.4  6067.6  442.36  6088.4   443.9  6108.4     444
#Mann= 6 ,-1 , 0
  4424.1     .08       0  4463.2     .05       0  4718.5     .08       0
  4750.9     .05       0    4997     .03       0    5003     .05       0
Bank Sta=4997,5003
XS Rating Curve= 0 ,0
Exp/Cntr=0.3,0.1

Type RM Length L Ch R = 1 ,16036   ,238,238,238
BEGIN DESCRIPTION:
UNT023 IN SUCR 5.0
END DESCRIPTION:
XS GIS Cut Line= 3
      2293540.59      13449298.2       2292671.2     13448981.23
      2292051.76     13448813.94
#Sta/Elev= 30
  3988.1  419.09  4035.5  418.28  4063.9  417.55  4289.2  414.27  4581.4  412.03
  4662.4  412.02  4810.7  410.43  4891.9  411.67  4986.1  411.98    4997  410.01
  4999.8  409.51    5003  410.01  5041.4  411.78  5093.2  411.71  5195.4  414.09
  5310.7  416.44  5329.6     419  5334.8  417.75  5352.1  422.93  5369.5  426.25
  5383.2  426.57  5409.4  422.41  5414.6  424.87    5423  424.59    5484  421.65
  5489.2  424.38  5498.5  423.52  5523.9   423.2  5529.1  424.38  5555.1   424.7
#Mann= 11 ,-1 , 0
  3988.1     .08       0  4035.5     .05       0  4063.9     .08       0
  4581.4     .05       0  4662.4     .08       0  4891.9     .05       0
    4997     .07       0    5003     .05       0  5195.4     .05       0
    5423     .08       0  5498.5     .05       0
Bank Sta=4997,5003
XS Rating Curve= 0 ,0
Exp/Cntr=0.3,0.1

Type RM Length L Ch R = 1 ,15798   ,399,399,399
BEGIN DESCRIPTION:
UNT023 IN SUCR 4.0
END DESCRIPTION:
XS GIS Cut Line= 4
      2293694.64     13449175.97      2293133.08     13448949.53
      2292154.97     13448605.38      2291951.95     13448596.36
#Sta/Elev= 30
  3752.6  425.49  3901.2  422.19  3943.4  421.72  3955.2  425.49  3989.6  422.23
    3999  419.79  4062.5   410.4    4135  412.07  4140.4   416.9  4169.9  420.24
  4212.9  409.84  4294.1  409.72  4303.8   409.7  4331.5   414.8  4436.2  412.15
  4549.4   411.7    4607  411.48  4983.9  411.22    4997  406.89  4999.8  406.39
    5003  406.89  5014.8  407.38    5021  411.12    5190  409.88  5226.3  415.49
  5264.9  408.43  5281.5  408.68  5335.9  415.81  5452.3  423.29  5598.2  427.72
#Mann= 13 ,-1 , 0
  3752.6     .05       0  3901.2      .1       0  3989.6     .05       0
    3999      .1       0  4294.1     .05       0  4303.8      .1       0
  4436.2     .05       0  4549.4     .08       0    4607     .05       0
    4997     .03       0    5003     .05       0  5281.5      .1       0
  5335.9     .05       0
Bank Sta=4997,5003
XS Rating Curve= 0 ,0
Exp/Cntr=0.3,0.1

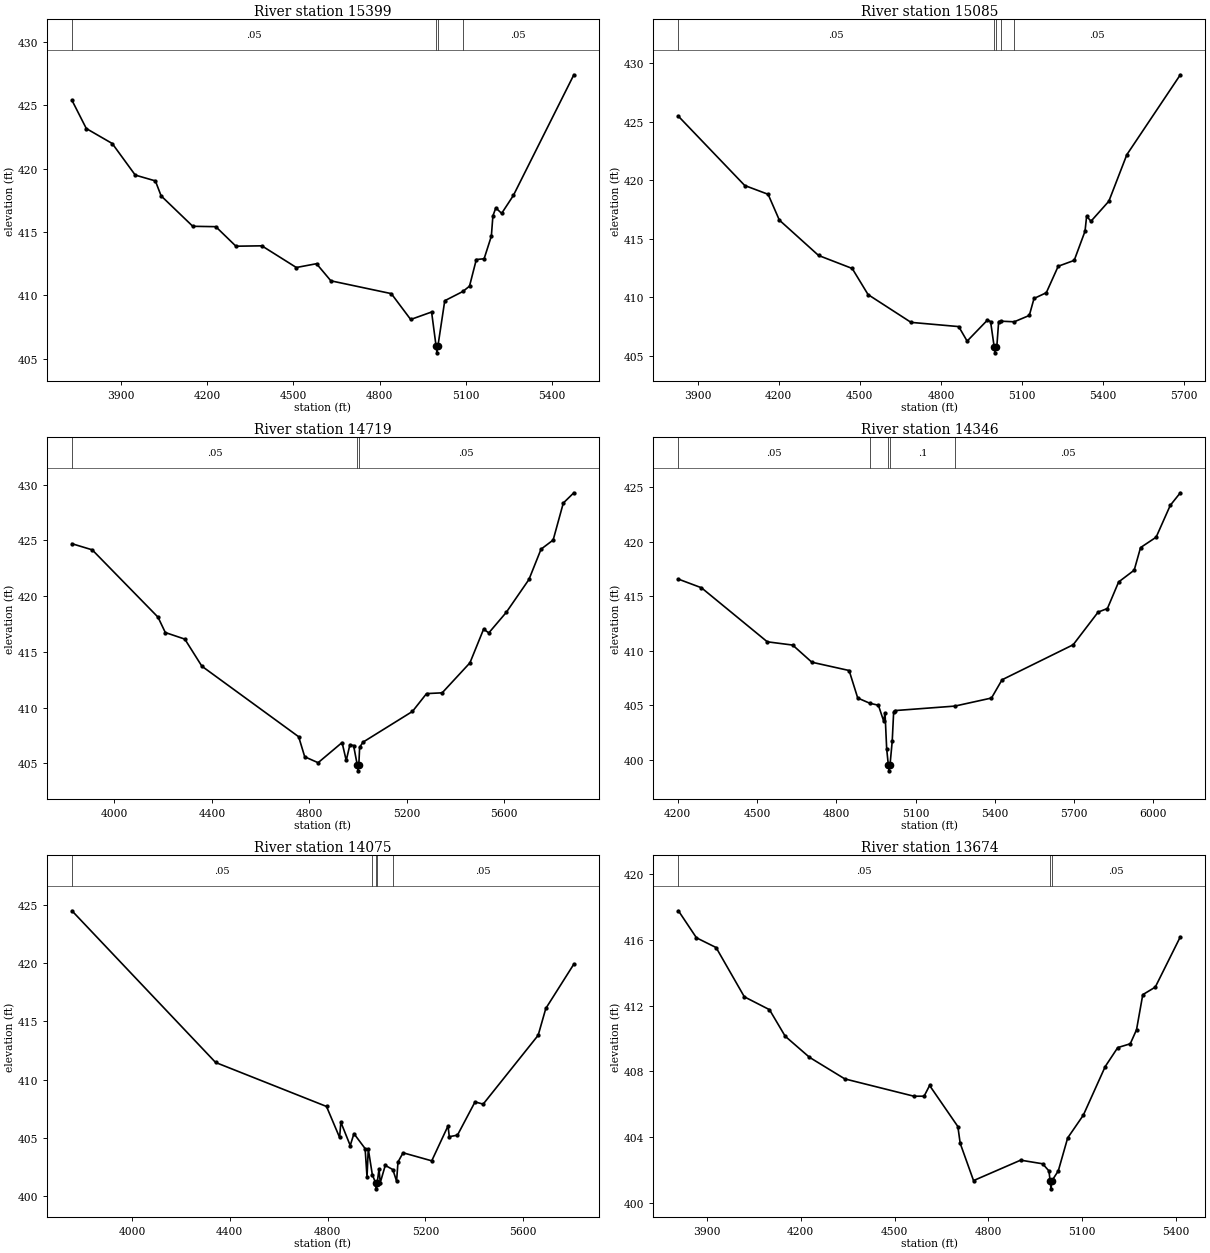
Type RM Length L Ch R = 1 ,15399   ,314,314,314
BEGIN DESCRIPTION:
UNT023 IN SUCR 3.0
END DESCRIPTION:
XS GIS Cut Line= 3
      2293687.68     13448296.86      2292418.91     13448366.77
      2291950.79     13448455.22
#Sta/Elev= 30
  3729.3  425.39  3779.3  423.16  3869.5  421.98  3949.6  419.49  4019.7  419.03
  4039.7  417.85  4149.9  415.45    4230  415.42  4300.1  413.88  4390.3  413.91
  4510.4   412.2  4580.6   412.5  4630.6  411.15  4840.9  410.14  4908.4   408.1
  4981.2  408.69    4997  405.97  4999.8  405.47    5003  405.97    5027  409.58
  5090.1  410.31  5113.2  410.73  5136.9  412.83    5164  412.89  5189.2  414.67
  5194.6  416.27  5204.7   416.9  5225.1  416.47  5265.8  417.88  5476.4   427.4
#Mann= 4 ,-1 , 0
  3729.3     .05       0    4997     .03       0    5003     .05       0
  5090.1     .05       0
Bank Sta=4997,5003
XS Rating Curve= 0 ,0
Exp/Cntr=0.3,0.1

Type RM Length L Ch R = 1 ,15085   ,366,366,366
BEGIN DESCRIPTION:
UNT023 IN SUCR 2.0
END DESCRIPTION:
XS GIS Cut Line= 3
      2293587.75     13447746.85      2292487.72     13448046.85
      2291837.72     13448346.85
#Sta/Elev= 30
  3829.2  425.46  4074.5  419.55  4160.9   418.8  4202.4   416.6  4347.5  413.58
  4471.9  412.47  4530.6  410.24  4689.5  407.87  4865.8  407.51  4896.9  406.27
  4972.2  408.07  4983.6  407.94    4997  405.77  4999.8  405.27    5003  405.77
  5006.6  405.77  5013.5  407.94  5022.8  407.97  5071.1  407.92  5126.8  408.46
  5144.3  409.91  5189.7   410.4  5233.7  412.66  5292.9  413.16  5332.9  415.65
  5338.8  416.93  5354.9   416.5    5421  418.21  5487.5  422.18  5685.3     429
#Mann= 5 ,-1 , 0
  3829.2     .05       0    4997     .03       0    5003     .05       0
  5022.8      .1       0  5071.1     .05       0
Bank Sta=4997,5003
XS Rating Curve= 0 ,0
Exp/Cntr=0.3,0.1

Type RM Length L Ch R = 1 ,14719   ,373,373,373
BEGIN DESCRIPTION:
Mapping XS c50030d5
END DESCRIPTION:
XS GIS Cut Line= 4
      2293580.83     13447630.93      2292712.78     13447600.54
      2292287.43     13447761.13      2291832.58     13448341.62
#Sta/Elev= 30
  3825.3   424.7  3908.5  424.15  4178.6  418.11  4208.6  416.73  4288.7  416.14
  4358.7  413.71  4756.1  407.38    4781  405.58    4836  405.05  4934.4  406.86
  4951.4  405.25  4966.5  406.66  4981.6  406.59    4997  404.82  4999.8  404.32
    5003  404.82  5006.5  406.43    5020  406.89  5223.3  409.65  5281.2  411.25
  5345.4  411.32  5459.3  414.01  5515.4  417.03  5536.9   416.7  5608.5  418.54
  5701.6  421.49  5751.3  424.21    5801  425.03  5842.7  428.35    5886  429.27
#Mann= 3 ,-1 , 0
  3825.3     .05       0    4997     .03       0    5003     .05       0
Bank Sta=4997,5003
XS Rating Curve= 0 ,0
Exp/Cntr=0.3,0.1

Type RM Length L Ch R = 1 ,14346   ,271,271,271
BEGIN DESCRIPTION:
UNT023 IN SUCR 26.0
END DESCRIPTION:
XS GIS Cut Line= 4
      2293200.99     13447581.98      2292231.95     13447283.12
      2291833.46     13447092.93       2291422.1     13446925.67
#Sta/Elev= 30
  4202.3  416.57  4289.4  415.78  4538.7  410.83  4634.8  410.53  4707.3  408.96
  4848.4   408.2    4881  405.68  4926.8   405.2  4959.2  405.02    4979  403.58
  4984.3   404.3  4990.6  401.02    4997  399.51  4999.8  399.01    5003  399.51
  5011.5  401.71  5016.9  404.36  5022.1  404.53  5248.6  404.94  5387.3  405.68
  5427.2  407.35  5696.5  410.56  5790.9  413.55  5826.1  413.88  5868.5  416.31
  5927.4  417.39  5951.5  419.46  6010.4  420.41    6064  423.33    6102  424.48
#Mann= 5 ,-1 , 0
  4202.3     .05       0  4926.8      .1       0    4997     .07       0
    5003      .1       0  5248.6     .05       0
Bank Sta=4997,5003
XS Rating Curve= 0 ,0
Exp/Cntr=0.3,0.1

Type RM Length L Ch R = 1 ,14075   ,401,401,401
BEGIN DESCRIPTION:
UNT023 IN SUCR 25.0
END DESCRIPTION:
XS GIS Cut Line= 3
      2293537.77     13447346.86      2292317.28     13447126.42
      2291537.71     13446896.85
#Sta/Elev= 30
  3754.6  424.48  4342.2  411.48  4795.8  407.71  4849.4  405.05  4854.5  406.36
  4892.8  404.36    4908  405.38  4953.7   404.1  4961.5  401.67  4966.6  404.07
  4983.3  401.85    4997  401.15  4999.8  400.65    5003  401.15  5010.5  402.33
  5015.7  401.18  5036.1  402.66  5067.1   402.3  5082.4  401.31  5088.2  402.95
    5109  403.74  5226.2  403.05  5292.8  406.04    5298  405.12  5331.4  405.25
  5403.3   408.1  5436.6  407.91  5661.5  413.81  5692.8  416.11  5807.5  419.91
#Mann= 5 ,-1 , 0
  3754.6     .05       0  4983.3      .1       0    4997     .07       0
    5003      .1       0  5067.1     .05       0
Bank Sta=4997,5003
XS Rating Curve= 0 ,0
Exp/Cntr=0.3,0.1

Type RM Length L Ch R = 1 ,13674   ,427,427,427
BEGIN DESCRIPTION:
UNT023 IN SUCR 24.0
END DESCRIPTION:
XS GIS Cut Line= 3
       2293237.7     13446746.86      2292037.72     13446846.85
      2291637.76     13446846.85
#Sta/Elev= 30
    3809  417.75  3866.7  416.11  3929.4  415.52  4019.7  412.53    4100  411.75
  4150.2  410.14  4227.9  408.86  4340.8  407.55  4561.6   406.5  4594.2   406.5
  4611.8  407.15  4702.1  404.66  4709.6  403.64  4752.2  401.38  4902.8  402.62
    4973   402.4  4993.1  401.97    4997  401.38  4999.8  400.88    5003  401.38
  5023.1  401.97  5053.1  403.97  5103.1  405.35  5173.1   408.3  5213.1  409.45
  5253.1  409.68  5273.1  410.53  5293.1  412.66  5333.1  413.12  5413.1  416.17
#Mann= 3 ,-1 , 0
    3809     .05       0    4997     .03       0    5003     .05       0
Bank Sta=4997,5003
XS Rating Curve= 0 ,0
Exp/Cntr=0.3,0.1

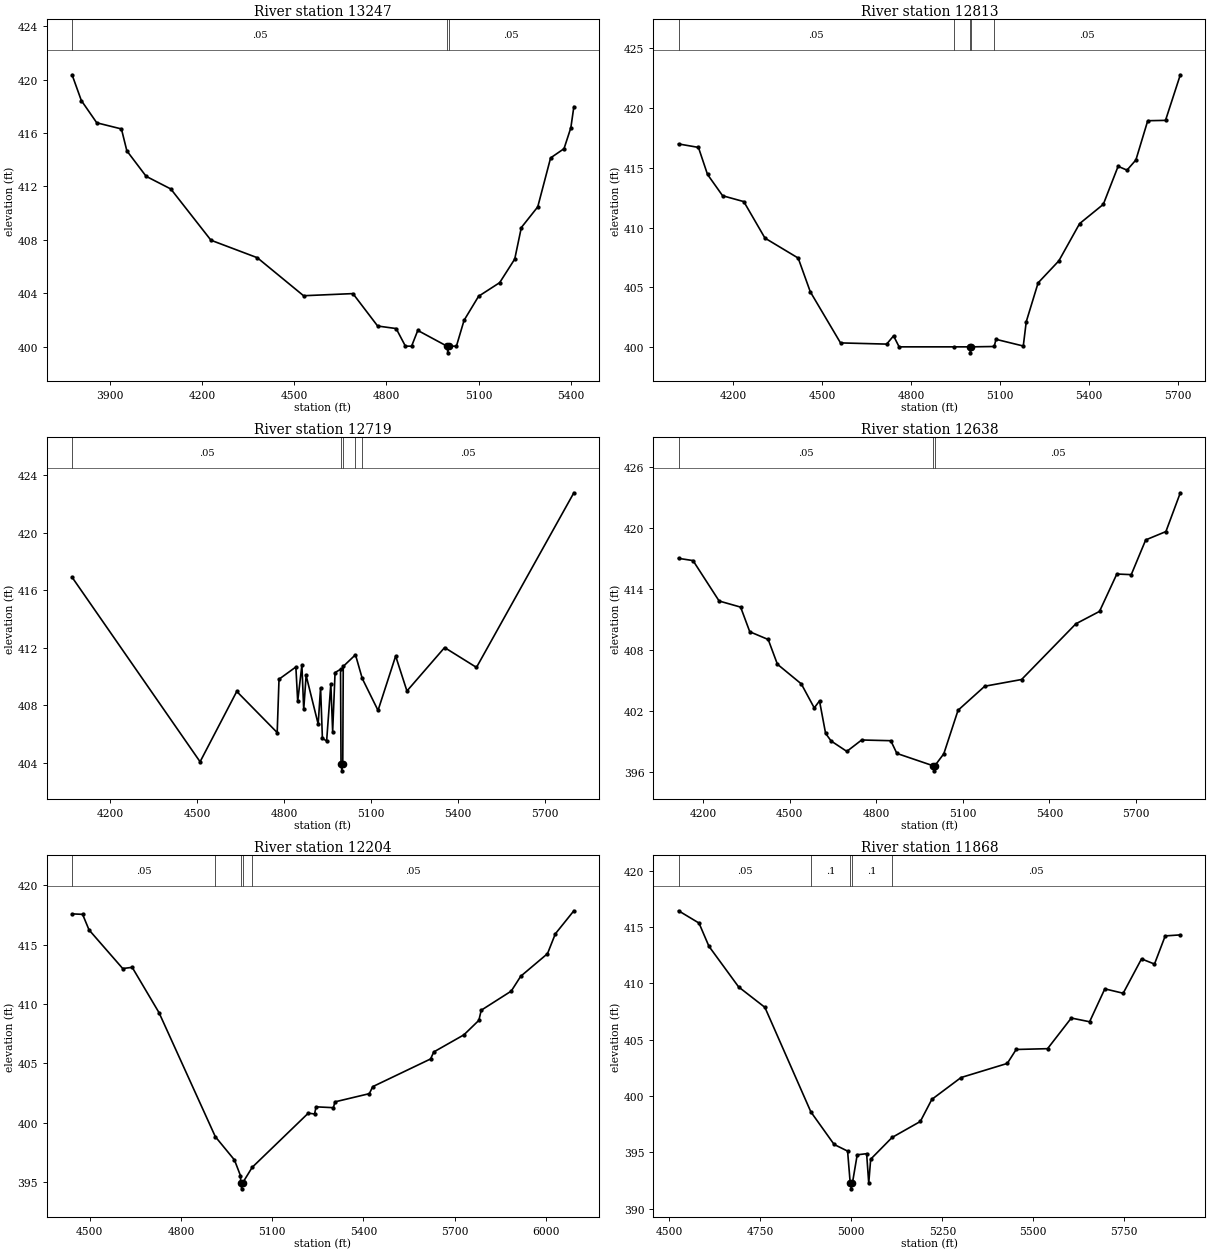
Type RM Length L Ch R = 1 ,13247   ,434,434,434
BEGIN DESCRIPTION:
UNT023 IN SUCR 23.0
END DESCRIPTION:
XS GIS Cut Line= 3
      2293287.69     13446546.85      2292087.72     13446446.85
      2291687.75     13446296.87
#Sta/Elev= 30
  3778.2  420.37  3808.3  418.44  3858.5  416.77  3938.7  416.31  3956.3  414.67
    4019  412.76  4099.3  411.81  4229.7  407.97  4380.3  406.66  4530.8  403.81
  4691.3  403.97  4771.6  401.54  4831.8  401.35  4861.9  400.03    4882  400.03
  4902.1  401.21    4997  400.03  4999.8  399.53    5003  400.03  5027.7  400.03
  5052.6  401.97  5099.8  403.77  5168.3  404.79  5217.3  406.56  5238.7  408.92
  5292.1  410.47  5333.9  414.14  5377.5  414.83  5399.7   416.4  5409.5  417.98
#Mann= 3 ,-1 , 0
  3778.2     .05       0    4997     .03       0    5003     .05       0
Bank Sta=4997,5003
XS Rating Curve= 0 ,0
Exp/Cntr=0.3,0.1

Type RM Length L Ch R = 1 ,12813   ,94,94,94
BEGIN DESCRIPTION:
Mapping XS 72a8d88d
END DESCRIPTION:
XS GIS Cut Line= 5
       2293233.6      13446367.9      2292634.66     13446246.38
      2292448.03     13446185.61      2292165.91     13445981.62
      2291627.69     13445977.28
#Sta/Elev= 30
  4014.5  416.99  4081.7   416.7  4112.3  414.44  4163.3  412.66  4234.8  412.17
  4306.2  409.12  4418.4  407.45  4459.3  404.63  4561.3  400.36  4717.1  400.26
  4740.3  400.95  4759.1  400.03  4942.9  400.03    4997  400.03  4999.8  399.53
    5003  400.03  5080.1  400.06    5086  400.66  5178.2   400.1  5188.2  402.13
  5228.3  405.38  5298.3  407.22  5368.3  410.33  5448.3  411.94  5498.3  415.12
  5528.3   414.8  5558.3  415.65  5598.3  418.93  5658.3  418.96  5708.3  422.77
#Mann= 5 ,-1 , 0
  4014.5     .05       0  4942.9      .1       0    4997     .07       0
    5003      .1       0  5080.1     .05       0
Bank Sta=4997,5003
XS Rating Curve= 0 ,0
Exp/Cntr=0.3,0.1

Type RM Length L Ch R = 1 ,12719   ,81,81,81
BEGIN DESCRIPTION:
UNT023 IN SUCR 22.0
END DESCRIPTION:
XS GIS Cut Line= 6
      2293224.96     13446315.83      2292717.12     13446168.25
      2292543.51     13446146.55      2292365.56       13446012.
      2292226.67     13445881.79      2291611.51     13445890.46
#Sta/Elev= 30
  4068.4   416.9  4510.4  404.07    4637  408.96  4776.6   406.1  4782.9  409.81
  4841.1  410.66  4847.4  408.27  4861.9  410.79  4868.2  407.71  4876.5  410.07
  4918.1  406.69  4926.4  409.22  4932.7  405.71  4947.3  405.51  4961.8  409.48
  4968.1  406.17  4976.4  410.27  4995.3   410.5    4997  403.94  4999.8  403.44
    5003  403.94  5004.7   410.7  5046.9  411.51  5070.3  409.86  5124.8  407.64
  5185.6  411.42  5224.6  408.99  5354.6  412.01  5464.7  410.63  5800.9  422.77
#Mann= 5 ,-1 , 0
  4068.4     .05       0    4997     .03       0    5003     .05       0
  5046.9      .1       0  5070.3     .05       0
Bank Sta=4997,5003
XS Rating Curve= 0 ,0
Exp/Cntr=0.3,0.1

Type RM Length L Ch R = 1 ,12638   ,434,434,434
BEGIN DESCRIPTION:
Mapping XS d89424cd
END DESCRIPTION:
XS GIS Cut Line= 5
      2293242.34     13446276.77      2292669.38     13446090.13
      2292543.51     13446068.43      2292283.09     13445829.71
      2291627.71     13445812.35
#Sta/Elev= 30
  4114.7  416.99  4164.9  416.77  4255.4   412.8  4329.9   412.2  4361.6  409.78
  4425.5  409.02  4457.4  406.59  4540.2  404.66  4585.1   402.3  4603.3  402.99
  4624.4   399.8  4643.6  399.05    4698  398.03  4749.4  399.15  4850.4  399.08
  4871.4  397.83    4997  396.62  4999.8  396.12    5003  396.62  5034.2   397.8
  5083.5  402.07    5176  404.43  5303.7  405.09  5491.8  410.56  5573.8  411.78
  5633.8  415.45  5683.8  415.39  5733.9   418.8  5803.9  419.62  5853.9  423.43
#Mann= 3 ,-1 , 0
  4114.7     .05       0    4997     .03       0    5003     .05       0
Bank Sta=4997,5003
XS Rating Curve= 0 ,0
Exp/Cntr=0.3,0.1

Type RM Length L Ch R = 1 ,12204   ,336,336,336
BEGIN DESCRIPTION:
UNT023 IN SUCR 21.0
END DESCRIPTION:
XS GIS Cut Line= 4
      2293350.43     13446006.13      2293101.39      13445920.1
      2292222.89     13445612.17      2291792.69     13445462.73
#Sta/Elev= 30
  4442.2  417.59  4476.8  417.55    4498  416.24  4608.7  412.99  4639.9  413.09
    4728  409.28  4913.2  398.84  4976.1  396.88  4995.7  395.57    4997  394.95
  4999.8  394.45    5003  394.95  5034.4  396.26  5218.9  400.82  5239.3  400.75
  5244.6  401.35  5301.3  401.28  5306.6  401.77  5419.5  402.46  5430.7  403.05
  5620.9  405.38  5631.4  405.97  5730.5  407.41  5779.7  408.63  5787.4  409.48
  5886.1  411.09  5917.3  412.34  6005.3  414.24  6031.1  415.91    6092  417.85
#Mann= 5 ,-1 , 0
  4442.2     .05       0  4913.2      .1       0    4997     .07       0
    5003      .1       0  5034.4     .05       0
Bank Sta=4997,5003
XS Rating Curve= 0 ,0
Exp/Cntr=0.3,0.1

Type RM Length L Ch R = 1 ,11868   ,462,462,462
BEGIN DESCRIPTION:
UNT023 IN SUCR 20.0
END DESCRIPTION:
XS GIS Cut Line= 4
      2293382.14     13445652.93      2293187.42     13445603.12
      2292476.48     13445367.65       2292127.8     13445118.59
#Sta/Elev= 30
  4525.4  416.44  4581.6  415.35  4608.9  413.29  4690.5  409.68  4762.6  407.87
  4888.9  398.59  4952.8   395.7  4989.8  395.11    4997  392.26  4999.8  391.76
    5003  392.26  5016.2  394.78  5042.1  394.88  5047.9  392.26  5053.2  394.39
    5112  396.32  5189.6  397.74  5221.2   399.7  5301.5  401.64  5428.4  402.89
  5452.9  404.13  5539.1   404.2  5604.3  406.92  5654.6  406.59  5696.4  409.51
  5746.8  409.12  5797.2  412.17  5832.8  411.71  5862.3  414.21  5903.8   414.3
#Mann= 5 ,-1 , 0
  4525.4     .05       0  4888.9      .1       0    4997     .07       0
    5003      .1       0    5112     .05       0
Bank Sta=4997,5003
XS Rating Curve= 0 ,0
Exp/Cntr=0.3,0.1