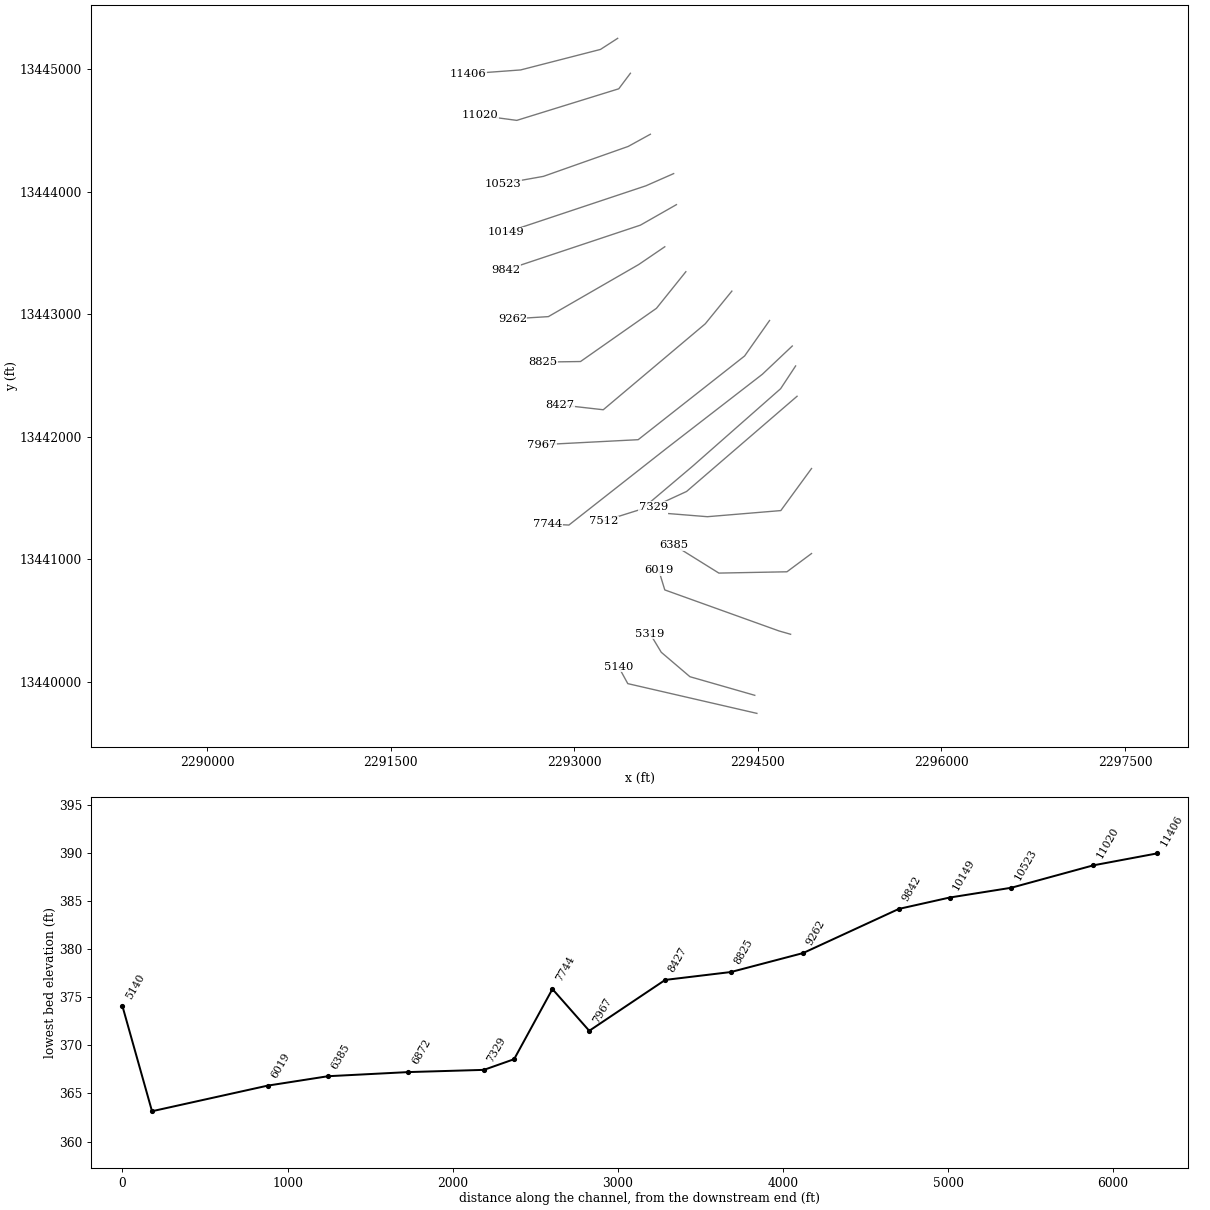
HEC-RAS study UNT023 IN SUCR.prj: UNT023 IN SUCR Base Level Engineering

--- UNT023 IN SUCR.g01 (geometry) --- (continued)

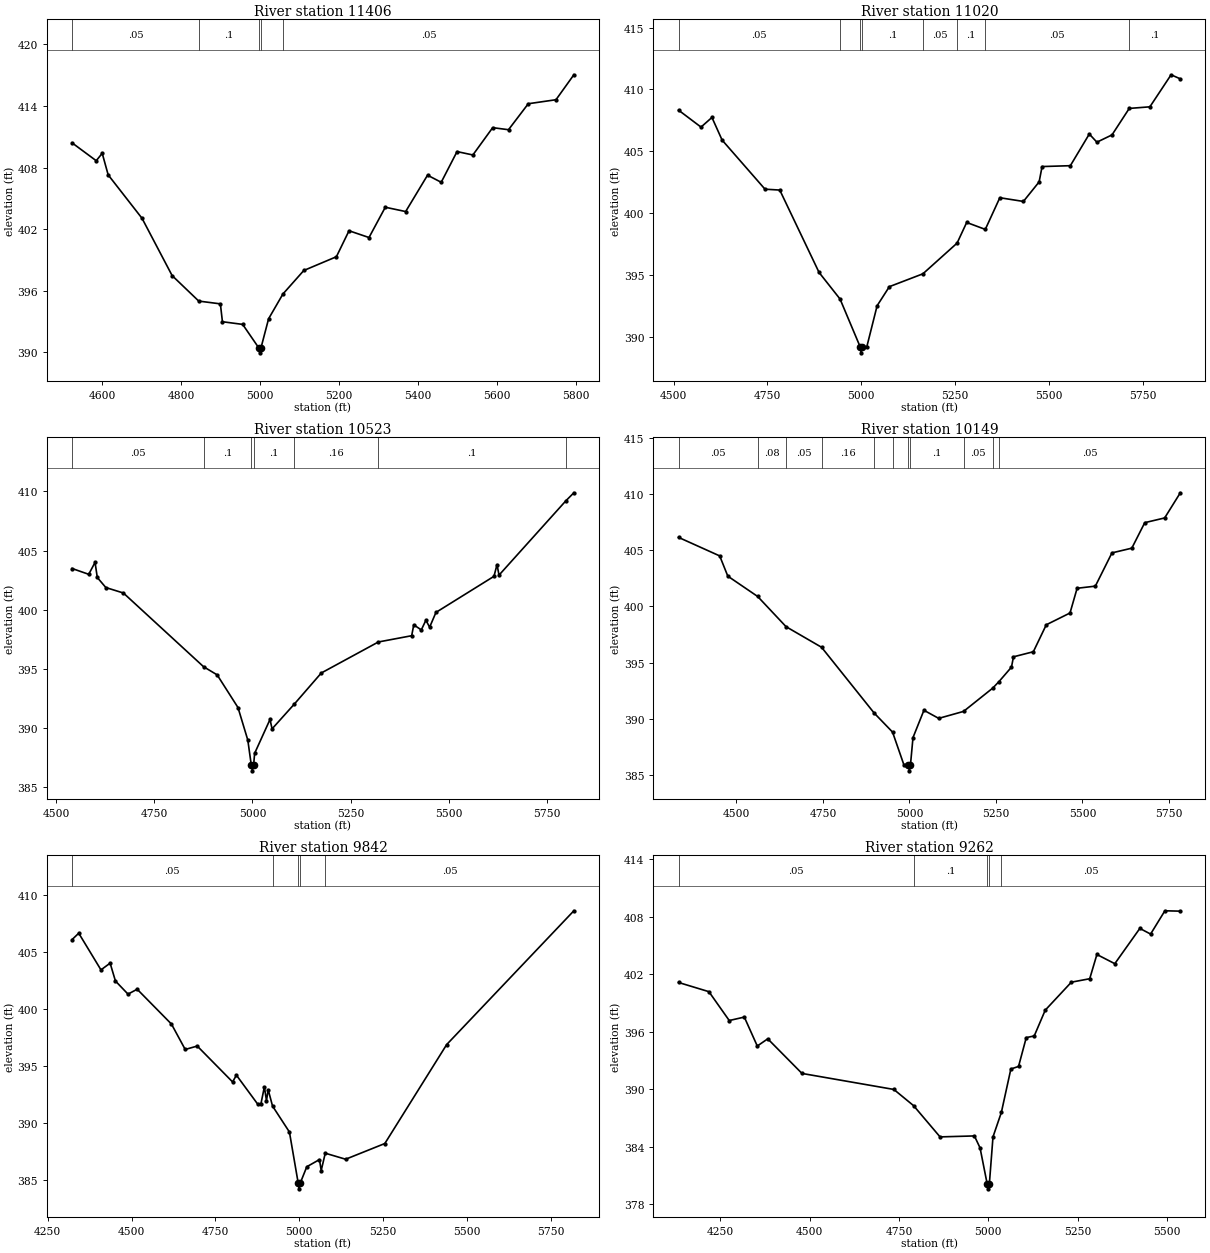
Type RM Length L Ch R = 1 ,11406   ,386,386,386
BEGIN DESCRIPTION:
UNT023 IN SUCR 19.0
END DESCRIPTION:
XS GIS Cut Line= 4
      2293355.01     13445254.46      2293214.59     13445163.87
      2292562.52     13444996.32      2292132.54     13444964.64
#Sta/Elev= 30
  4524.2   410.4  4585.4  408.66  4600.6  409.38  4615.7  407.28  4701.5  403.05
  4777.8  397.47  4845.2  394.99    4900  394.72  4905.2  392.98  4956.5  392.72
    4997  390.45  4999.8  389.95    5003  390.45  5022.2  393.27  5058.5  395.68
  5111.4  397.97    5194  399.31    5226  401.84  5276.6  401.18  5317.9  404.13
  5369.5  403.71  5424.9  407.25  5459.6  406.56  5499.7  409.55  5539.8  409.22
    5590  411.88  5630.1  411.68  5680.2  414.21  5750.4   414.6  5795.7  417.03
#Mann= 5 ,-1 , 0
  4524.2     .05       0  4845.2      .1       0    4997     .07       0
    5003      .1       0  5058.5     .05       0
Bank Sta=4997,5003
XS Rating Curve= 0 ,0
Exp/Cntr=0.3,0.1

Type RM Length L Ch R = 1 ,11020   ,497,497,497
BEGIN DESCRIPTION:
UNT023 IN SUCR 18.0
END DESCRIPTION:
XS GIS Cut Line= 4
       2293459.1     13444969.13      2293364.03     13444842.36
      2292530.82     13444584.25      2292227.37     13444625.01
#Sta/Elev= 30
  4513.3  408.33  4573.2  406.96  4602.3  407.74  4629.4  405.91  4743.7  401.94
    4783  401.87  4887.7  395.21  4943.6  393.06    4997  389.21  4999.8  388.71
    5003  389.21    5015  389.21  5042.4  392.52    5075  394.06  5164.4   395.1
  5255.4  397.58    5281  399.25  5330.6  398.69  5369.3  401.25  5432.1  400.95
    5474  402.53  5481.9  403.77  5557.2  403.84  5607.7   406.4  5627.9  405.74
  5668.2  406.33  5714.1  408.47  5769.1   408.6  5825.6  411.19  5850.2  410.86
#Mann= 8 ,-1 , 0
  4513.3     .05       0  4943.6      .1       0    4997     .07       0
    5003      .1       0  5164.4     .05       0  5255.4      .1       0
  5330.6     .05       0  5714.1      .1       0
Bank Sta=4997,5003
XS Rating Curve= 0 ,0
Exp/Cntr=0.3,0.1

Type RM Length L Ch R = 1 ,10523   ,374,374,374
BEGIN DESCRIPTION:
UNT023 IN SUCR 17.0
END DESCRIPTION:
XS GIS Cut Line= 4
      2293622.12     13444471.03      2293441.01     13444371.42
      2292748.18     13444126.89       2292417.6     13444068.02
#Sta/Elev= 30
  4540.9  403.48  4583.3  402.99  4599.4     404  4605.1  402.72  4626.9  401.87
  4671.5  401.41  4875.6  395.18  4910.2  394.49  4963.2  391.73  4988.2  388.98
    4997  386.88  4999.8  386.38    5003  386.88  5005.6  387.86  5044.7  390.72
    5050  389.93  5106.8  392.03  5175.3  394.65  5320.5  397.27  5405.3   397.8
  5410.6  398.72  5429.8  398.29  5441.5  399.11    5451  398.52  5467.1  399.77
  5614.8  402.82  5622.5  403.81  5627.6  402.92  5797.7   409.2  5818.1  409.88
#Mann= 7 ,-1 , 0
  4540.9     .05       0  4875.6      .1       0    4997     .07       0
    5003      .1       0  5106.8     .16       0  5320.5      .1       0
  5797.7     .05       0
Bank Sta=4997,5003
XS Rating Curve= 0 ,0
Exp/Cntr=0.3,0.1

Type RM Length L Ch R = 1 ,10149   ,307,307,307
BEGIN DESCRIPTION:
UNT023 IN SUCR 16.0
END DESCRIPTION:
XS GIS Cut Line= 3
      2293812.29     13444149.51      2293585.91     13444049.91
      2292444.76     13443669.52
#Sta/Elev= 30
  4332.8  406.14  4451.8  404.49  4475.2  402.69  4561.5  400.88  4643.6  398.19
  4746.1  396.36  4898.3   390.5  4951.3  388.81  4984.5  385.86    4997  385.86
  4999.8  385.36    5003  385.86  5010.4  388.32    5042  390.75  5084.7  390.03
  5156.5  390.65  5240.7  392.72  5259.1  393.31    5295  394.59  5300.8  395.51
  5358.2  395.96  5395.6  398.36  5464.2  399.41  5484.7  401.61  5537.4   401.8
  5585.4  404.76  5642.8  405.18  5680.2  407.45  5737.7  407.87    5783  410.11
#Mann= 11 ,-1 , 0
  4332.8     .05       0  4561.5     .08       0  4643.6     .05       0
  4746.1     .16       0  4898.3     .05       0  4951.3      .1       0
    4997     .07       0    5003      .1       0  5156.5     .05       0
  5240.7      .1       0  5259.1     .05       0
Bank Sta=4997,5003
XS Rating Curve= 0 ,0
Exp/Cntr=0.3,0.1

Type RM Length L Ch R = 1 ,9842    ,580,580,580
BEGIN DESCRIPTION:
UNT023 IN SUCR 15.0
END DESCRIPTION:
XS GIS Cut Line= 3
        2293835.     13443895.96      2293540.63      13443728.4
      2292441.88     13443362.15
#Sta/Elev= 30
  4322.4  406.07  4342.3  406.63  4408.6  403.41  4435.9     404  4451.8  402.43
  4489.3  401.28  4516.6  401.71  4618.9  398.65  4659.9  396.42  4695.8  396.72
  4801.2  393.57  4812.7  394.16  4875.9  391.63  4885.5   391.6  4896.1  393.14
  4902.3  391.93  4907.5  392.88  4920.4  391.45  4970.8  389.17    4997  384.68
  4999.8  384.18    5003  384.68  5022.6  386.12  5060.4  386.75  5065.6  385.79
  5077.7  387.31  5138.5  386.78  5255.4  388.16  5439.9  396.85  5819.3   408.6
#Mann= 5 ,-1 , 0
  4322.4     .05       0  4920.4      .1       0    4997     .07       0
    5003      .1       0  5077.7     .05       0
Bank Sta=4997,5003
XS Rating Curve= 0 ,0
Exp/Cntr=0.3,0.1

Type RM Length L Ch R = 1 ,9262    ,437,437,437
BEGIN DESCRIPTION:
UNT023 IN SUCR 14.0
END DESCRIPTION:
XS GIS Cut Line= 4
      2293739.89     13443551.81      2293527.05     13443406.89
      2292788.93     13442981.23      2292494.64     13442963.12
#Sta/Elev= 30
  4133.1  401.12  4218.1  400.16    4275  397.15  4317.2  397.51  4353.5  394.49
  4382.8  395.24  4478.6  391.63  4735.7  389.96  4790.9  388.27    4865  385.01
  4961.2  385.11    4977  383.86    4997  380.09  4999.8  379.59    5003  380.09
  5013.2  385.01  5036.6  387.56  5063.2  392.09  5084.7  392.36  5106.3  395.37
  5128.6  395.54  5159.4  398.23  5232.5  401.15  5283.9  401.51    5304  404.04
  5354.1  403.08  5424.2  406.76  5454.3  406.17  5494.3   408.6  5537.5  408.56
#Mann= 5 ,-1 , 0
  4133.1     .05       0  4790.9      .1       0    4997     .07       0
    5003      .1       0  5036.6     .05       0
Bank Sta=4997,5003
XS Rating Curve= 0 ,0
Exp/Cntr=0.3,0.1

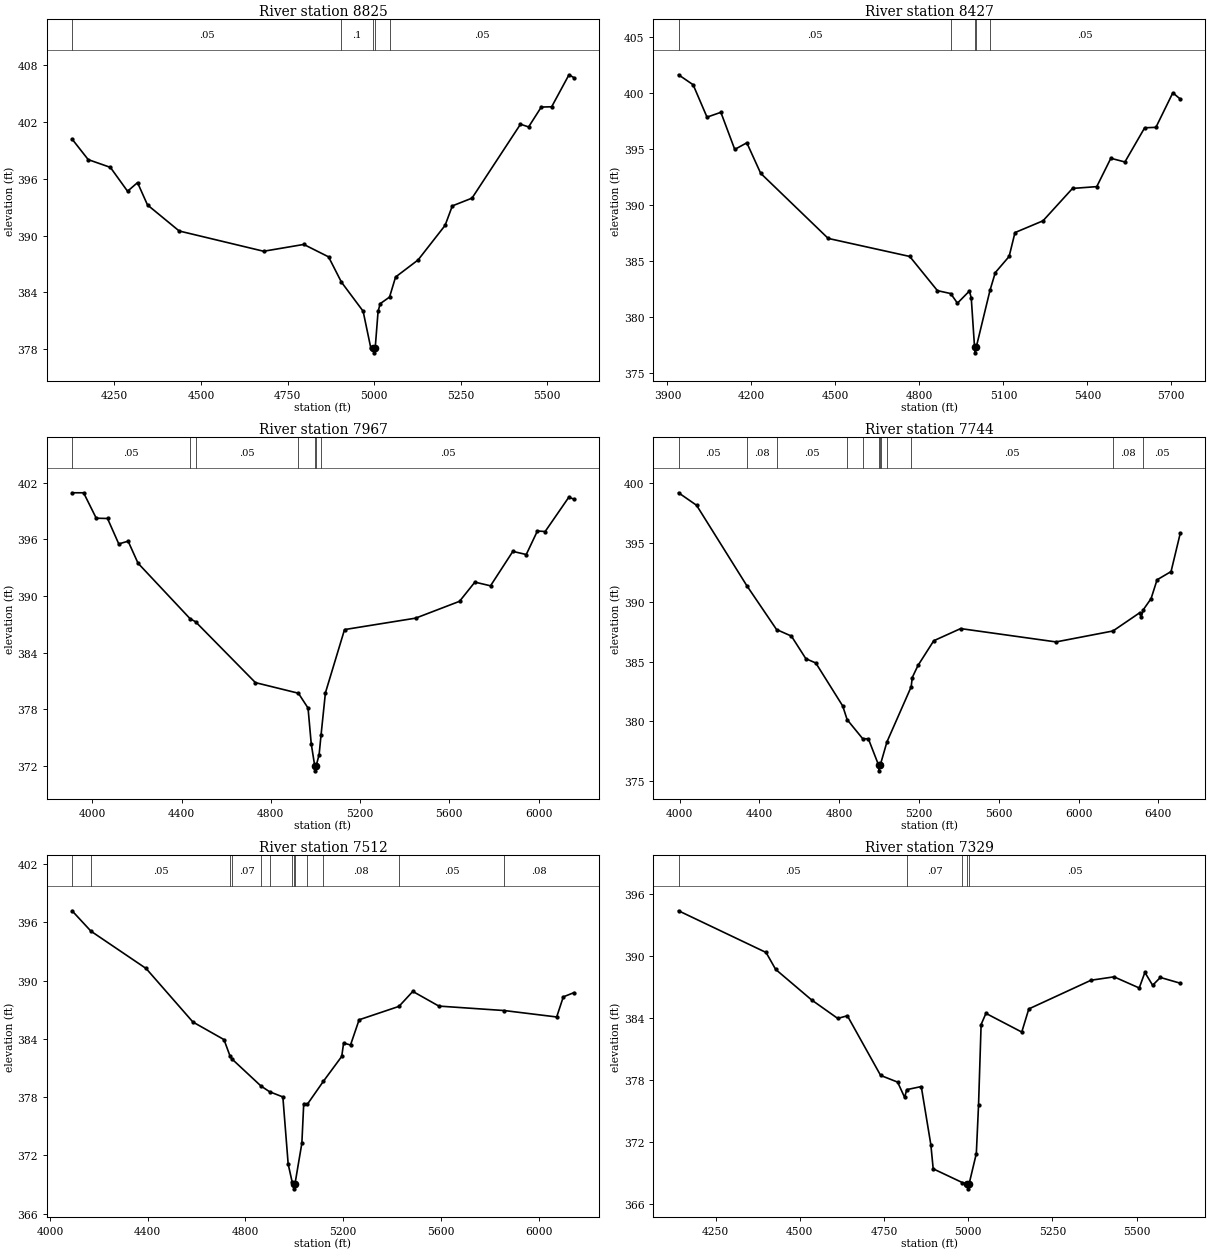
Type RM Length L Ch R = 1 ,8825    ,398,398,398
BEGIN DESCRIPTION:
UNT023 IN SUCR 13.1
END DESCRIPTION:
XS GIS Cut Line= 4
      2293911.96     13443348.04      2293671.95     13443049.15
      2293051.57     13442614.44      2292743.66     13442609.91
#Sta/Elev= 30
  4127.8   400.2  4174.4  398.03  4238.4  397.21    4288  394.69  4316.8   395.6
  4345.6  393.24  4437.1  390.49  4680.9  388.35  4796.8  389.07  4868.3  387.76
  4905.5  385.09  4968.1  382.02  4990.4  378.12    4997  378.12  4999.8  377.62
    5003  378.12  5011.3  381.99  5017.4  382.81  5044.4  383.51  5061.9  385.63
  5126.8  387.43  5204.8  391.08  5225.7  393.14  5282.5  393.96  5422.5  401.77
  5445.9  401.48  5482.5  403.58  5512.5  403.61  5562.5  406.99  5576.6  406.69
#Mann= 5 ,-1 , 0
  4127.8     .05       0  4905.5      .1       0    4997     .07       0
    5003      .1       0  5044.4     .05       0
Bank Sta=4997,5003
XS Rating Curve= 0 ,0
Exp/Cntr=0.3,0.1

Type RM Length L Ch R = 1 ,8427    ,460,460,460
BEGIN DESCRIPTION:
UNT023 IN SUCR 12.1
END DESCRIPTION:
XS GIS Cut Line= 4
      2294287.82     13443189.55      2294070.44     13442922.36
      2293237.23     13442220.47      2292881.12     13442261.04
#Sta/Elev= 30
  3939.7  401.61  3991.8  400.72  4041.4  397.83  4090.9  398.26  4140.5  394.95
  4183.6  395.54  4233.1  392.82  4474.2  387.01  4765.5   385.4  4864.4  382.35
  4911.7  382.09  4935.9  381.23  4978.8  382.32  4985.3  381.69    4997   377.3
  4999.8   376.8    5003   377.3  5052.1  382.37  5071.1  383.96  5120.5   385.4
  5141.4  387.53  5241.5  388.58  5346.9  391.47  5433.5  391.63  5483.8  394.16
  5534.1  393.83  5604.6  396.88  5644.8  396.92  5705.2     400    5732  399.44
#Mann= 5 ,-1 , 0
  3939.7     .05       0  4911.7      .1       0    4997     .07       0
    5003      .1       0  5052.1     .05       0
Bank Sta=4997,5003
XS Rating Curve= 0 ,0
Exp/Cntr=0.3,0.1

Type RM Length L Ch R = 1 ,7967    ,223,223,223
BEGIN DESCRIPTION:
Mapping XS 5a12d65d
END DESCRIPTION:
XS GIS Cut Line= 4
      2294595.74     13442949.55      2294391.95     13442659.72
      2293522.52     13441975.95      2292734.58     13441935.19
#Sta/Elev= 30
  3909.1  400.92  3960.8  400.92  4017.5  398.23    4068   398.2  4118.5  395.51
  4160.4   395.8  4204.8  393.47  4438.2   387.6  4462.5  387.28  4731.1  380.84
  4923.6  379.72  4966.9  378.15  4981.2  374.38    4997  372.01  4999.8  371.51
    5003  372.01  5016.6  373.23    5025  375.25  5044.8  379.76  5130.5  386.45
  5449.1  387.66    5646  389.44  5714.8  391.47  5784.9  391.08    5885  394.72
  5945.1  394.39  5995.1  396.88  6029.8  396.82  6135.3  400.43  6158.5  400.26
#Mann= 7 ,-1 , 0
  3909.1     .05       0  4438.2     .08       0  4462.5     .05       0
  4923.6      .1       0    4997     .07       0    5003      .1       0
    5025     .05       0
Bank Sta=4997,5003
XS Rating Curve= 0 ,0
Exp/Cntr=0.3,0.1

Type RM Length L Ch R = 1 ,7744    ,232,232,232
BEGIN DESCRIPTION:
UNT023 IN SUCR 11.1
END DESCRIPTION:
XS GIS Cut Line= 5
      2294781.35      13442741.2      2294536.86     13442510.29
      2293757.99     13441908.02      2292956.48     13441278.59
      2292781.29     13441287.57
#Sta/Elev= 30
  3994.6  399.21    4085  398.16  4336.7  391.41    4486  387.72  4560.4  387.17
  4632.9  385.27  4682.7  384.91  4817.6   381.3  4839.8  380.15  4917.8  378.55
  4946.2  378.54    4997  376.35  4999.8  375.85    5003  376.35  5007.5  376.43
  5039.3  378.28  5160.8  382.91  5166.2  383.69  5195.2  384.71    5274  386.78
  5408.8   387.8  5886.9  386.68  6172.4   387.6  6307.2  389.14  6313.5  388.75
    6325   389.4  6363.4  390.32  6393.4   391.9  6463.5  392.59    6510  395.83
#Mann= 12 ,-1 , 0
  3994.6     .05       0  4336.7     .08       0    4486     .05       0
  4839.8     .08       0  4917.8     .05       0    4997     .03       0
    5003     .05       0  5007.5     .08       0  5039.3      .1       0
  5160.8     .05       0  6172.4     .08       0    6325     .05       0
Bank Sta=4997,5003
XS Rating Curve= 0 ,0
Exp/Cntr=0.3,0.1

Type RM Length L Ch R = 1 ,7512    ,183,183,183
BEGIN DESCRIPTION:
Mapping XS 3a0e27c6
END DESCRIPTION:
XS GIS Cut Line= 5
      2294808.54     13442578.19      2294686.29     13442392.55
      2293966.29     13441758.59      2293554.22     13441409.91
      2293237.21     13441310.28
#Sta/Elev= 30
  4090.7  397.18    4168  395.08  4393.7  391.24  4585.3  385.73  4712.5  383.92
  4736.4  382.28  4744.9  381.93    4864  379.14  4899.4  378.55  4953.4  378.02
  4975.2   371.1  4991.6  369.25    4997  369.06  4999.8  368.56    5003  369.06
  5031.2  373.26  5038.8  377.33  5053.8  377.27  5119.3  379.63  5194.4  382.19
    5202  383.56  5230.4  383.37  5265.5  385.96  5428.6  387.34  5485.3  388.88
  5591.9  387.37  5859.9  386.91  6074.1  386.25  6101.2  388.32  6144.4  388.75
#Mann= 13 ,-1 , 0
  4090.7     .08       0    4168     .05       0  4736.4      .1       0
  4744.9     .07       0    4864     .08       0  4899.4     .07       0
  4991.6      .1       0    4997     .07       0    5003      .1       0
  5053.8     .05       0  5119.3     .08       0  5428.6     .05       0
  5859.9     .08       0
Bank Sta=4997,5003
XS Rating Curve= 0 ,0
Exp/Cntr=0.3,0.1

Type RM Length L Ch R = 1 ,7329    ,457,457,457
BEGIN DESCRIPTION:
UNT023 IN SUCR 10.1
END DESCRIPTION:
XS GIS Cut Line= 3
      2294820.53      13442330.7      2293917.74     13441552.91
      2293646.93     13441427.92
#Sta/Elev= 30
  4140.1  394.39    4400  390.35  4428.5  388.71  4534.9  385.76  4612.8  383.96
  4641.4  384.22  4740.1  378.44  4790.6  377.79  4811.4  376.31  4817.7  377.06
  4860.8  377.36  4889.3  371.72  4896.2  369.39  4983.2  368.05    4997  367.95
  4999.8  367.45    5003  367.95  5024.3  370.87  5030.9  375.59  5038.5  383.37
  5052.8  384.45  5159.2  382.64  5180.1  384.88  5364.8  387.66  5433.1  387.99
    5508  386.91  5524.8  388.42  5547.8  387.17  5570.7  387.93    5630  387.37
#Mann= 5 ,-1 , 0
  4140.1     .05       0  4817.7     .07       0  4983.2     .05       0
    4997     .03       0    5003     .05       0
Bank Sta=4997,5003
XS Rating Curve= 0 ,0
Exp/Cntr=0.3,0.1

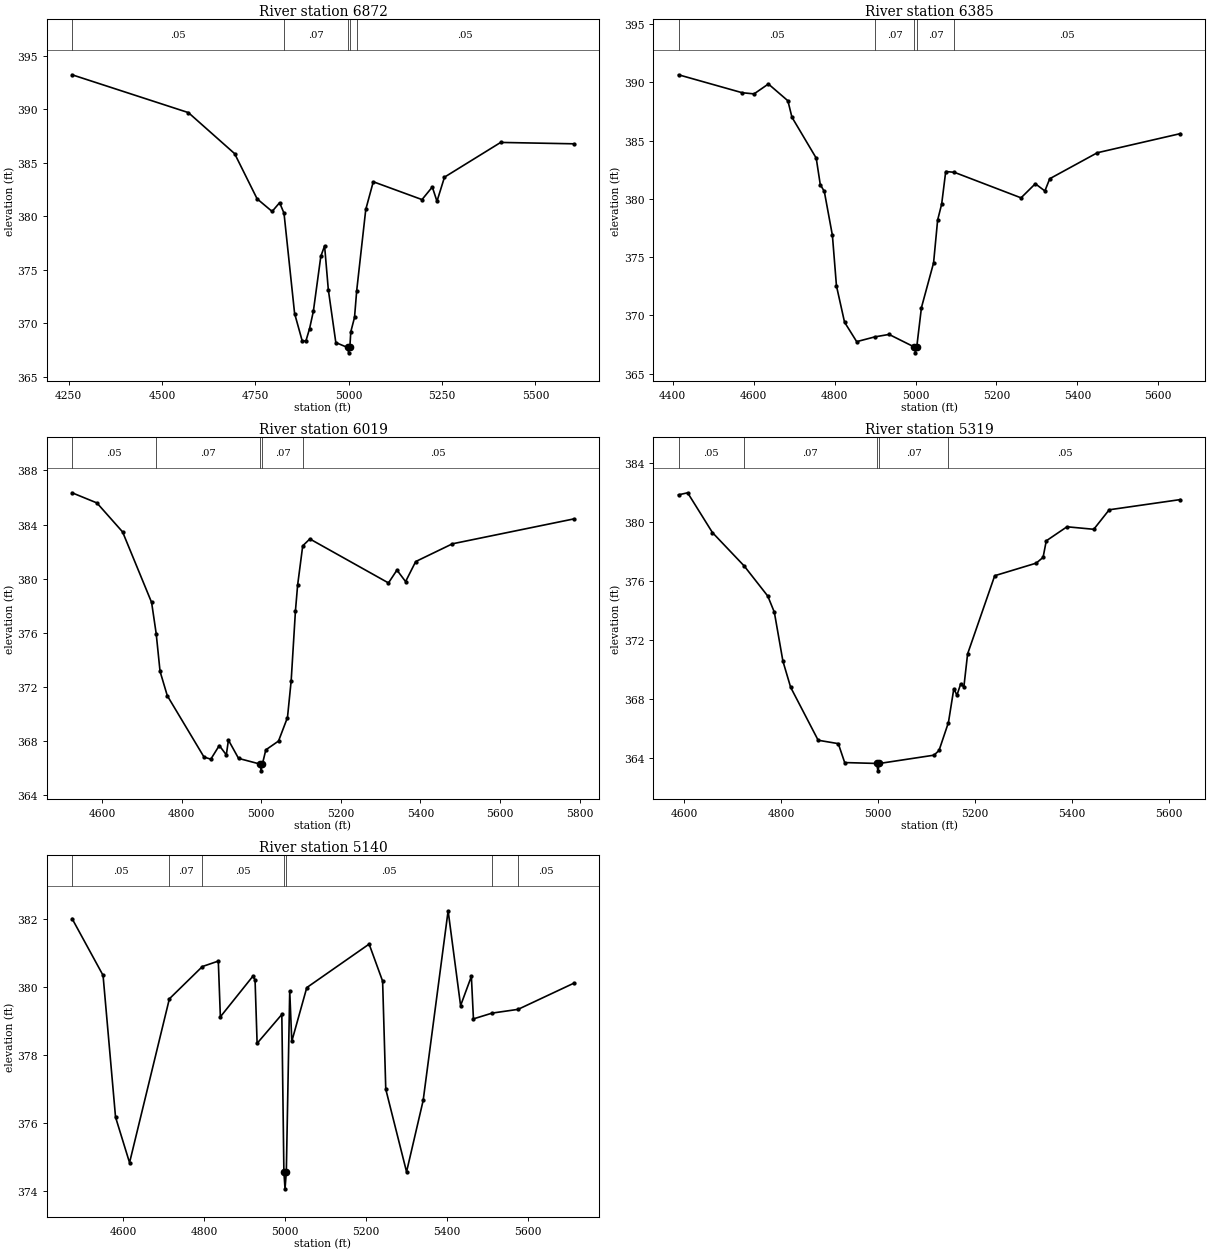
Type RM Length L Ch R = 1 ,6872    ,487,487,487
BEGIN DESCRIPTION:
UNT023 IN SUCR 9.1
END DESCRIPTION:
XS GIS Cut Line= 4
      2294938.57     13441740.42      2294687.72     13441396.85
      2294087.72     13441346.85      2293772.32     13441372.32
#Sta/Elev= 30
  4259.1  393.24  4570.6   389.7  4694.5  385.86  4754.7  381.63  4794.9  380.45
  4814.9  381.27  4826.7  380.29  4855.1   370.9  4875.2  368.37  4885.2  368.31
  4895.2  369.49  4905.3   371.1  4925.3  376.25  4935.4  377.23  4945.4  373.13
  4965.5  368.18    4997  367.72  4999.8  367.22    5003  367.72  5005.6  369.19
  5015.6  370.54  5021.4  373.04  5045.7  380.64  5065.8  383.23  5196.3  381.56
  5223.9  382.74  5236.4   381.4  5256.5  383.66    5407  386.91    5603  386.78
#Mann= 5 ,-1 , 0
  4259.1     .05       0  4826.7     .07       0    4997     .07       0
    5003     .07       0  5021.4     .05       0
Bank Sta=4997,5003
XS Rating Curve= 0 ,0
Exp/Cntr=0.3,0.1

Type RM Length L Ch R = 1 ,6385    ,366,366,366
BEGIN DESCRIPTION:
UNT023 IN SUCR 8.1
END DESCRIPTION:
XS GIS Cut Line= 4
      2294938.59     13441045.98      2294737.72     13440896.85
      2294181.63     13440886.25       2293813.6      13441115.4
#Sta/Elev= 30
  4414.4  390.65  4571.7  389.11    4601  389.01  4636.4  389.86  4684.6  388.42
  4694.6  387.01  4754.6   383.5  4764.6  381.23  4774.6  380.64  4794.6  376.87
  4804.6  372.54  4824.6  369.42  4854.6  367.75  4899.5  368.16  4934.6  368.37
    4997  367.29  4999.8  366.79    5003  367.29  5014.6  370.67  5044.6  374.51
  5054.6  378.18  5064.6  379.56  5074.6  382.35    5096  382.28  5260.7  380.09
    5296   381.3  5319.6  380.68  5331.6  381.73  5449.2  383.96  5654.3   385.6
#Mann= 5 ,-1 , 0
  4414.4     .05       0  4899.5     .07       0    4997     .07       0
    5003     .07       0    5096     .05       0
Bank Sta=4997,5003
XS Rating Curve= 0 ,0
Exp/Cntr=0.3,0.1

Type RM Length L Ch R = 1 ,6019    ,700,700,700
BEGIN DESCRIPTION:
UNT023 IN SUCR 7.1
END DESCRIPTION:
XS GIS Cut Line= 4
      2294767.76     13440386.52      2294672.71     13440413.68
      2293739.88     13440748.77      2293690.07     13440911.79
#Sta/Elev= 30
  4524.9  386.35  4587.3   385.6  4651.8  383.46  4724.7  378.25  4736.2  375.95
  4745.9  373.16  4764.1  371.36  4856.3  366.83  4873.4  366.67  4894.7  367.68
  4912.4  366.99  4917.7  368.08  4943.1  366.73    4997  366.31  4999.8  365.81
    5003  366.31  5011.6  367.36  5043.5  368.01    5066  369.75  5075.3  372.47
    5086  377.62  5091.5  379.53  5104.3  382.43  5122.2  382.94  5319.7  379.69
    5341  380.64  5362.7  379.79  5388.1  381.27  5480.3  382.58  5785.4  384.42
#Mann= 5 ,-1 , 0
  4524.9     .05       0  4736.2     .07       0    4997     .07       0
    5003     .07       0  5104.3     .05       0
Bank Sta=4997,5003
XS Rating Curve= 0 ,0
Exp/Cntr=0.3,0.1

Type RM Length L Ch R = 1 ,5319    ,179,179,179
BEGIN DESCRIPTION:
UNT023 IN SUCR 6.3
END DESCRIPTION:
XS GIS Cut Line= 4
      2294474.96     13439887.86      2293945.42     13440039.78
      2293711.05     13440239.43      2293619.32     13440391.64
#Sta/Elev= 30
  4587.9  381.82  4606.7  381.96  4657.9  379.27  4723.5  377.01  4772.3  374.97
  4785.8  373.88  4803.5  370.57  4819.5   368.8  4876.3  365.22  4917.9  364.99
  4931.1  363.71    4997  363.65  4999.8  363.15    5003  363.65  5115.6  364.21
    5126  364.53  5145.4  366.42  5156.5   368.7    5163  368.27  5170.7  369.03
  5177.3  368.83    5185  371.06    5241  376.35  5326.7   377.2  5340.9  377.59
  5347.5  378.71  5390.3  379.66  5445.6  379.49  5477.5  380.81  5624.4   381.5
#Mann= 5 ,-1 , 0
  4587.9     .05       0  4723.5     .07       0    4997     .07       0
    5003     .07       0  5145.4     .05       0
Bank Sta=4997,5003
XS Rating Curve= 0 ,0
Exp/Cntr=0.3,0.1

Type RM Length L Ch R = 1 ,5140    ,121,121,121
BEGIN DESCRIPTION:
Mapping XS 3ade6ca1
END DESCRIPTION:
XS GIS Cut Line= 3
      2294492.31      13439740.3      2293437.61     13439983.36
      2293362.54     13440120.51
#Sta/Elev= 30
  4474.1  382.02  4550.6  380.35  4581.4  376.18    4616  374.84  4714.3  379.66
  4795.8  380.61  4835.1  380.77  4840.2  379.13  4920.1  380.32  4925.8  380.22
  4930.9  378.35  4991.9   379.2    4997  374.57  4999.8  374.07    5003  374.57
  5011.4  379.89  5016.5  378.41  5053.5  379.99  5207.4  381.27  5240.7  380.18
  5248.5     377  5299.8  374.57  5340.8  376.67  5402.4  382.25  5433.2  379.46
  5459.8  380.32  5464.9  379.07  5511.1  379.24  5575.1  379.35  5712.8  380.12
#Mann= 7 ,-1 , 0
  4474.1     .05       0  4714.3     .07       0  4795.8     .05       0
    4997     .03       0    5003     .05       0  5511.1      .1       0
  5575.1     .05       0
Bank Sta=4997,5003
XS Rating Curve= 0 ,0
Exp/Cntr=0.3,0.1