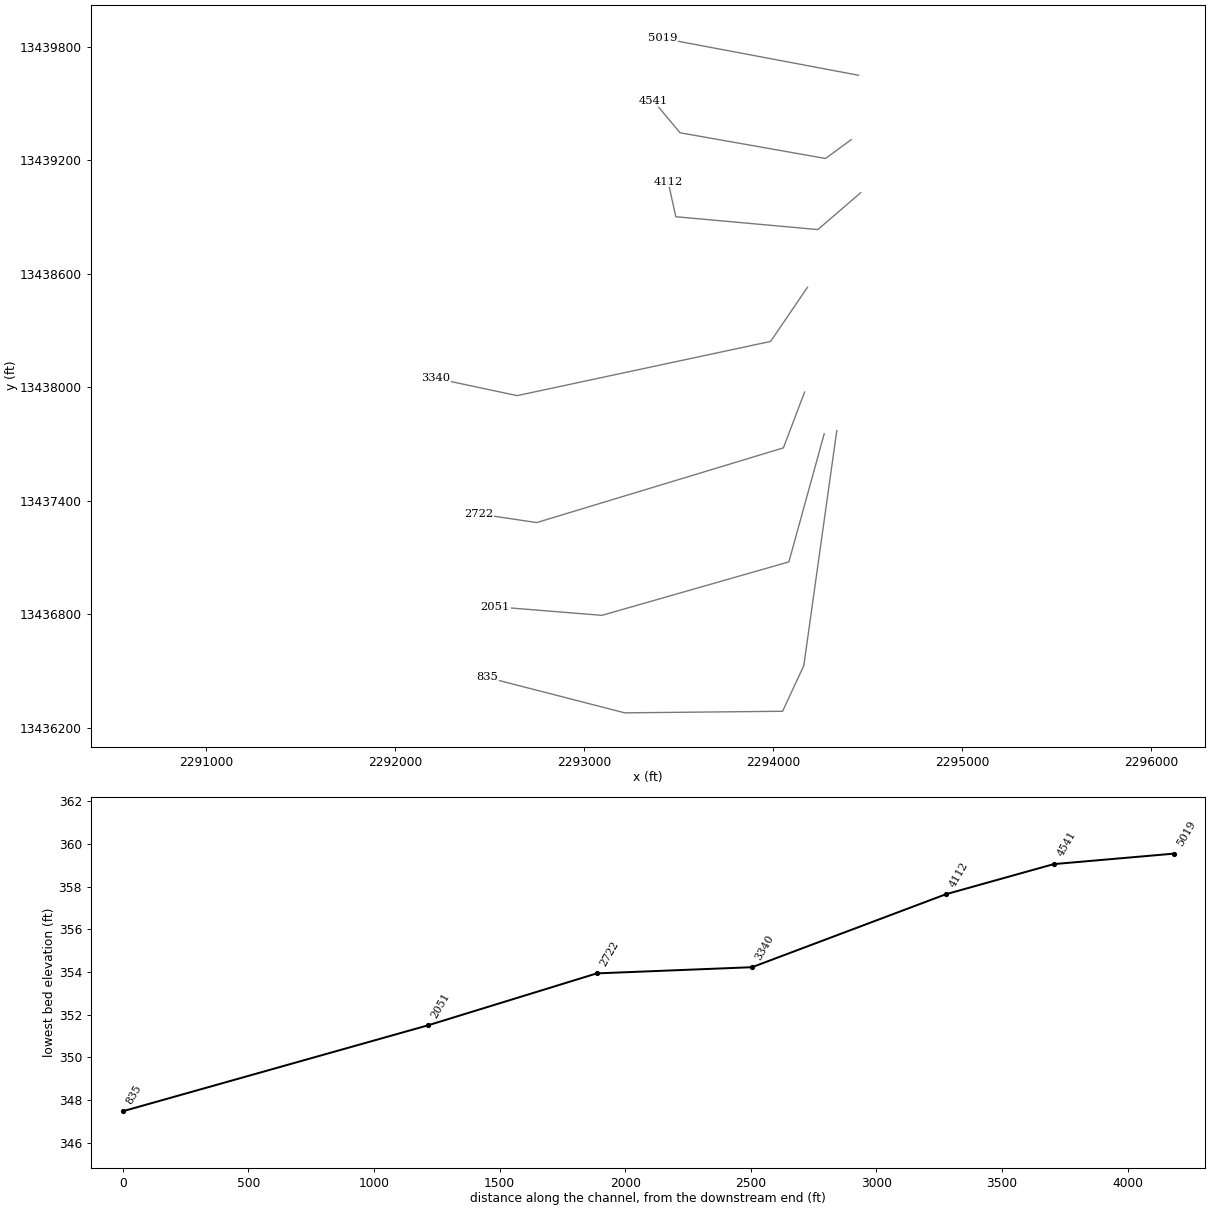
HEC-RAS study UNT023 IN SUCR.prj: UNT023 IN SUCR Base Level Engineering

--- UNT023 IN SUCR.g01 (geometry) --- (continued)

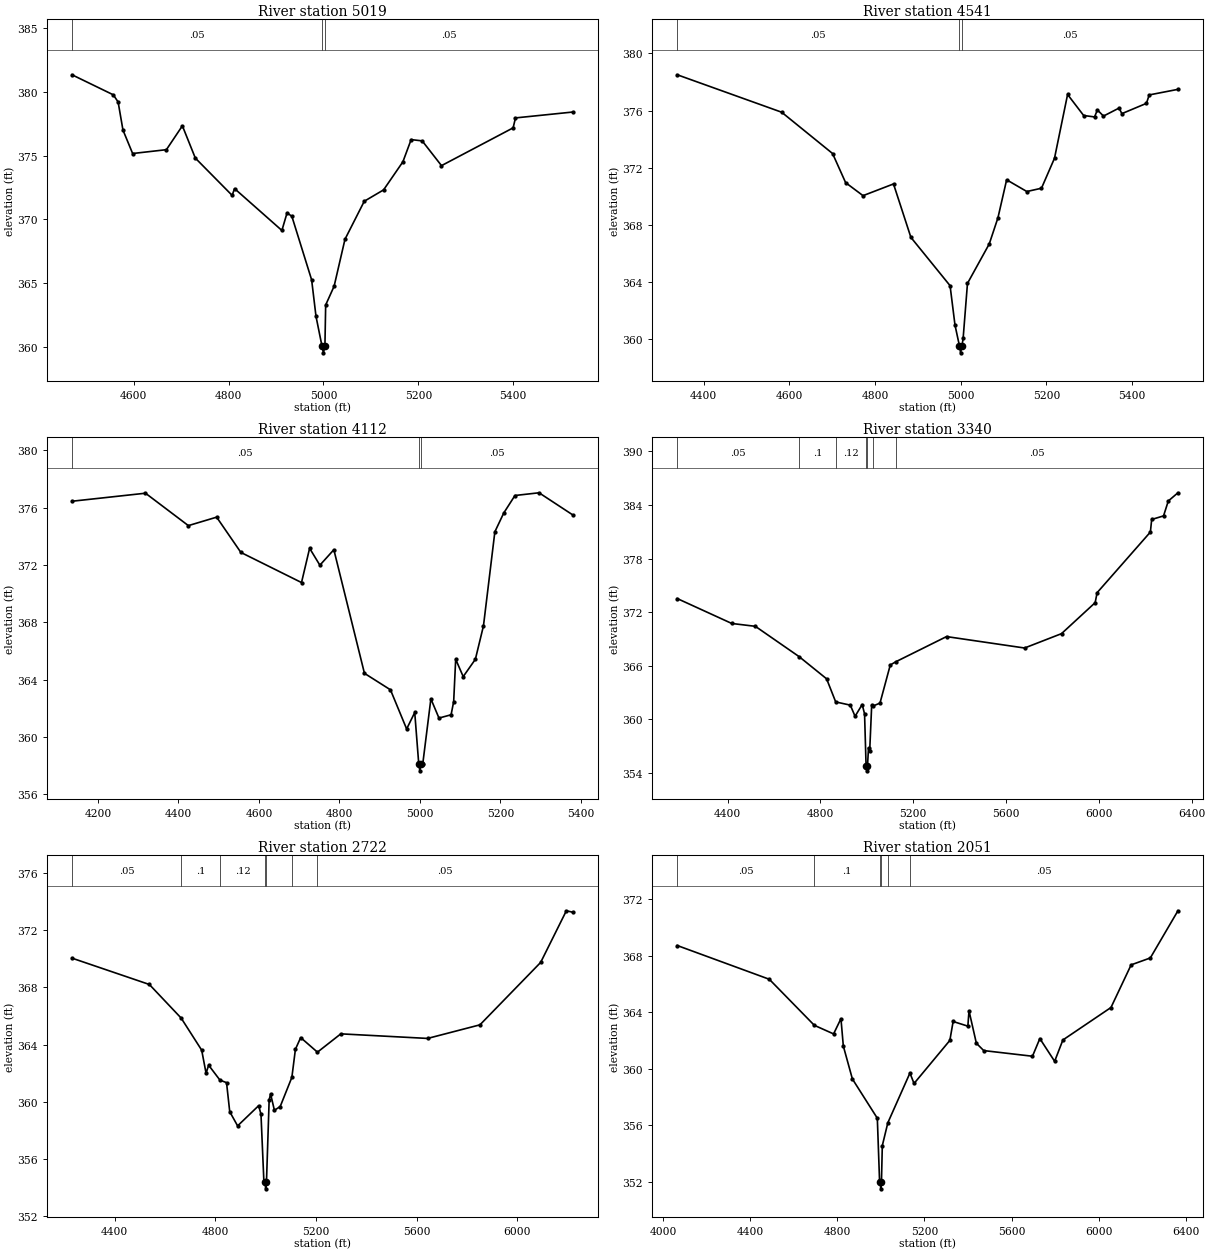
Type RM Length L Ch R = 1 ,5019    ,478,478,478
BEGIN DESCRIPTION:
UNT023 IN SUCR 5.1
END DESCRIPTION:
XS GIS Cut Line= 2
      2294453.26     13439649.15      2293415.89     13439844.47
#Sta/Elev= 30
  4469.8  381.33  4556.8  379.76    4567   379.2  4577.2     377  4597.6  375.16
  4668.8  375.46  4702.5  377.33  4729.8   374.8  4807.4  371.88  4812.5  372.41
  4912.3  369.13  4923.2  370.51  4933.3  370.24    4975  365.26  4984.2   362.4
    4997  360.04  4999.8  359.54    5003  360.04  5004.6  363.29  5022.4  364.76
  5045.3  368.44    5086  371.42  5126.7  372.31  5167.4  374.51  5184.8  376.25
  5208.1  376.15  5248.8  374.21  5399.8  377.17  5404.8  377.95  5525.4  378.41
#Mann= 3 ,-1 , 0
  4469.8     .05       0    4997     .03       0    5003     .05       0
Bank Sta=4997,5003
XS Rating Curve= 0 ,0
Exp/Cntr=0.3,0.1

Type RM Length L Ch R = 1 ,4541    ,429,429,429
BEGIN DESCRIPTION:
UNT023 IN SUCR 4.1
END DESCRIPTION:
XS GIS Cut Line= 4
       2294414.6     13439308.78      2294278.74     13439209.15
      2293508.93       13439345.      2293368.85      13439512.2
#Sta/Elev= 30
  4338.6  378.51  4582.2  375.89    4701     373  4731.5  370.96  4772.1  370.05
  4843.2  370.87  4883.8  367.13  4975.2  363.75  4986.7  360.99    4997  359.55
  4999.8  359.05    5003  359.55  5005.7  360.07  5015.8  363.91  5066.6  366.67
  5086.9   368.5  5107.2  371.16  5154.3  370.34  5188.5  370.57  5218.9  372.67
  5249.4  377.13  5286.9  375.66  5312.4  375.56  5318.9  376.05  5333.2  375.62
  5369.5  376.18  5376.1  375.79  5433.4  376.51  5439.9   377.1  5506.9  377.49
#Mann= 3 ,-1 , 0
  4338.6     .05       0    4997     .03       0    5003     .05       0
Bank Sta=4997,5003
XS Rating Curve= 0 ,0
Exp/Cntr=0.3,0.1

Type RM Length L Ch R = 1 ,4112    ,772,772,772
BEGIN DESCRIPTION:
UNT023 IN SUCR 3.1
END DESCRIPTION:
XS GIS Cut Line= 4
      2294464.42     13439028.03      2294237.99      13438833.3
      2293486.29     13438901.23      2293445.53      13439086.9
#Sta/Elev= 30
  4135.9  376.44  4318.4     377  4424.9  374.74  4495.1  375.33  4555.3  372.87
  4705.9  370.77    4726  373.16  4751.5  371.98  4786.2  373.06  4862.2  364.44
  4926.8  363.29    4967  360.56  4987.1  361.71    4997  358.14  4999.8  357.64
    5003  358.14  5007.1  358.14  5027.2  362.66  5047.3  361.32  5077.4  361.55
  5083.8  362.47  5088.8  365.42  5107.5  364.21  5137.7  365.42  5157.8  367.75
  5186.1  374.31  5208.2  375.62    5236  376.84  5295.8  377.03  5379.4  375.49
#Mann= 3 ,-1 , 0
  4135.9     .05       0    4997     .03       0    5003     .05       0
Bank Sta=4997,5003
XS Rating Curve= 0 ,0
Exp/Cntr=0.3,0.1

Type RM Length L Ch R = 1 ,3340    ,618,618,618
BEGIN DESCRIPTION:
Mapping XS 35e53971
END DESCRIPTION:
XS GIS Cut Line= 4
      2294183.26     13438528.37      2293987.94      13438241.9
      2292646.79     13437955.44      2292217.08     13438046.59
#Sta/Elev= 30
  4183.3  373.52  4418.1  370.73  4519.8  370.41  4708.6  367.01  4826.8  364.53
    4866  361.94    4929  361.58  4949.5  360.33  4980.2  361.65  4990.4   360.6
    4997  354.72  4999.8  354.22    5003  354.72  5007.4  356.82  5012.5  356.43
  5021.1  361.58  5025.9  361.47  5056.9  361.81  5101.2  366.08  5125.8  366.45
  5343.6  369.26  5679.9  367.98  5839.1  369.59    5984  373.06  5992.5  374.18
    6222  380.97  6227.6  382.38  6278.7  382.78  6299.2  384.45  6340.7  385.37
#Mann= 7 ,-1 , 0
  4183.3     .05       0  4708.6      .1       0    4866     .12       0
    4997     .07       0    5003     .12       0  5025.9      .1       0
  5125.8     .05       0
Bank Sta=4997,5003
XS Rating Curve= 0 ,0
Exp/Cntr=0.3,0.1

Type RM Length L Ch R = 1 ,2722    ,671,671,671
BEGIN DESCRIPTION:
UNT023 IN SUCR 2.1
END DESCRIPTION:
XS GIS Cut Line= 4
      2294167.81     13437974.32      2294055.57     13437679.16
      2292750.35     13437284.27      2292442.75     13437329.99
#Sta/Elev= 30
  4229.9  370.05  4537.4  368.21  4663.9  365.86  4745.4  363.62  4762.8  362.01
  4773.1  362.57  4817.9  361.53  4844.2  361.35  4856.9  359.32  4888.2  358.33
  4971.8  359.74  4981.1  359.15  4992.7  354.43    4997  354.43  4999.8  353.93
    5003  354.43  5013.6  360.14  5019.3  360.56  5034.5  359.42  5057.5  359.68
  5103.9  361.72    5118  363.68  5138.9   364.5  5205.6  363.48  5298.5  364.76
  5643.5  364.44  5851.6  365.39  6092.9  369.75  6195.1  373.36  6220.3  373.26
#Mann= 7 ,-1 , 0
  4229.9     .05       0  4663.9      .1       0  4817.9     .12       0
    4997     .07       0    5003     .12       0  5103.9      .1       0
  5205.6     .05       0
Bank Sta=4997,5003
XS Rating Curve= 0 ,0
Exp/Cntr=0.3,0.1

Type RM Length L Ch R = 1 ,2051    ,1216,1216,1216
BEGIN DESCRIPTION:
Mapping XS 947b85f7
END DESCRIPTION:
XS GIS Cut Line= 4
      2294271.72     13437753.98      2294084.67     13437076.43
      2293095.36     13436793.77      2292531.39     13436839.39
#Sta/Elev= 30
  4065.9  368.73  4488.3  366.34  4694.9  363.08  4783.3  362.47  4817.1  363.55
    4828  361.61  4869.6  359.28    4984   356.5  4994.4     352    4997     352
  4999.8   351.5    5003     352  5006.9  354.56  5032.3  356.18  5133.7   359.7
  5152.5  358.96  5316.8  362.01  5331.9  363.35  5399.5  363.02  5404.7  364.11
  5438.5  361.81  5472.3  361.29    5696  360.89  5729.8  362.14  5797.7  360.53
  5835.5  362.04  6056.2  364.34  6148.7  367.36  6236.8  367.85  6363.5  371.19
#Mann= 6 ,-1 , 0
  4065.9     .05       0  4694.9      .1       0    4997     .07       0
    5003      .1       0  5032.3     .12       0  5133.7     .05       0
Bank Sta=4997,5003
XS Rating Curve= 0 ,0
Exp/Cntr=0.3,0.1

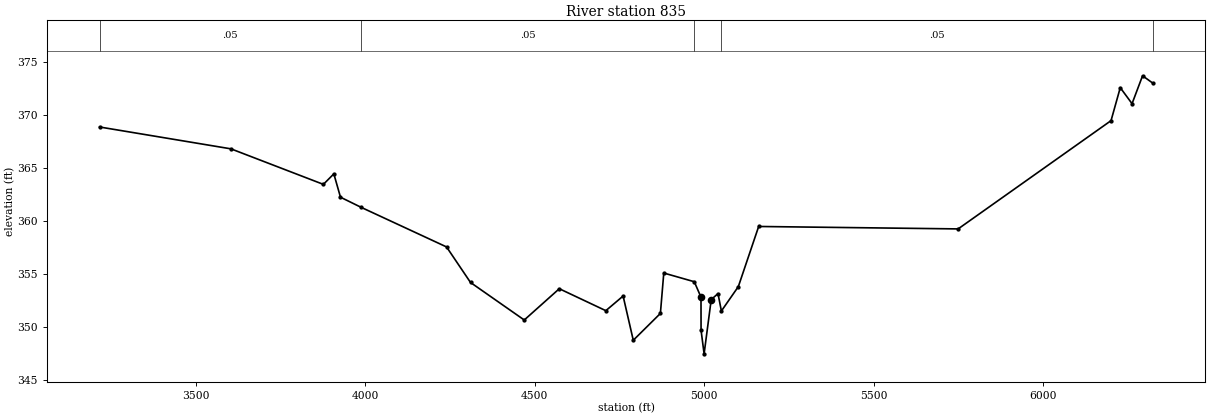
Type RM Length L Ch R = 1 ,835     ,0,0,0
BEGIN DESCRIPTION:
UNT023 IN SUCR 1.0
END DESCRIPTION:
XS GIS Cut Line= 5
      2294338.23     13437770.61      2294163.64     13436527.74
      2294051.41     13436286.65      2293215.91     13436278.34
      2292488.52     13436465.38
#Sta/Elev= 30
  3216.1  368.86  3603.6   366.8  3876.3  363.45  3907.2  364.44  3926.8  362.24
  3987.4  361.29  4239.8  357.55  4310.5   354.2  4469.1  350.66  4572.5  353.61
  4709.8  351.54  4760.8  352.92  4790.8  348.75  4870.8  351.28  4880.8  355.09
  4970.8  354.27 4990.62  352.81  4990.8   349.7  4999.8  347.47  5020.8  352.59
  5040.8  353.15  5050.8  351.51  5100.8  353.81  5160.8  359.48  5749.4  359.25
  6200.6  369.46  6227.8  372.57  6262.6  371.06  6293.6  373.69  6323.7     373
#Mann= 5 ,-1 , 0
  3216.1     .05       0  3987.4     .05       0  4970.8     .03       0
  5050.8     .05       0  6323.7     .05       0
Bank Sta=4990.62,5020.8
XS Rating Curve= 0 ,0
Exp/Cntr=0.3,0.1

Chan Stop Cuts=-1
Use User Specified Reach Order=0
Composite Channel Slope=5