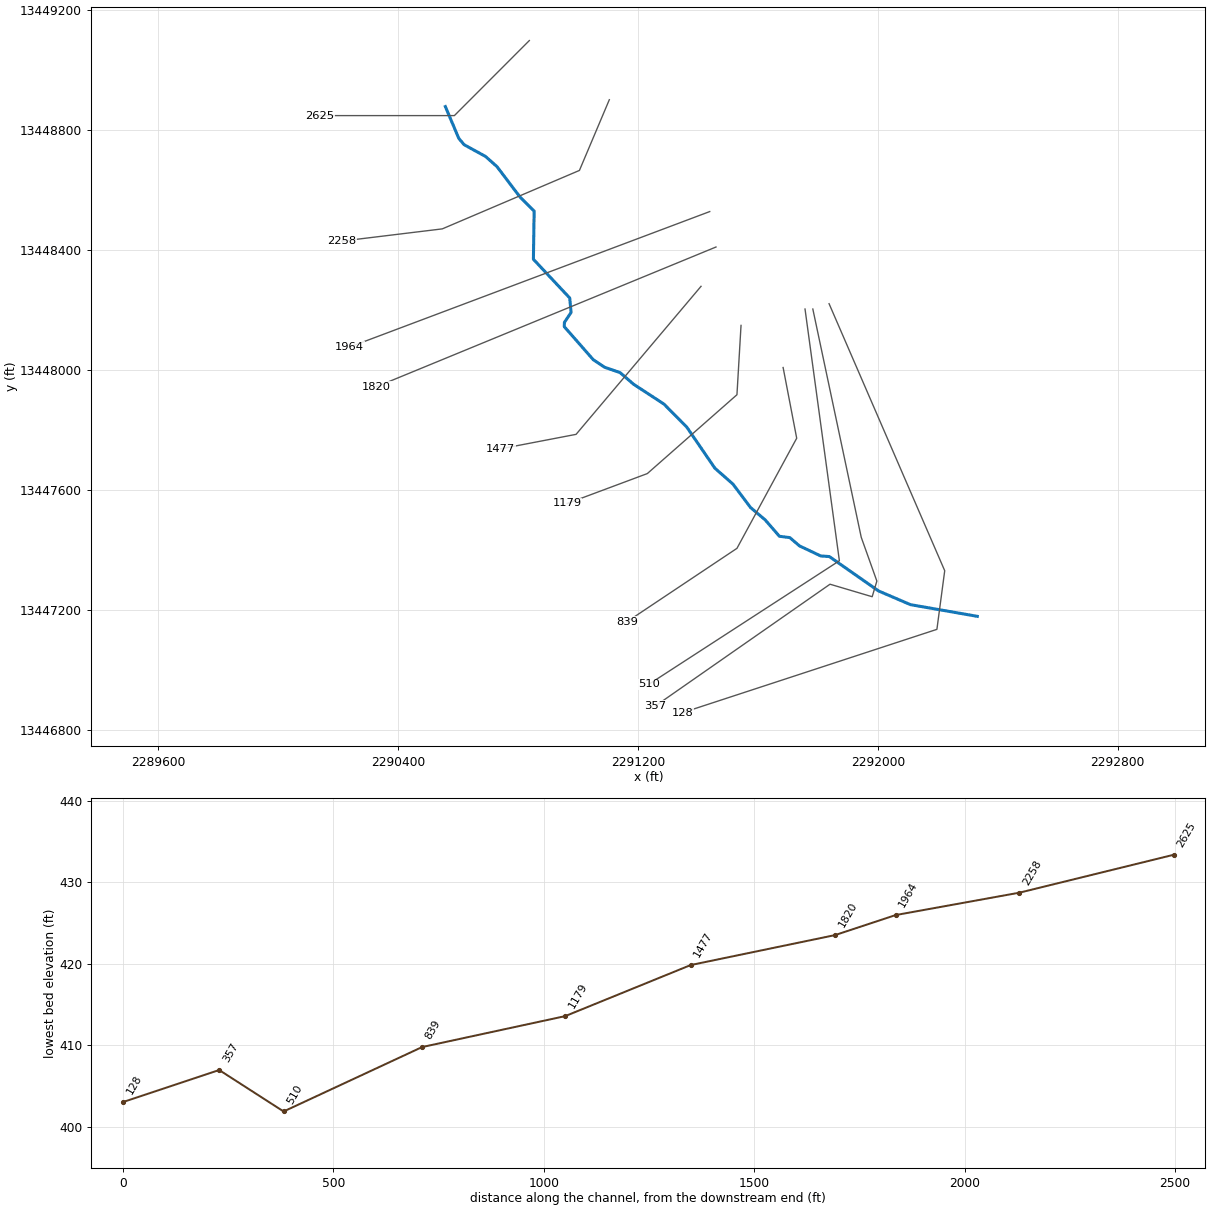
--- UNT024 IN SUCR.prj (project) ---

Proj Title=UNT024 IN SUCR Base Level Engineering
Current Plan=p01
Default Exp/Contr=0.3,0.1
English Units
Geom File=g01
Flow File=f01
Plan File=p01
BEGIN DESCRIPTION:
UNT024 IN SUCR
END DESCRIPTION:

--- UNT024 IN SUCR.p01 (plan) ---

Plan Title=Multiple Run
Short Identifier=Multiple
Geom File=g01
Flow File=f01
Subcritical Flow
K Sum by GR= 0
Std Step Tol= 0.01
Critical Tol= 0.01
Num of Std Step Trials= 20
Max Error Tol= 0.3
Flow Tol Ratio= 0.001
Split Flow NTrial= 30
Split Flow Tol= 0.02
Split Flow Ratio= 0.02
Log Output Level= 0
Friction Slope Method= 1
Unsteady Friction Slope Method= 2
Unsteady Bridges Friction Slope Method= 1
Parabolic Critical Depth
Global Vel Dist=  1 , 1 , 1
Global Log Level= 0
CheckData=True
Encroach Param= -1, 0, 0, 0
BEGIN DESCRIPTION:
Multiple Run
END DESCRIPTION:

--- UNT024 IN SUCR.f01 (steady flow) ---

Flow Title=Multiple
Number of Profiles=7
Profile Names=10-year,25-year,50-year,1pct_min,100-year,1pct_plu,500-year
River Rch & RM= UNT024 IN SUCR,Reach-1,2625
     211     278     331     289     390     528     545
River Rch & RM= UNT024 IN SUCR,Reach-1,1820
     359     488     591     524     709     958    1021
Boundary for River Rch & Prof#=UNT024 IN SUCR,Reach-1,1
Up Type=0
Dn Type=3
Dn Slope=0.005
Boundary for River Rch & Prof#=UNT024 IN SUCR,Reach-1,2
Up Type=0
Dn Type=3
Dn Slope=0.005
Boundary for River Rch & Prof#=UNT024 IN SUCR,Reach-1,3
Up Type=0
Dn Type=3
Dn Slope=0.005
Boundary for River Rch & Prof#=UNT024 IN SUCR,Reach-1,4
Up Type=0
Dn Type=3
Dn Slope=0.005
Boundary for River Rch & Prof#=UNT024 IN SUCR,Reach-1,5
Up Type=0
Dn Type=3
Dn Slope=0.005
Boundary for River Rch & Prof#=UNT024 IN SUCR,Reach-1,6
Up Type=0
Dn Type=3
Dn Slope=0.005
Boundary for River Rch & Prof#=UNT024 IN SUCR,Reach-1,7
Up Type=0
Dn Type=3
Dn Slope=0.005

--- UNT024 IN SUCR.g01 (geometry) ---

Geom Title=Existing Conditions

River Reach=UNT024 IN SUCR,Reach-1
Reach XY= 30
      2290557.59     13448876.99      2290602.13     13448771.56
      2290619.84     13448750.15      2290691.53     13448710.81
      2290729.51     13448677.18      2290807.90     13448574.05
      2290853.73     13448528.91      2290851.26     13448368.32
      2290972.35     13448239.34      2290976.91     13448191.26
      2290954.73     13448158.16      2290954.11     13448143.92
      2291051.06     13448033.55      2291088.44     13448008.71
      2291139.98     13447990.94      2291185.20     13447952.14
      2291286.71     13447885.86      2291362.66     13447809.28
      2291456.45     13447672.35      2291516.66     13447619.51
      2291575.64     13447541.09      2291624.29     13447500.04
      2291671.62     13447445.58      2291706.39     13447441.09
      2291738.48     13447413.55      2291809.38     13447380.08
      2291838.21     13447377.95      2292002.18     13447263.43
      2292108.52     13447217.85      2292331.45     13447178.90

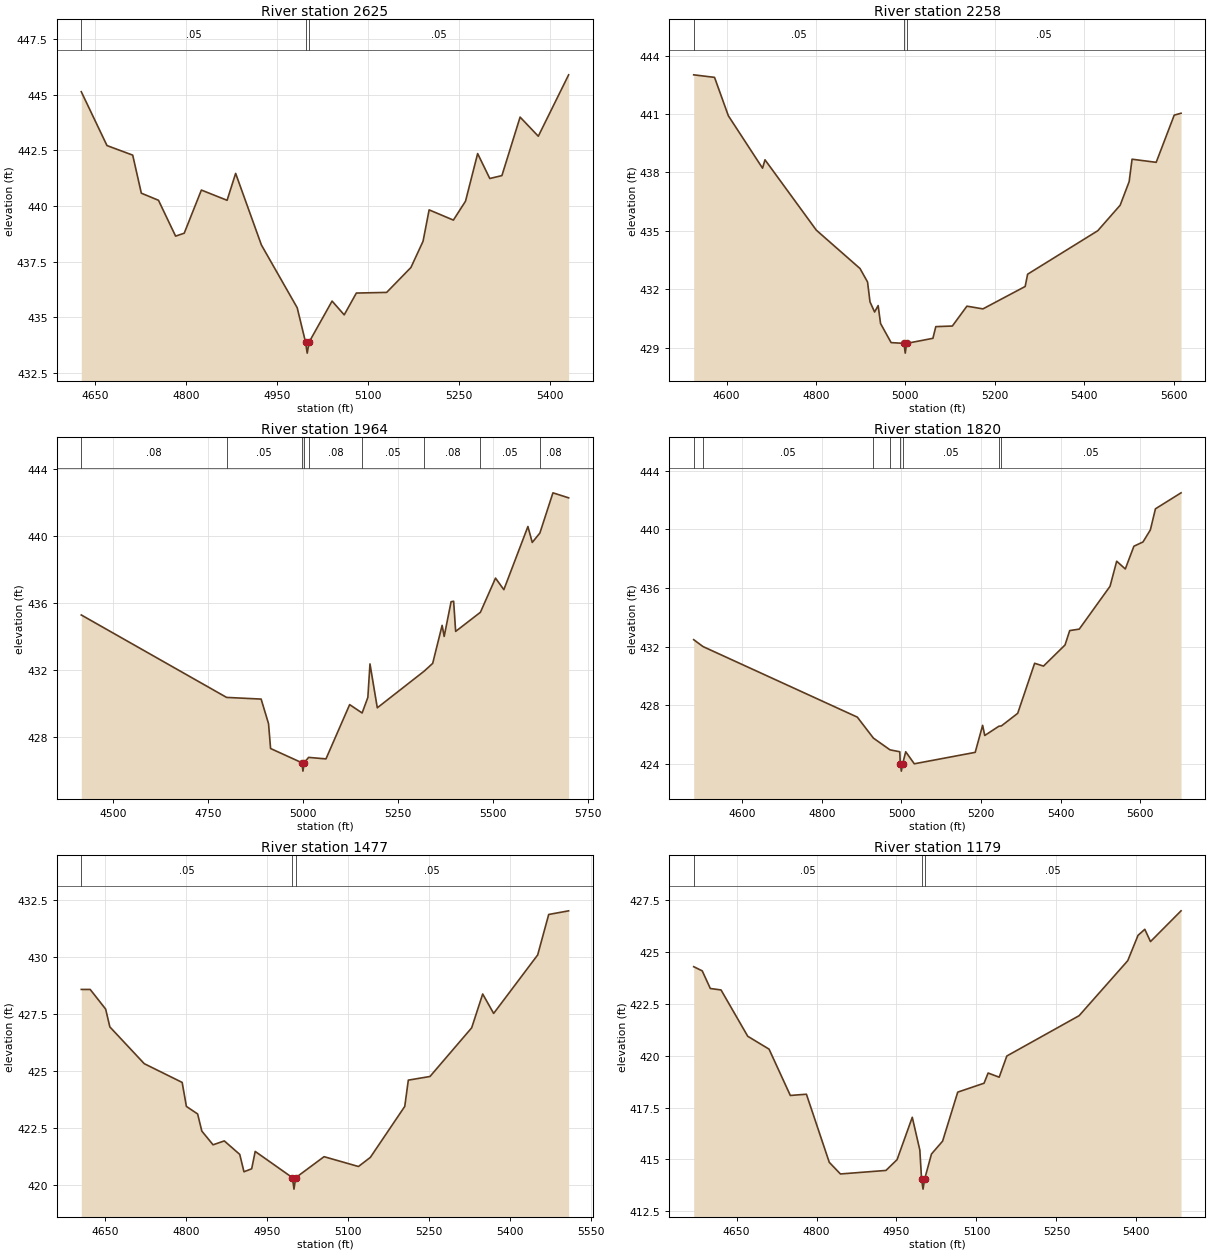
Type RM Length L Ch R = 1,2625,367,367,367
BEGIN DESCRIPTION:
UNT024 IN SUCR 31.0
END DESCRIPTION:
XS GIS Cut Line= 3
      2290837.70     13449096.84      2290587.72     13448846.85
      2290137.75     13448846.85
#Sta/Elev= 30
  4627.3  445.14  4669.7  442.72  4712.1  442.29  4726.3  440.58  4754.6  440.26
  4782.8  438.65  4797.0  438.78  4825.3  440.72  4867.7  440.26  4881.8  441.47
  4924.3  438.25  4983.3  435.43  4997.0  433.89  4999.8  433.39  5003.0  433.89
  5040.8  435.73  5060.8  435.11  5080.8  436.09  5130.8  436.12  5170.8  437.24
  5190.8  438.42  5200.8  439.83  5240.8  439.37  5260.8  440.22  5280.8  442.36
  5300.8  441.24  5320.8  441.37  5350.8  444.00  5380.8  443.14  5430.8  445.90
#Mann=3,-1,0
  4627.3    0.05       0  4997.0    0.03       0  5003.0    0.05       0
Bank Sta=4997,5003
Exp/Cntr=0.3,0.1

Type RM Length L Ch R = 1,2258,294,294,294
BEGIN DESCRIPTION:
Mapping XS fd523108
END DESCRIPTION:
XS GIS Cut Line= 4
      2291104.42     13448899.75      2291004.78     13448664.25
      2290547.42     13448469.53      2290212.48     13448428.80
#Sta/Elev= 30
  4526.6  443.01  4573.2  442.88  4604.1  440.91  4680.6  438.22  4686.1  438.65
  4800.9  435.04  4898.7  433.07  4915.5  432.38  4921.0  431.36  4931.3  430.84
  4939.2  431.17  4944.6  430.25  4968.2  429.27  4997.0  429.23  4999.8  428.73
  5003.0  429.23  5061.7  429.49  5068.2  430.09  5105.2  430.12  5137.8  431.14
  5173.6  431.00  5268.1  432.15  5273.6  432.78  5430.5  435.01  5480.6  436.32
  5500.7  437.53  5507.2  438.68  5561.2  438.52  5601.5  440.94  5616.8  441.04
#Mann=3,-1,0
  4526.6    0.05       0  4997.0    0.03       0  5003.0    0.05       0
Bank Sta=4997,5003
Exp/Cntr=0.3,0.1

Type RM Length L Ch R = 1,1964,144,144,144
BEGIN DESCRIPTION:
UNT024 IN SUCR 30.0
END DESCRIPTION:
XS GIS Cut Line= 2
      2291439.30     13448527.18      2290238.00     13448075.82
#Sta/Elev= 30
  4416.1  435.30  4798.7  430.38  4889.7  430.28  4909.2  428.81  4914.6  427.33
  4997.0  426.48  4999.8  425.98  5003.0  426.48  5014.7  426.80  5060.4  426.71
  5122.8  429.95  5155.6  429.45  5170.7  430.38  5176.3  432.38  5195.6  429.76
  5319.2  431.95  5341.4  432.41  5366.3  434.68  5371.7  434.02  5389.9  436.09
  5396.6  436.12  5401.9  434.32  5467.1  435.46  5506.9  437.50  5528.8  436.81
  5592.2  440.58  5603.6  439.63  5623.7  440.19  5658.1  442.59  5699.4  442.29
#Mann=9,-1,0
  4416.1    0.08       0  4798.7    0.05       0  4997.0    0.03       0
  5003.0    0.05       0  5014.7    0.08       0  5155.6    0.05       0
  5319.2    0.08       0  5467.1    0.05       0  5623.7    0.08       0
Bank Sta=4997,5003
Exp/Cntr=0.3,0.1

Type RM Length L Ch R = 1,1820,343,343,343
BEGIN DESCRIPTION:
UNT024 IN SUCR 29.0
END DESCRIPTION:
XS GIS Cut Line= 2
      2291460.16     13448409.13      2290328.25     13447943.87
#Sta/Elev= 30
  4478.3  432.48  4501.7  432.01  4889.2  427.20  4929.6  425.77  4971.3  424.97
  4995.8  424.84  4997.0  424.02  4999.8  423.52  5003.0  424.02  5010.7  424.84
  5032.3  424.02  5185.2  424.80  5203.8  426.64  5209.2  425.95  5244.6  426.58
  5250.9  426.60  5291.9  427.46  5334.4  430.87  5356.7  430.68  5410.8  432.12
  5422.5  433.10  5446.5  433.20  5523.8  436.12  5540.5  437.83  5562.1  437.30
  5583.7  438.85  5606.5  439.14  5625.0  439.96  5637.8  441.40  5702.1  442.49
#Mann=8,-1,0
  4478.3    0.08       0  4501.7    0.05       0  4929.6    0.08       0
  4971.3    0.05       0  4997.0    0.03       0  5003.0    0.05       0
  5244.6    0.08       0  5250.9    0.05       0
Bank Sta=4997,5003
Exp/Cntr=0.3,0.1

Type RM Length L Ch R = 1,1477,298,298,298
BEGIN DESCRIPTION:
Mapping XS 46352f37
END DESCRIPTION:
XS GIS Cut Line= 3
      2291410.27     13448278.16      2290993.59     13447785.09
      2290741.44     13447736.74
#Sta/Elev= 30
  4606.0  428.58  4622.5  428.58  4651.1  427.72  4658.9  426.94  4722.6  425.33
  4792.8  424.51  4800.6  423.46  4821.4  423.13  4829.2  422.38  4850.0  421.78
  4870.8  421.95  4899.4  421.36  4907.2  420.60  4921.5  420.73  4928.0  421.49
  4997.0  420.34  4999.8  419.84  5003.0  420.34  5055.5  421.26  5119.2  420.83
  5141.2  421.23  5204.9  423.46  5211.5  424.61  5251.6  424.77  5328.8  426.90
  5349.2  428.38  5369.5  427.53  5451.0  430.09  5471.4  431.86  5508.3  432.02
#Mann=3,-1,0
  4606.0    0.05       0  4997.0    0.03       0  5003.0    0.05       0
Bank Sta=4997,5003
Exp/Cntr=0.3,0.1

Type RM Length L Ch R = 1,1179,340,340,340
BEGIN DESCRIPTION:
UNT024 IN SUCR 28.0
END DESCRIPTION:
XS GIS Cut Line= 4
      2291543.65     13448148.04      2291530.06     13447917.08
      2291231.20     13447654.44      2290964.00     13447554.80
#Sta/Elev= 30
  4569.5  424.28  4585.5  424.08  4600.7  423.23  4620.8  423.16  4670.9  420.93
  4710.9  420.31  4750.8  418.08  4781.0  418.14  4823.9  414.86  4844.8  414.30
  4930.2  414.47  4951.1  414.99  4979.6  417.03  4993.8  415.45  4997.0  414.07
  4999.8  413.57  5003.0  414.07  5015.6  415.26  5036.5  415.88  5064.9  418.24
  5114.3  418.67  5121.9  419.16  5142.7  418.96  5157.0  419.98  5292.6  421.92
  5383.9  424.57  5403.2  425.79  5415.9  426.08  5426.6  425.49  5483.9  426.97
#Mann=3,-1,0
  4569.5    0.05       0  4997.0    0.03       0  5003.0    0.05       0
Bank Sta=4997,5003
Exp/Cntr=0.3,0.1

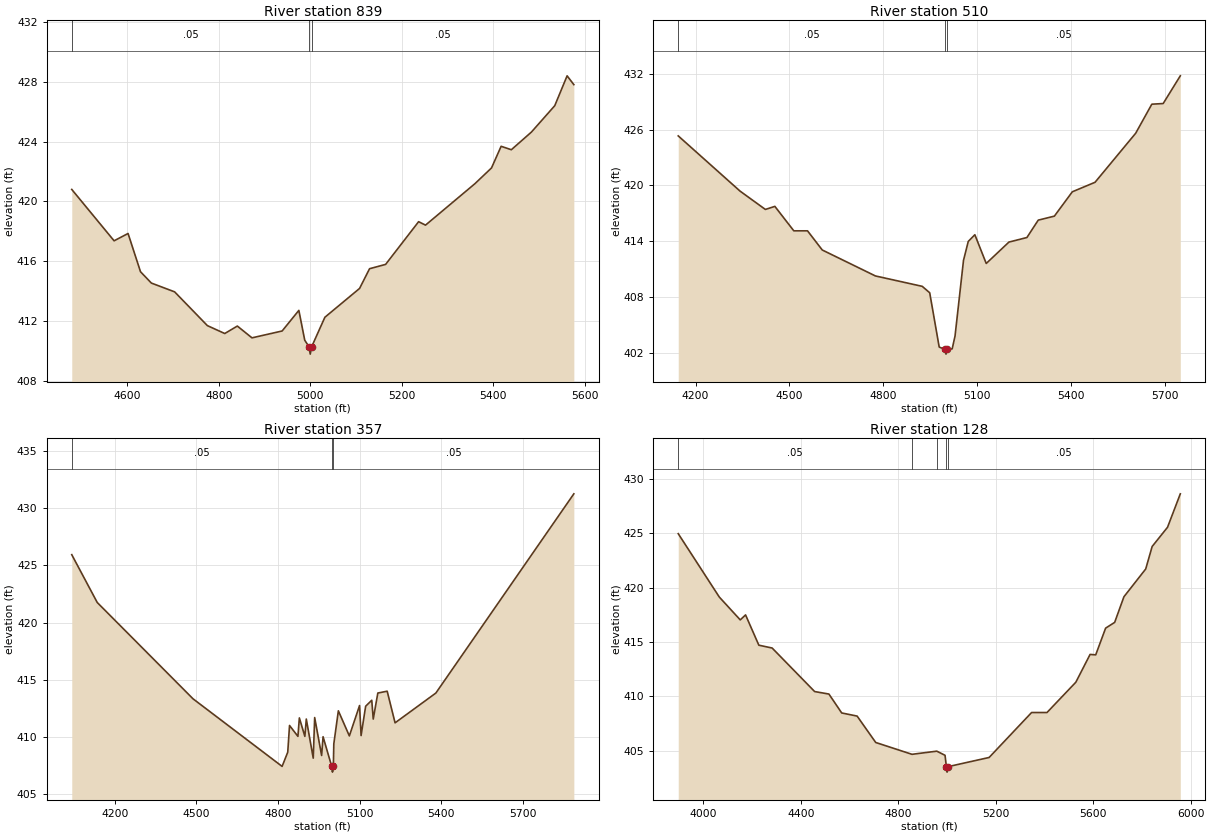
Type RM Length L Ch R = 1,839,329,329,329
BEGIN DESCRIPTION:
UNT024 IN SUCR 27.0
END DESCRIPTION:
XS GIS Cut Line= 4
      2291684.02     13448007.66      2291729.31     13447772.17
      2291530.06     13447405.38      2291164.05     13447161.38
#Sta/Elev= 30
  4478.7  420.80  4571.2  417.36  4601.7  417.85  4628.9  415.29  4652.6  414.53
  4703.5  413.94  4775.0  411.68  4813.0  411.15  4840.5  411.65  4872.5  410.86
  4938.4  411.32  4974.9  412.70  4987.8  410.70  4997.0  410.27  4999.8  409.77
  5003.0  410.27  5031.8  412.24  5107.6  414.17  5129.4  415.49  5164.5  415.78
  5236.6  418.64  5251.7  418.41  5359.8  421.19  5395.9  422.24  5416.9  423.69
  5439.2  423.46  5483.0  424.64  5534.1  426.41  5561.1  428.41  5575.8  427.82
#Mann=3,-1,0
  4478.7    0.05       0  4997.0    0.03       0  5003.0    0.05       0
Bank Sta=4997,5003
Exp/Cntr=0.3,0.1

Type RM Length L Ch R = 1,510,153,153,153
BEGIN DESCRIPTION:
Mapping XS 4251830d
END DESCRIPTION:
XS GIS Cut Line= 3
      2291757.05     13448202.57      2291871.64     13447364.00
      2291236.19     13446952.52
#Sta/Elev= 30
  4144.7  425.33  4342.2  419.39  4423.0  417.42  4453.3  417.75  4513.8  415.12
  4557.6  415.12  4604.6  413.06  4774.3  410.27  4923.9  409.15  4947.8  408.46
  4978.1  402.62  4997.0  402.36  4999.8  401.86  5003.0  402.36  5019.6  402.43
  5028.7  403.81  5055.7  411.94  5070.9  413.98  5092.0  414.70  5128.3  411.61
  5200.8  413.91  5258.2  414.40  5294.4  416.27  5345.9  416.70  5403.3  419.32
  5475.8  420.34  5605.7  425.62  5657.1  428.74  5693.4  428.81  5748.1  431.79
#Mann=3,-1,0
  4144.7    0.05       0  4997.0    0.03       0  5003.0    0.05       0
Bank Sta=4997,5003
Exp/Cntr=0.3,0.1

Type RM Length L Ch R = 1,357,229,229,229
BEGIN DESCRIPTION:
Mapping XS 08beda07
END DESCRIPTION:
XS GIS Cut Line= 6
      2291783.10     13448202.51      2291944.55     13447442.12
      2291996.64     13447296.29      2291981.01     13447244.21
      2291840.39     13447285.87      2291258.66     13446880.74
#Sta/Elev= 30
  4041.8  425.92  4135.4  421.75  4487.2  413.35  4814.7  407.45  4835.4  408.69
  4842.0  411.02  4872.8  410.07  4878.1  411.68  4898.3  410.07  4903.6  411.58
  4929.1  408.17  4934.4  411.71  4959.9  408.40  4965.2  410.04  4997.0  407.45
  4999.8  406.95  5003.0  407.45  5004.7  409.42  5021.4  412.30  5061.8  410.11
  5099.3  412.76  5104.9  410.14  5121.7  412.70  5144.1  413.22  5149.6  411.58
  5166.4  413.85  5200.8  414.01  5229.8  411.25  5379.7  413.85  5886.7  431.23
#Mann=3,-1,0
  4041.8    0.05       0  4997.0    0.03       0  5003.0    0.05       0
Bank Sta=4997,5003
Exp/Cntr=0.3,0.1

Type RM Length L Ch R = 1,128,0,0,0
BEGIN DESCRIPTION:
UNT024 IN SUCR 1.0
END DESCRIPTION:
XS GIS Cut Line= 4
      2291837.29     13448220.23      2292222.92     13447330.83
      2292196.87     13447135.52      2291347.91     13446857.74
#Sta/Elev= 30
  3896.9  424.97  4065.5  419.13  4151.3  417.03  4173.1  417.49  4227.6  414.70
  4282.1  414.44  4456.5  410.43  4515.1  410.20  4567.5  408.46  4630.8  408.17
  4707.1  405.74  4855.9  404.65  4957.6  404.94  4991.4  404.56  4997.0  403.51
  4999.8  403.01  5003.0  403.51  5172.3  404.36  5346.5  408.50  5409.7  408.50
  5528.0  411.29  5586.5  413.85  5609.6  413.81  5650.2  416.27  5687.3  416.80
  5725.3  419.16  5814.7  421.72  5841.1  423.79  5904.2  425.56  5956.6  428.64
#Mann=5,-1,0
  3896.9    0.05       0  4855.9     0.1       0  4957.6    0.05       0
  4997.0    0.03       0  5003.0    0.05       0
Bank Sta=4997,5003
Exp/Cntr=0.3,0.1

Chan Stop Cuts=-1