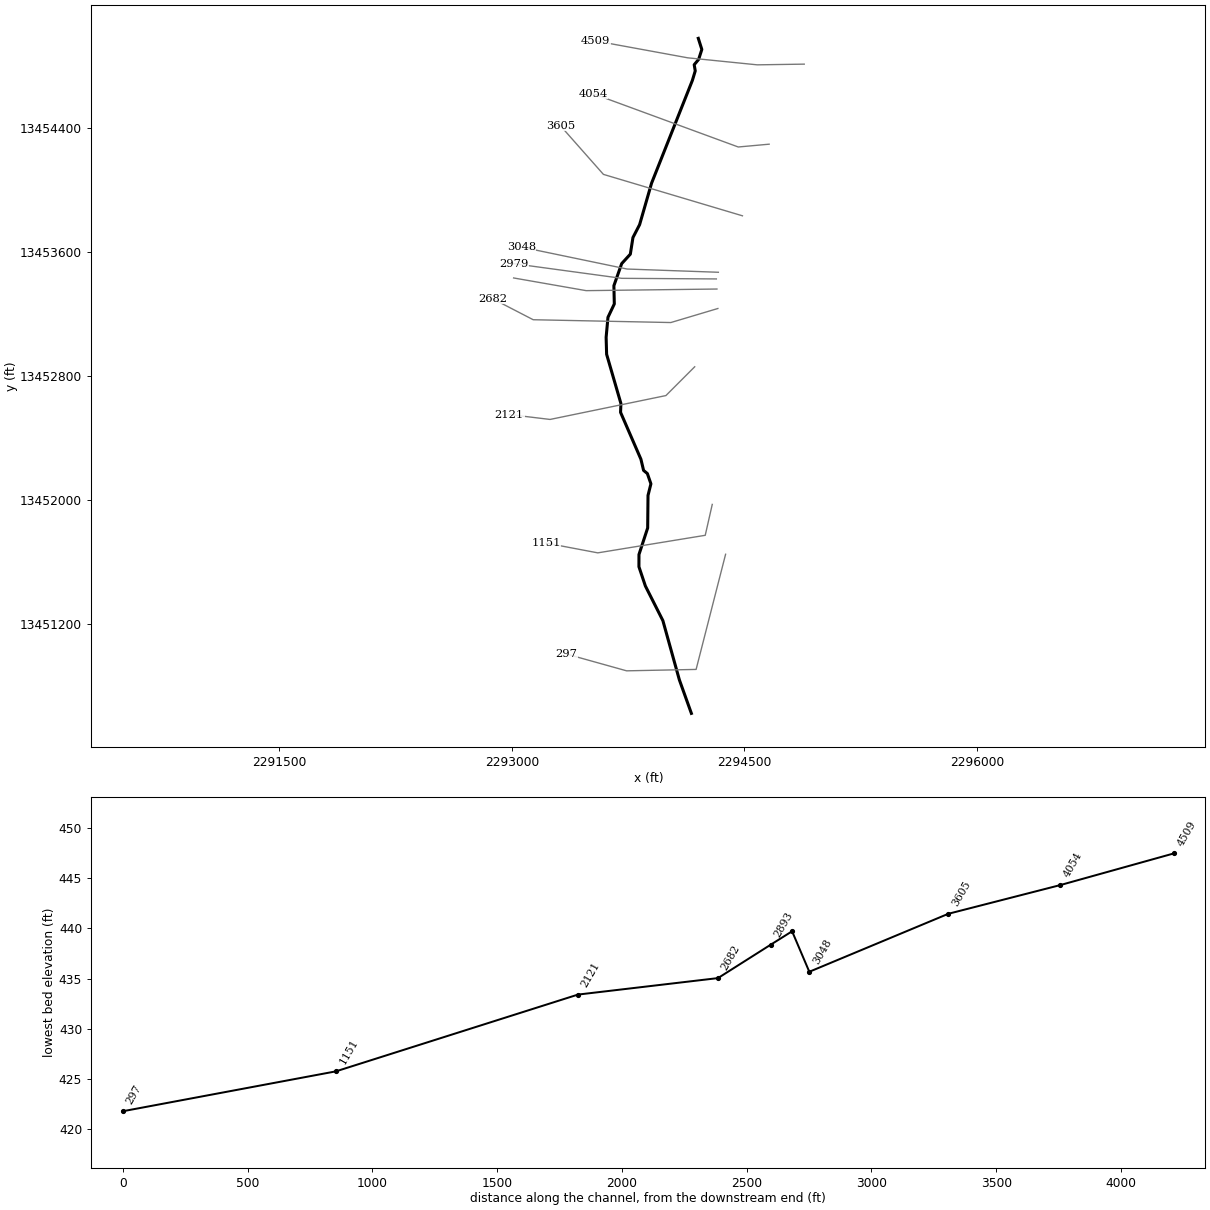
--- UNT025 IN SUCR.prj (project) ---

Proj Title=UNT025 IN SUCR Base Level Engineering
Current Plan=p01
Default Exp/Contr=0.3,0.1
English Units
Geom File=g01
Flow File=f01
Plan File=p01
BEGIN DESCRIPTION:
UNT025 IN SUCR
END DESCRIPTION:

--- UNT025 IN SUCR.p01 (plan) ---

Plan Title=Multiple Run
Short Identifier=Multiple
Geom File=g01
Flow File=f01
Subcritical Flow
K Sum by GR= 0
Std Step Tol= 0.01
Critical Tol= 0.01
Num of Std Step Trials= 20
Max Error Tol= 0.3
Flow Tol Ratio= 0.001
Split Flow NTrial= 30
Split Flow Tol= 0.02
Split Flow Ratio= 0.02
Log Output Level= 0
Friction Slope Method= 1
Unsteady Friction Slope Method= 2
Unsteady Bridges Friction Slope Method= 1
Parabolic Critical Depth
Global Vel Dist=  1 , 1 , 1
Global Log Level= 0
CheckData=True
Encroach Param= -1, 0, 0, 0
BEGIN DESCRIPTION:
Multiple Run
END DESCRIPTION:

--- UNT025 IN SUCR.f01 (steady flow) ---

Flow Title=Multiple
Number of Profiles=7
Profile Names=10-year,25-year,50-year,1pct_min,100-year,1pct_plu,500-year
River Rch & RM= UNT025 IN SUCR,Reach-1,4509
     626     887    1107    1009    1365    1846    2082
River Rch & RM= UNT025 IN SUCR,Reach-1,2682
     684     973    1217    1112    1503    2033    2302
Boundary for River Rch & Prof#=UNT025 IN SUCR,Reach-1,1
Up Type=0
Dn Type=3
Dn Slope=0.005
Boundary for River Rch & Prof#=UNT025 IN SUCR,Reach-1,2
Up Type=0
Dn Type=3
Dn Slope=0.005
Boundary for River Rch & Prof#=UNT025 IN SUCR,Reach-1,3
Up Type=0
Dn Type=3
Dn Slope=0.005
Boundary for River Rch & Prof#=UNT025 IN SUCR,Reach-1,4
Up Type=0
Dn Type=3
Dn Slope=0.005
Boundary for River Rch & Prof#=UNT025 IN SUCR,Reach-1,5
Up Type=0
Dn Type=3
Dn Slope=0.005
Boundary for River Rch & Prof#=UNT025 IN SUCR,Reach-1,6
Up Type=0
Dn Type=3
Dn Slope=0.005
Boundary for River Rch & Prof#=UNT025 IN SUCR,Reach-1,7
Up Type=0
Dn Type=3
Dn Slope=0.005

--- UNT025 IN SUCR.g01 (geometry) ---

Geom Title=Existing Conditions

River Reach=UNT025 IN SUCR,Reach-1
Reach XY= 30
      2294202.35     13454980.06      2294225.06     13454908.24
      2294204.58     13454844.42      2294175.92     13454809.93
      2294182.63     13454770.00      2294164.05     13454708.52
      2293900.81     13454045.57      2293823.82     13453778.47
      2293780.89     13453695.54      2293764.06     13453588.37
      2293708.25     13453527.20      2293657.98     13453384.90
      2293660.69     13453267.20      2293619.76     13453181.02
      2293607.90     13453051.74      2293611.09     13452942.55
      2293703.23     13452625.36      2293700.99     13452568.16
      2293832.36     13452265.66      2293849.43     13452193.64
      2293873.81     13452173.48      2293896.72     13452107.17
      2293878.06     13452032.42      2293875.83     13451822.71
      2293819.69     13451651.23      2293819.47     13451572.39
      2293861.06     13451448.24      2293973.86     13451225.17
      2294080.25     13450842.90      2294157.72     13450626.85

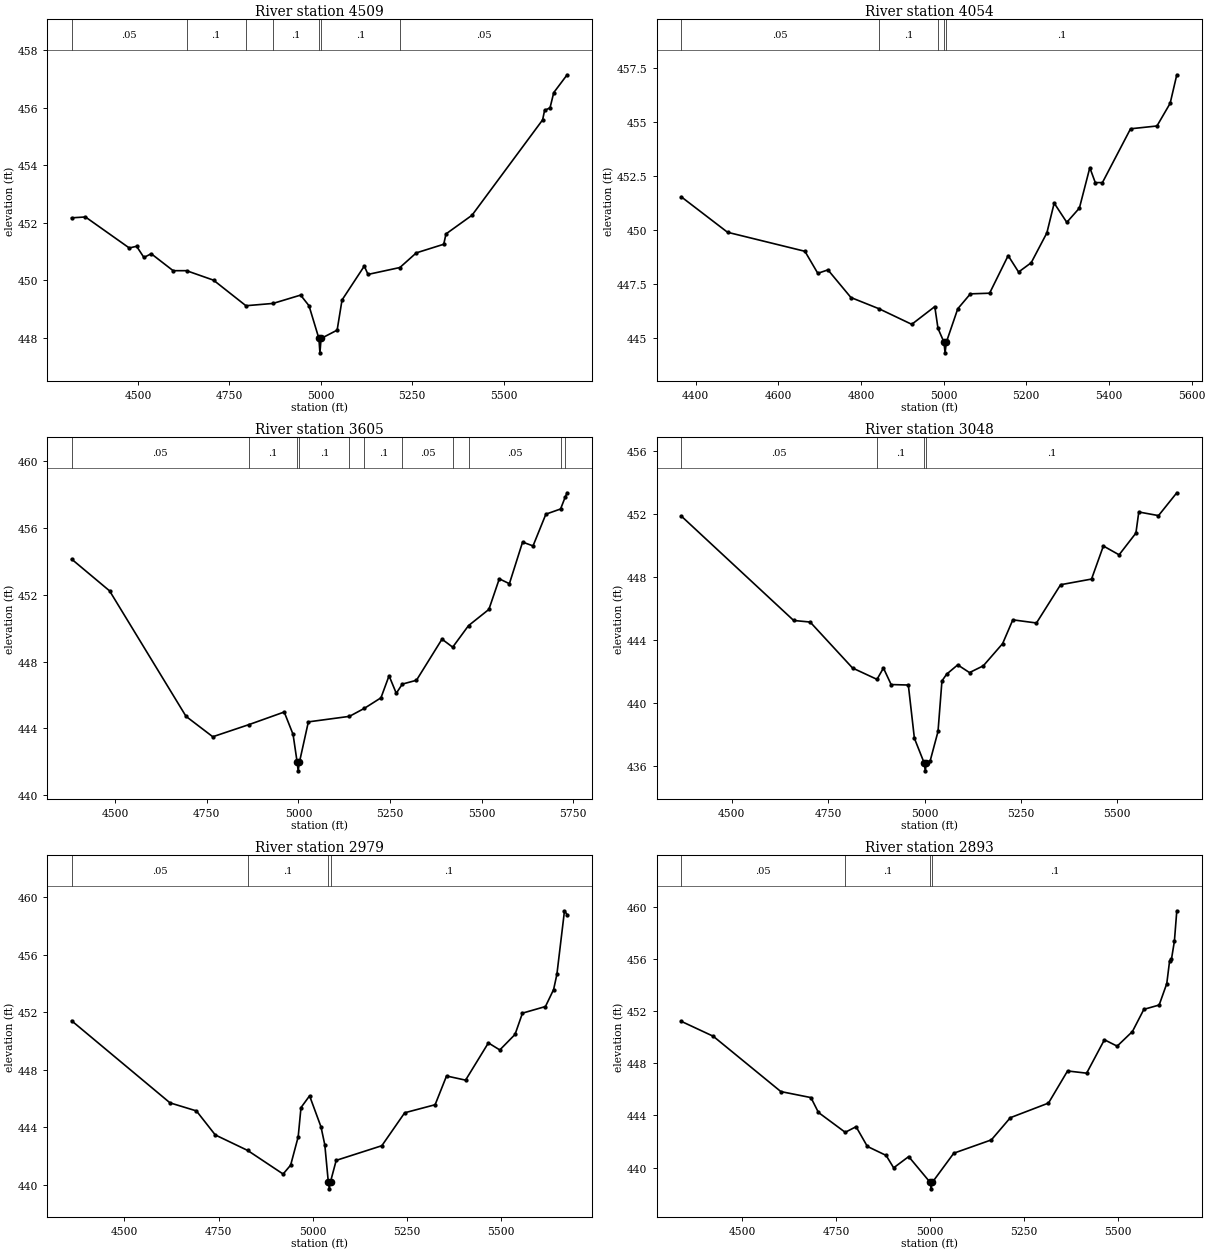
Type RM Length L Ch R = 1,4509,455,455,455
BEGIN DESCRIPTION:
UNT025 IN SUCR 7.0
END DESCRIPTION:
XS GIS Cut Line= 4
      2294885.52     13454813.69      2294582.14     13454809.16
      2294133.84     13454854.44      2293541.69     13454962.93
#Sta/Elev= 30
  4318.0  452.17  4355.8  452.20  4475.8  451.12  4495.8  451.18  4515.8  450.79
  4535.8  450.92  4595.8  450.33  4632.4  450.33  4706.3  450.00  4795.0  449.11
  4869.1  449.19  4944.6  449.48  4967.6  449.11  4994.7  447.97  4997.5  447.47
  5000.7  447.97  5044.6  448.26  5058.0  449.31  5118.9  450.49  5129.1  450.20
  5216.3  450.44  5261.2  450.95  5336.3  451.25  5342.5  451.61  5413.7  452.26
  5606.9  455.58  5612.3  455.91  5627.2  456.00  5637.4  456.53  5674.0  457.15
#Mann=7,-1,0
  4318.0    0.05       0  4632.4     0.1       0  4795.0    0.05       0
  4869.1     0.1       0  4994.7    0.07       0  5000.7     0.1       0
  5216.3    0.05       0
Bank Sta=4994.7,5000.7
Exp/Cntr=0.3,0.1

Type RM Length L Ch R = 1,4054,449,449,449
BEGIN DESCRIPTION:
UNT025 IN SUCR 6.0
END DESCRIPTION:
XS GIS Cut Line= 3
      2294659.16     13454297.46      2294459.88     13454279.35
      2293522.65     13454623.45
#Sta/Elev= 30
  4365.6  451.54  4477.5  449.90  4664.6  449.02  4695.8  448.00  4720.3  448.16
  4775.9  446.88  4843.9  446.36  4923.0  445.64  4978.7  446.46  4986.5  445.45
  5000.8  444.82  5003.6  444.32  5006.8  444.82  5034.3  446.36  5064.8  447.05
  5111.3  447.08  5156.2  448.82  5181.4  448.06  5211.9  448.49  5249.8  449.87
  5267.5  451.25  5298.0  450.36  5328.5  451.02  5353.7  452.89  5366.9  452.20
  5384.2  452.20  5452.2  454.69  5516.1  454.82  5548.0  455.87  5564.1  457.19
#Mann=5,-1,0
  4365.6    0.05       0  4843.9     0.1       0  4986.5    0.05       0
  5000.8    0.03       0  5006.8     0.1       0
Bank Sta=5000.8,5006.8
Exp/Cntr=0.3,0.1

Type RM Length L Ch R = 1,3605,557,557,557
BEGIN DESCRIPTION:
UNT025 IN SUCR 5.0
END DESCRIPTION:
XS GIS Cut Line= 3
      2294487.00     13453835.59      2293590.44     13454102.74
      2293314.19     13454415.22
#Sta/Elev= 30
  4380.9  454.13  4484.5  452.23  4693.2  444.72  4766.2  443.50  4865.4  444.23
  4961.2  444.98  4985.4  443.64  4996.6  441.96  4999.3  441.46  5002.6  441.96
  5027.1  444.39  5139.2  444.72  5180.0  445.20  5225.3  445.83  5247.4  447.15
  5267.1  446.10  5283.5  446.65  5322.2  446.88  5391.9  449.34  5421.1  448.86
  5464.3  450.15  5519.9  451.12  5548.3  452.95  5575.9  452.66  5611.9  455.15
  5640.4  454.92  5675.5  456.82  5715.6  457.13  5728.2  457.84  5733.5  458.10
#Mann=11,-1,0
  4380.9    0.05       0  4865.4     0.1       0  4996.6    0.07       0
  5002.6     0.1       0  5139.2    0.05       0  5180.0     0.1       0
  5283.5    0.05       0  5421.1     0.1       0  5464.3    0.05       0
  5715.6     0.1       0  5728.2    0.05       0
Bank Sta=4996.6,5002.6
Exp/Cntr=0.3,0.1

Type RM Length L Ch R = 1,3048,69,69,69
BEGIN DESCRIPTION:
UNT025 IN SUCR 4.1
END DESCRIPTION:
XS GIS Cut Line= 3
      2294331.77     13453471.46      2293743.18     13453492.29
      2293061.18     13453633.89
#Sta/Elev= 30
  4368.8  451.87  4660.3  445.24  4703.1  445.14  4813.1  442.22  4876.5  441.50
  4893.2  442.22  4913.2  441.17  4957.8  441.14  4973.5  437.76  4998.9  436.19
  5001.7  435.69  5004.9  436.19  5014.4  436.32  5034.8  438.19  5045.0  441.40
  5057.2  441.83  5085.9  442.42  5116.5  441.93  5152.3  442.36  5202.4  443.77
  5228.9  445.28  5290.2  445.08  5352.8  447.51  5433.1  447.87  5463.8  449.97
  5504.6  449.41  5548.2  450.79  5555.7  452.13  5606.8  451.90  5654.3  453.35
#Mann=4,-1,0
  4368.8    0.05       0  4876.5     0.1       0  4998.9    0.07       0
  5004.9     0.1       0
Bank Sta=4998.9,5004.9
Exp/Cntr=0.3,0.1

Type RM Length L Ch R = 1,2979,86,86,86
BEGIN DESCRIPTION:
UNT025 IN SUCR 4.0
END DESCRIPTION:
XS GIS Cut Line= 3
      2294318.72     13453428.49      2293708.02     13453432.40
      2293010.75     13453527.19
#Sta/Elev= 30
  4360.2  451.41  4621.2  445.70  4691.2  445.14  4741.2  443.47  4827.2  442.39
  4921.2  440.75  4941.2  441.37  4961.2  443.34  4968.6  445.37  4991.4  446.19
  5021.7  444.03  5031.8  442.78  5041.0  440.22  5043.8  439.72  5047.0  440.22
  5062.0  441.70  5183.1  442.72  5243.7  445.01  5324.4  445.57  5354.7  447.57
  5405.2  447.28  5465.7  449.87  5496.0  449.38  5536.4  450.46  5556.1  451.94
  5617.1  452.40  5638.7  453.58  5647.4  454.63  5667.6  459.06  5674.6  458.79
#Mann=4,-1,0
  4360.2    0.05       0  4827.2     0.1       0  5041.0    0.07       0
  5047.0     0.1       0
Bank Sta=5041,5047
Exp/Cntr=0.3,0.1

Type RM Length L Ch R = 1,2893,211,211,211
BEGIN DESCRIPTION:
UNT025 IN SUCR 4.2
END DESCRIPTION:
XS GIS Cut Line= 3
      2294322.64     13453363.39      2293478.86     13453352.97
      2293011.40     13453434.78
#Sta/Elev= 30
  4337.8  451.21  4422.7  450.07  4602.7  445.83  4682.7  445.37  4702.7  444.23
  4774.0  442.71  4802.8  443.14  4832.8  441.63  4882.8  440.94  4902.8  439.99
  4942.8  440.85  4999.8  438.88  5002.5  438.38  5005.8  438.88  5062.8  441.11
  5162.8  442.13  5213.3  443.83  5314.8  444.95  5365.5  447.41  5416.3  447.24
  5463.6  449.80  5497.5  449.31  5538.1  450.43  5568.6  452.13  5609.2  452.46
  5629.5  454.10  5636.9  455.81  5642.0  455.97  5649.8  457.35  5656.2  459.68
#Mann=4,-1,0
  4337.8    0.05       0  4774.0     0.1       0  4999.8    0.07       0
  5005.8     0.1       0
Bank Sta=4999.8,5005.8
Exp/Cntr=0.3,0.1

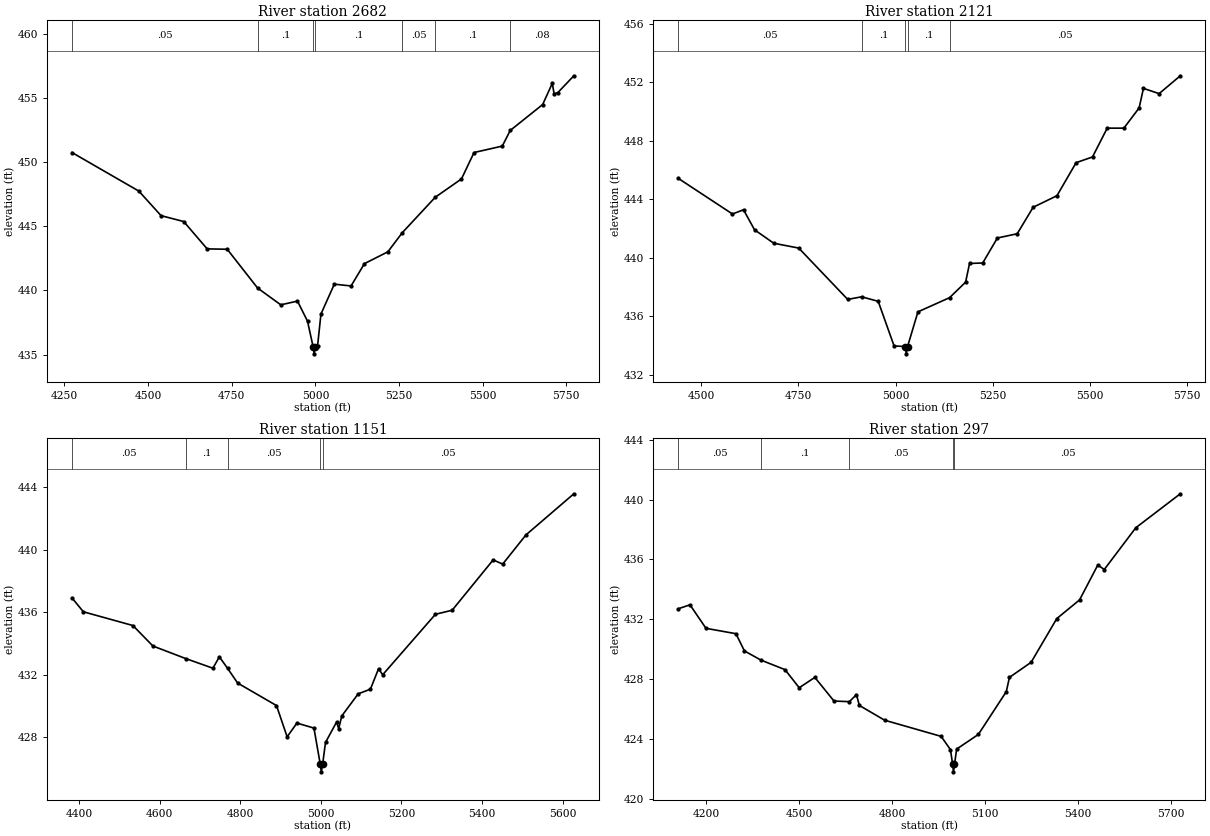
Type RM Length L Ch R = 1,2682,561,561,561
BEGIN DESCRIPTION:
UNT025 IN SUCR 3.0
END DESCRIPTION:
XS GIS Cut Line= 4
      2294328.56     13453237.84      2294025.16     13453147.27
      2293137.61     13453165.39      2292874.93     13453301.25
#Sta/Elev= 30
  4272.4  450.75  4472.5  447.74  4538.7  445.83  4606.5  445.37  4676.5  443.24
  4736.5  443.21  4827.2  440.19  4896.5  438.88  4946.5  439.17  4976.5  437.60
  4993.6  435.56  4996.3  435.06  4999.6  435.56  5006.6  435.70  5016.6  438.16
  5056.6  440.49  5106.6  440.35  5146.6  442.09  5216.6  443.01  5259.7  444.50
  5358.1  447.26  5436.6  448.69  5474.2  450.75  5558.6  451.25  5582.4  452.47
  5679.3  454.49  5708.0  456.14  5713.6  455.32  5724.3  455.41  5772.5  456.73
#Mann=7,-1,0
  4272.4    0.05       0  4827.2     0.1       0  4993.6    0.07       0
  4999.6     0.1       0  5259.7    0.05       0  5358.1     0.1       0
  5582.4    0.08       0
Bank Sta=4993.6,4999.6
Exp/Cntr=0.3,0.1

Type RM Length L Ch R = 1,2121,970,970,970
BEGIN DESCRIPTION:
UNT025 IN SUCR 2.0
END DESCRIPTION:
XS GIS Cut Line= 4
      2294179.13     13452862.00      2293993.46     13452676.33
      2293246.29     13452522.37      2292983.64     13452554.06
#Sta/Elev= 30
  4442.0  445.41  4581.0  442.98  4609.3  443.27  4637.6  441.90  4687.1  440.98
  4751.3  440.65  4877.1  437.14  4913.0  437.32  4955.5  437.01  4996.3  433.96
  5025.0  433.92  5027.8  433.42  5031.0  433.92  5057.6  436.29  5138.9  437.26
  5180.1  438.32  5190.3  439.60  5224.1  439.63  5261.8  441.34  5312.8  441.63
  5353.7  443.44  5414.9  444.23  5464.2  446.49  5506.3  446.88  5544.1  448.85
  5586.9  448.85  5626.1  450.23  5637.2  451.57  5677.5  451.21  5732.0  452.43
#Mann=5,-1,0
  4442.0    0.05       0  4913.0     0.1       0  5025.0    0.07       0
  5031.0     0.1       0  5138.9    0.05       0
Bank Sta=5025,5031
Exp/Cntr=0.3,0.1

Type RM Length L Ch R = 1,1151,854,854,854
BEGIN DESCRIPTION:
Mapping XS 5199b430
END DESCRIPTION:
XS GIS Cut Line= 4
      2294292.33     13451974.44      2294247.05     13451775.20
      2293554.22     13451661.99      2293220.97     13451725.04
#Sta/Elev= 30
  4382.4  436.91  4410.7  436.02  4533.7  435.14  4583.3  433.83  4664.4  433.03
  4732.2  432.41  4748.2  433.14  4768.6  432.40  4793.6  431.46  4890.0  430.02
  4916.4  428.02  4940.7  428.90  4982.9  428.58  4998.5  426.28  5001.2  425.78
  5004.5  426.28  5011.6  427.66  5039.2  428.97  5044.3  428.54  5052.1  429.36
  5092.7  430.77  5123.1  431.07  5143.3  432.38  5153.5  431.99  5284.4  435.86
  5325.9  436.12  5427.7  439.34  5451.3  439.07  5509.1  440.94  5627.9  443.57
#Mann=5,-1,0
  4382.4    0.05       0  4664.4     0.1       0  4768.6    0.05       0
  4998.5    0.03       0  5004.5    0.05       0
Bank Sta=4998.5,5004.5
Exp/Cntr=0.3,0.1

Type RM Length L Ch R = 1,297,0,0,0
BEGIN DESCRIPTION:
UNT025 IN SUCR 1.0
END DESCRIPTION:
XS GIS Cut Line= 4
      2294378.37     13451652.96      2294188.18     13450910.29
      2293739.88     13450901.23      2293351.55     13451009.60
#Sta/Elev= 30
  4111.6  432.71  4148.9  432.97  4200.5  431.40  4297.1  431.04  4324.4  429.89
  4377.3  429.28  4455.1  428.64  4501.1  427.43  4551.5  428.12  4613.2  426.54
  4662.8  426.50  4685.7  426.97  4694.8  426.25  4776.4  425.26  4958.7  424.18
  4988.7  423.29  4995.7  422.31  4998.5  421.81  5001.7  422.31  5008.7  423.33
  5078.7  424.31  5168.8  427.17  5178.8  428.12  5248.8  429.13  5331.5  432.05
  5405.0  433.30  5463.8  435.63  5484.6  435.33  5586.3  438.12  5729.8  440.39
#Mann=5,-1,0
  4111.6    0.05       0  4377.3     0.1       0  4662.8    0.05       0
  4995.7    0.03       0  5001.7    0.05       0
Bank Sta=4995.7,5001.7
Exp/Cntr=0.3,0.1

Chan Stop Cuts=-1