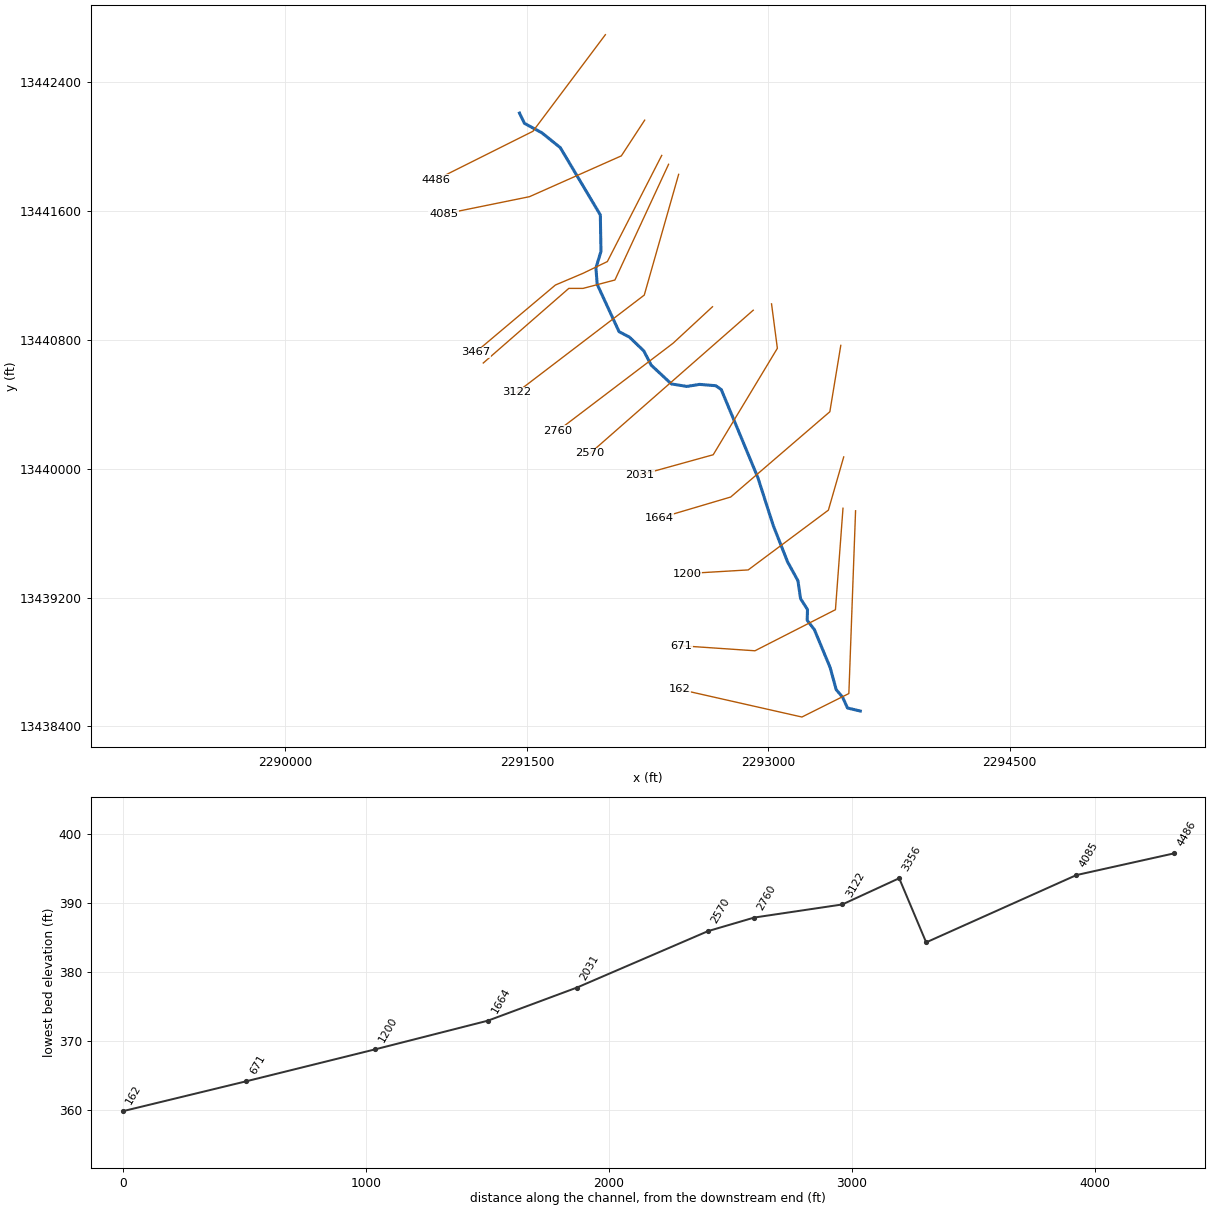
--- UNT026 IN SUCR.prj (project) ---

Proj Title=UNT026 IN SUCR Base Level Engineering
Current Plan=p01
Default Exp/Contr=0.3,0.1
English Units
Geom File=g01
Flow File=f01
Plan File=p01
Y Axis Title=Elevation
X Axis Title(PF)=Main Channel Distance
X Axis Title(XS)=Station
BEGIN DESCRIPTION:
UNT026 IN SUCR
END DESCRIPTION:
DSS Export Rating Curves= 0
DSS Export Rating Curve Sorted= 0
DSS Export Volume Flow Curves= 0
DXF OffsetX= 0
DXF OffsetY= 0
DXF ScaleX= 1
DXF ScaleY= 10

--- UNT026 IN SUCR.p01 (plan) ---

Plan Title=Multiple Run
Short Identifier=Multiple
Geom File=g01
Flow File=f01
Subcritical Flow
K Sum by GR= 0
Std Step Tol= 0.01
Critical Tol= 0.01
Num of Std Step Trials= 20
Max Error Tol= 0.3
Flow Tol Ratio= 0.001
Split Flow NTrial= 30
Split Flow Tol= 0.02
Split Flow Ratio= 0.02
Log Output Level= 0
Friction Slope Method= 1
Unsteady Friction Slope Method= 2
Unsteady Bridges Friction Slope Method= 1
Parabolic Critical Depth
Global Vel Dist=  1 , 1 , 1
Global Log Level= 0
CheckData=True
Encroach Param= -1, 0, 0, 0
BEGIN DESCRIPTION:
Multiple Run
END DESCRIPTION:

--- UNT026 IN SUCR.f01 (steady flow) ---

Flow Title=Multiple
Program Version=4.10
Number of Profiles= 7
Profile Names=10-year,25-year,50-year,1pct_min,100-year,1pct_plu,500-year
River Rch & RM=UNT026 IN SUCR,Reach-1         ,4486
     274     368     442     390     527     713     753
River Rch & RM=UNT026 IN SUCR,Reach-1         ,2570
     329     448     544     483     654     884     950
Boundary for River Rch & Prof#=UNT026 IN SUCR,Reach-1         , 1
Up Type= 0
Dn Type= 3
Dn Slope=0.0086
Boundary for River Rch & Prof#=UNT026 IN SUCR,Reach-1         , 2
Up Type= 0
Dn Type= 3
Dn Slope=0.0086
Boundary for River Rch & Prof#=UNT026 IN SUCR,Reach-1         , 3
Up Type= 0
Dn Type= 3
Dn Slope=0.0086
Boundary for River Rch & Prof#=UNT026 IN SUCR,Reach-1         , 4
Up Type= 0
Dn Type= 3
Dn Slope=0.0086
Boundary for River Rch & Prof#=UNT026 IN SUCR,Reach-1         , 5
Up Type= 0
Dn Type= 3
Dn Slope=0.0086
Boundary for River Rch & Prof#=UNT026 IN SUCR,Reach-1         , 6
Up Type= 0
Dn Type= 3
Dn Slope=0.0086
Boundary for River Rch & Prof#=UNT026 IN SUCR,Reach-1         , 7
Up Type= 0
Dn Type= 3
Dn Slope=0.0086
DSS Import GetInterval= 0
DSS Import GetPeak= 0
DSS Import FillOption= 0

--- UNT026 IN SUCR.g01 (geometry) ---

Geom Title=Existing Conditions
Program Version=4.10

River Reach=UNT026 IN SUCR  ,Reach-1
Reach XY= 30
      2291454.25     13442209.81      2291485.04     13442146.17
      2291593.11     13442087.57      2291707.69     13441995.13
      2291956.39     13441577.16       2291960.3     13441350.59
      2291929.05     13441247.73      2291936.86     13441146.17
      2292072.79     13440851.97      2292136.86     13440818.58
      2292226.57     13440732.32      2292272.15     13440644.43
      2292398.01     13440527.24      2292494.59     13440512.05
      2292572.27      13440524.7      2292673.49      13440516.4
      2292707.71     13440492.24      2292934.94      13439945.7
      2293030.48       13439648.      2293119.36     13439422.53
      2293183.75     13439305.21      2293200.42      13439193.3
      2293243.26     13439126.17      2293241.45     13439058.52
      2293285.71     13439002.03      2293384.08     13438765.35
      2293421.55     13438628.44      2293461.31      13438581.6
      2293491.74     13438514.55      2293570.88     13438495.55

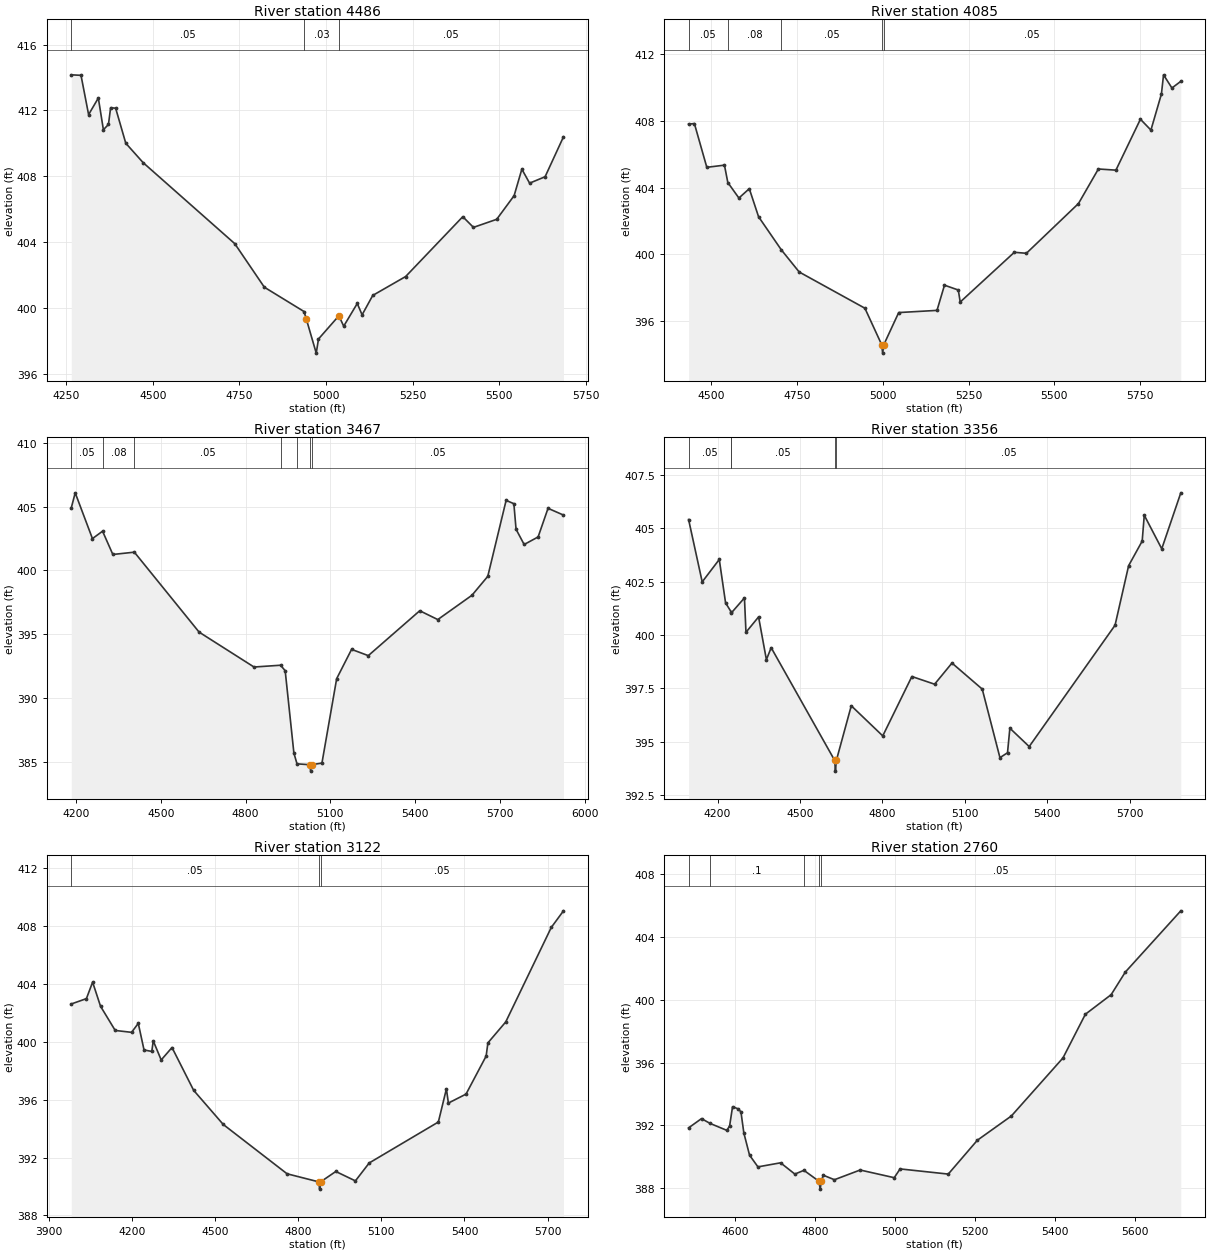
Type RM Length L Ch R = 1 ,4486    ,401,401,401
BEGIN DESCRIPTION:
UNT026 IN SUCR 10.0
END DESCRIPTION:
XS GIS Cut Line= 3
      2291987.73     13442696.87      2291537.72     13442096.85
      2290937.75     13441796.87
#Sta/Elev= 30
  4264.8  414.17  4292.9  414.14  4314.8  411.75  4342.9  412.76  4357.5  410.83
  4372.1  411.15  4378.4  412.17  4392.9  412.14  4422.1  410.01  4472.1  408.83
  4736.7   403.9  4822.1  401.25  4936.7  399.77  4942.9  399.34  4971.9  397.24
  4978.4   398.1  5037.2  399.51  5051.2  398.88  5090.3  400.26  5104.3  399.57
    5135  400.75    5230   401.9  5394.9  405.54  5425.7  404.89  5492.8  405.38
  5543.1  406.82  5565.4  408.43  5587.8  407.58  5632.5  407.97  5685.6   410.4
#Mann= 3 ,-1 , 0
  4264.8     .05       0  4936.7     .03       0  5037.2     .05       0
Bank Sta=4942.9,5037.2
XS Rating Curve= 0 ,0
Exp/Cntr=0.3,0.1

Type RM Length L Ch R = 1 ,4085    ,618,618,618
BEGIN DESCRIPTION:
UNT026 IN SUCR 9.0
END DESCRIPTION:
XS GIS Cut Line= 4
      2292231.94     13442166.11      2292087.04     13441944.25
      2291516.48     13441690.66      2290982.38     13441582.03
#Sta/Elev= 30
  4433.9  407.81  4450.8  407.84    4487  405.22  4538.4  405.35  4548.2  404.31
  4580.5  403.38  4610.8  403.94  4637.8  402.26    4704  400.28  4756.2  398.95
  4947.7  396.78  4996.7  394.59  4999.4  394.09  5002.7  394.59  5046.2  396.52
  5157.8  396.65  5179.6  398.16  5219.9  397.87  5225.4  397.15  5383.2  400.13
  5418.3  400.07  5570.1  403.05  5628.1  405.12  5679.2  405.05  5750.6   408.1
  5781.2  407.45  5811.8  409.61    5818  410.76  5842.4  409.97  5868.3  410.37
#Mann= 5 ,-1 , 0
  4433.9     .05       0  4548.2     .08       0    4704     .05       0
  4996.7     .03       0  5002.7     .05       0
Bank Sta=4996.7,5002.7
XS Rating Curve= 0 ,0
Exp/Cntr=0.3,0.1

Type RM Length L Ch R = 1 ,3467    ,111,111,111
BEGIN DESCRIPTION:
UNT026 IN SUCR 8.0
END DESCRIPTION:
XS GIS Cut Line= 5
       2292337.7     13441946.82      2292000.11     13441287.61
      2291849.07     13441214.69      2291677.19     13441141.78
      2291182.56     13440725.25
#Sta/Elev= 30
  4183.5  404.89  4197.4  406.07  4258.4  402.49  4294.2  403.07  4330.6  401.25
  4406.7  401.43  4635.8  395.18  4830.1  392.45  4924.1  392.59  4940.4  392.16
  4971.2  385.73  4982.2  384.88  5027.8  384.81  5030.6  384.31  5033.8  384.81
  5070.5  384.94  5122.6  391.54  5175.4  393.83  5234.5  393.34  5416.6  396.85
  5480.4  396.16  5601.3  398.06  5657.3  399.54  5722.2  405.48  5749.6  405.22
  5757.4  403.22    5786  402.03  5835.4  402.62  5870.5  404.86  5925.2  404.33
#Mann= 7 ,-1 , 0
  4183.5     .05       0  4294.2     .08       0  4406.7     .05       0
  4924.1      .1       0  4982.2     .05       0  5027.8     .03       0
  5033.8     .05       0
Bank Sta=5027.8,5033.8
XS Rating Curve= 0 ,0
Exp/Cntr=0.3,0.1

Type RM Length L Ch R = 1 ,3356    ,234,234,234
BEGIN DESCRIPTION:
Mapping XS 1929ef58
END DESCRIPTION:
XS GIS Cut Line= 5
       2292380.3     13441891.74      2292046.98     13441173.03
      2291849.07     13441120.94      2291760.53     13441120.94
      2291229.27      13440657.4
#Sta/Elev= 30
  4094.7  405.41  4144.2  402.49  4206.3  403.54  4229.2  401.51  4249.2  401.09
  4250.4  401.04  4297.9  401.74  4303.4  400.13  4349.3  400.85  4377.7  398.85
  4395.1  399.41  4626.2  394.13  4628.9  393.63  4632.2  394.13  4686.5  396.69
    4801  395.28  4906.9  398.06  4989.6   397.7  5052.8  398.69  5162.9  397.47
  5227.3  394.26  5254.8  394.49  5263.4  395.64  5333.7  394.78    5646  400.46
  5695.4  403.25  5744.7   404.4  5752.3  405.61  5815.9  404.04  5885.2  406.66
#Mann= 5 ,-1 , 0
  4094.7     .05       0  4249.2     .08       0  4250.4     .05       0
  4626.2     .03       0  4632.2     .05       0
Bank Sta=4626.2,4632.2
XS Rating Curve= 0 ,0
Exp/Cntr=0.3,0.1

Type RM Length L Ch R = 1 ,3122    ,362,362,362
BEGIN DESCRIPTION:
UNT026 IN SUCR 7.0
END DESCRIPTION:
XS GIS Cut Line= 3
      2292442.83     13441829.32      2292229.28     13441079.28
      2291437.63     13440475.12
#Sta/Elev= 30
  3981.5  402.62  4036.1  402.99  4058.5  404.13  4087.1  402.46    4140  400.79
  4199.1  400.66  4223.2  401.28    4244  399.44    4272  399.34  4277.2  400.07
  4305.9  398.75  4344.9  399.61    4423  396.65  4529.8  394.29    4760  390.88
  4874.7  390.32  4877.4  389.82  4880.7  390.32  4935.8  391.04  5006.5  390.39
  5056.4  391.63  5305.8  394.46  5334.8  396.75    5342  395.77  5405.6  396.39
  5478.2  399.02  5484.5  399.93  5548.9  401.38  5713.1  407.91  5757.2  409.06
#Mann= 3 ,-1 , 0
  3981.5     .05       0  4874.7     .03       0  4880.7     .05       0
Bank Sta=4874.7,4880.7
XS Rating Curve= 0 ,0
Exp/Cntr=0.3,0.1

Type RM Length L Ch R = 1 ,2760    ,190,190,190
BEGIN DESCRIPTION:
UNT026 IN SUCR 6.0
END DESCRIPTION:
XS GIS Cut Line= 3
      2292653.09      13441006.9      2292408.55     13440780.47
      2291693.08     13440237.08
#Sta/Elev= 30
  4483.5  391.83  4515.8  392.42  4537.5  392.11  4579.3  391.67  4586.2  391.96
  4593.5  393.18  4607.7  393.04  4614.5  392.85  4621.8   391.5    4636  390.09
    4657  389.34  4713.7   389.6  4749.4  388.88  4772.1  389.12  4809.9  388.42
  4812.7  387.92  4815.9  388.42  4820.4  388.81  4848.4  388.52  4912.8  389.14
  4998.1  388.65  5012.7  389.21  5133.3  388.88  5206.1  391.04  5291.3  392.59
  5420.3  396.29  5476.4  399.08  5540.9  400.33  5576.3  401.77  5715.2  405.68
#Mann= 5 ,-1 , 0
  4483.5     .05       0  4537.5      .1       0  4772.1     .05       0
  4809.9     .04       0  4815.9     .05       0
Bank Sta=4809.9,4815.9
XS Rating Curve= 0 ,0
Exp/Cntr=0.3,0.1

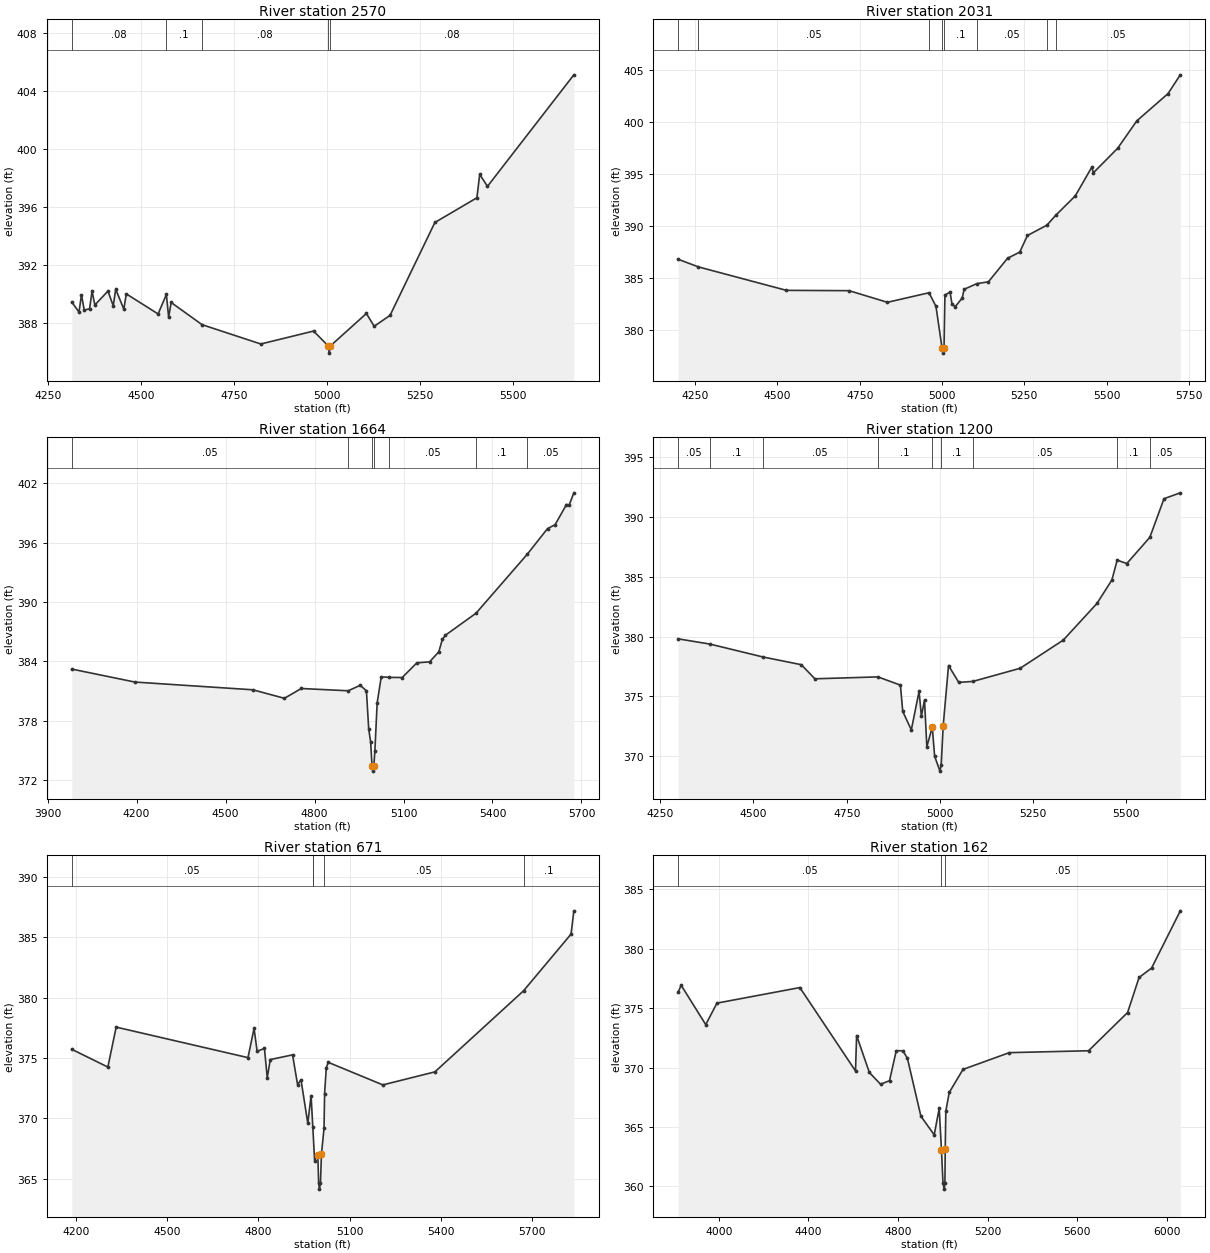
Type RM Length L Ch R = 1 ,2570    ,539,539,539
BEGIN DESCRIPTION:
UNT026 IN SUCR 5.0
END DESCRIPTION:
XS GIS Cut Line= 2
      2292906.33      13440985.5       2291891.7     13440095.75
#Sta/Elev= 30
  4313.3  389.47  4332.7  388.78  4339.4  389.96  4346.9  388.91  4361.2  389.01
  4367.8  390.22  4375.4  389.27  4410.5  390.22  4424.8  389.21  4431.4  390.35
  4453.2  388.98  4459.9  390.03  4545.3  388.65  4567.6  389.99  4573.7  388.42
  4580.4  389.44  4663.5  387.91  4821.4  386.58  4963.2  387.47  5002.5  386.45
  5005.3  385.95  5008.5  386.45  5105.2  388.68  5126.1   387.8  5168.8  388.55
  5289.3  394.95  5402.2  396.65  5409.8  398.26  5430.7  397.44  5662.8  405.12
#Mann= 5 ,-1 , 0
  4313.3     .08       0  4567.6      .1       0  4663.5     .08       0
  5002.5     .07       0  5008.5     .08       0
Bank Sta=5002.5,5008.5
XS Rating Curve= 0 ,0
Exp/Cntr=0.3,0.1

Type RM Length L Ch R = 1 ,2031    ,367,367,367
BEGIN DESCRIPTION:
UNT026 IN SUCR 4.0
END DESCRIPTION:
XS GIS Cut Line= 4
      2293019.88       13441025.       2293056.1     13440748.77
      2292657.61     13440087.64      2292200.29     13439960.86
#Sta/Elev= 30
  4198.6  386.78  4259.6  386.05  4527.2  383.79  4717.5  383.76    4834  382.64
  4960.3  383.56  4981.5  382.25  4999.9  378.25  5002.6  377.75  5005.9  378.25
  5008.7  383.33  5024.3  383.63  5030.1  382.48  5039.8  382.22  5061.1  383.04
    5067  383.89  5105.7  384.44  5140.7  384.61    5199  386.88  5235.9  387.47
  5259.4  389.07  5318.4  390.06  5345.2  391.01  5404.7  392.88  5454.7  395.64
  5459.8  395.11  5533.6  397.47  5591.5   400.1  5686.3  402.72  5723.7  404.53
#Mann= 8 ,-1 , 0
  4198.6     .08       0  4259.6     .05       0  4960.3      .1       0
  4999.9     .07       0  5005.9      .1       0  5105.7     .05       0
  5318.4      .1       0  5345.2     .05       0
Bank Sta=4999.9,5005.9
XS Rating Curve= 0 ,0
Exp/Cntr=0.3,0.1

Type RM Length L Ch R = 1 ,1664    ,464,464,464
BEGIN DESCRIPTION:
UNT026 IN SUCR 3.0
END DESCRIPTION:
XS GIS Cut Line= 4
      2293450.06     13440766.88      2293382.14     13440354.81
      2292766.29       13439825.      2292322.62     13439693.71
#Sta/Elev= 30
  3981.6  383.23  4194.5  381.92    4592  381.14  4698.5  380.28  4755.5  381.27
  4913.4  381.04  4954.1  381.59    4975  381.04  4982.7   377.2  4989.3  375.85
  4993.9  373.43  4996.7  372.93  4999.9  373.43  5003.5  374.97  5011.2  379.82
    5025  382.45  5052.4  382.39  5095.7  382.38  5145.1  383.86  5187.9  383.96
    5219  384.97    5231  386.22  5241.4  386.65  5344.6  388.87  5517.5  394.83
  5585.6  397.41    5611   397.8  5649.5  399.84  5658.6   399.8  5674.3  401.02
#Mann= 7 ,-1 , 0
  3981.6     .05       0  4913.4      .1       0  4993.9     .07       0
  4999.9      .1       0  5052.4     .05       0  5344.6      .1       0
  5517.5     .05       0
Bank Sta=4993.9,4999.9
XS Rating Curve= 0 ,0
Exp/Cntr=0.3,0.1

Type RM Length L Ch R = 1 ,1200    ,529,529,529
BEGIN DESCRIPTION:
UNT026 IN SUCR 2.0
END DESCRIPTION:
XS GIS Cut Line= 4
      2293468.17     13440074.04      2293373.08     13439743.49
      2292874.97     13439372.17      2292494.58     13439349.53
#Sta/Elev= 30
  4298.2  379.82  4383.8  379.38  4524.6  378.31  4628.2  377.66  4664.6  376.48
  4833.7  376.64    4894  375.95  4900.2  373.75  4923.2  372.21    4944  375.43
  4950.2  373.36  4958.6   374.7  4964.8   370.8  4979.4  372.44  4985.7  370.01
    5000  368.76  5003.3  369.26  5008.7  372.57    5023  377.59  5050.3  376.18
  5088.1  376.26  5215.1  377.36  5330.8  379.72    5421  382.78    5461  384.74
  5475.2   386.4  5501.1  386.12  5562.8  388.31  5600.8  391.54  5644.5  392.03
#Mann= 9 ,-1 , 0
  4298.2     .05       0  4383.8      .1       0  4524.6     .05       0
  4833.7      .1       0  4979.4     .07       0  5003.3      .1       0
  5088.1     .05       0  5475.2      .1       0  5562.8     .05       0
Bank Sta=4979.4,5008.7
XS Rating Curve= 0 ,0
Exp/Cntr=0.3,0.1

Type RM Length L Ch R = 1 ,671     ,509,509,509
BEGIN DESCRIPTION:
Mapping XS ddc60517
END DESCRIPTION:
XS GIS Cut Line= 4
      2293463.75     13439755.32      2293416.87     13439125.06
      2292916.87     13438869.86      2292458.49     13438901.11
#Sta/Elev= 30
  4185.5  375.72  4304.3  374.25  4331.7  377.56  4765.6  375.03  4785.6  377.46
  4795.6  375.56  4819.8  375.79    4829  373.36    4839  374.87  4912.3  375.26
  4928.8   372.8  4940.1   373.2  4962.5  369.59  4973.3  371.88  4978.9  369.32
  4984.9   366.5  4995.5  366.93  4998.2  364.63  5000.9  364.13  5004.2  364.63
  5007.4  367.03 5015.91  369.16  5017.8  372.05  5023.4  374.21  5029.9  374.64
  5209.5  372.77  5380.9  373.85  5672.7  380.57  5829.1  385.27  5838.3   387.2
#Mann= 5 ,-1 , 0
  4185.5     .05       0  4978.9      .1       0  4978.9     .03       0
 5015.91     .05       0  5672.7      .1       0
Bank Sta=4995.5,5007.4
XS Rating Curve= 0 ,0
Exp/Cntr=0.3,0.1

Type RM Length L Ch R = 1 ,162     ,0,0,0
BEGIN DESCRIPTION:
UNT026 IN SUCR 1.0
END DESCRIPTION:
XS GIS Cut Line= 4
      2293541.87     13439739.61       2293500.2     13438604.23
      2293208.53      13438458.4      2292448.15     13438630.27
#Sta/Elev= 30
  3818.4  376.35  3831.2  376.94  3941.2  373.62  3991.3  375.43  4361.5  376.74
  4609.9  369.72  4614.9   372.7  4671.7  369.59  4721.8   368.6  4761.8   368.9
  4791.8  371.42  4821.8  371.42  4841.8  370.77  4901.9  365.91  4961.4  364.34
  4983.7  366.57 4993.67  363.08  5000.5   360.3  5005.8  359.77  5009.1  360.27
 5010.53  363.11  5013.2  366.34  5028.5  367.91    5090  369.85  5296.6  371.26
  5650.5  371.42  5824.8  374.64  5876.1  377.59  5931.9  378.38  6060.2   383.2
#Mann= 3 , 0 , 0
  3818.4     .05       0 4993.67     .03       0 5010.53     .05       0
Bank Sta=4993.67,5010.53
XS Rating Curve= 0 ,0
Exp/Cntr=0.3,0.1

Chan Stop Cuts=-1
Use User Specified Reach Order=0
Composite Channel Slope=5