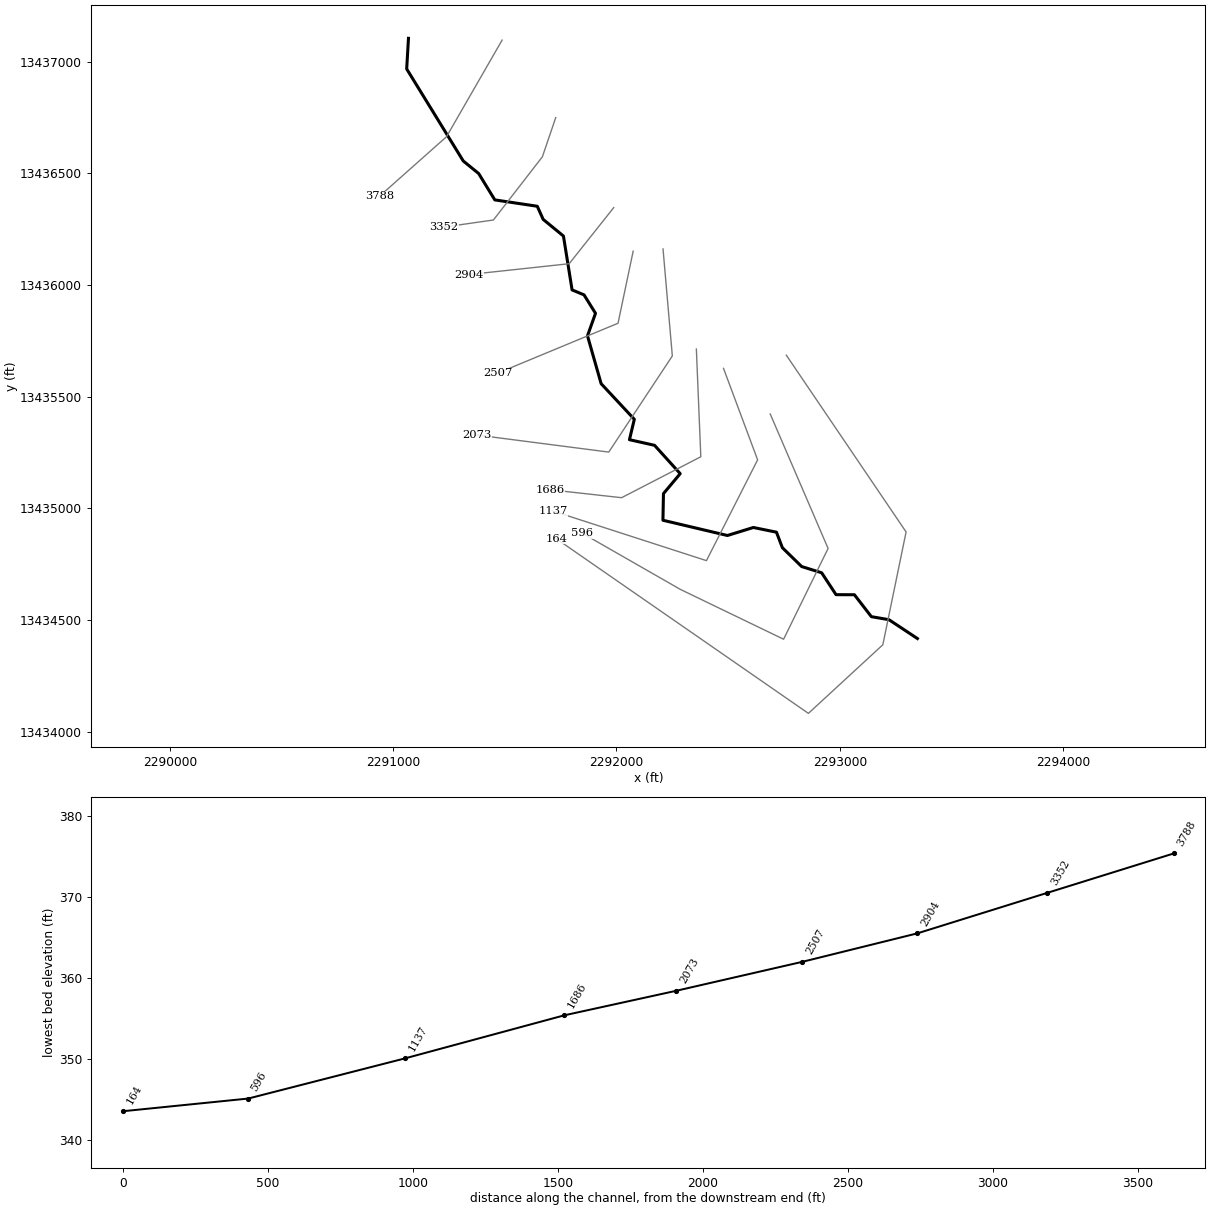
--- UNT027 IN SUCR.prj (project) ---

Proj Title=UNT027 IN SUCR Base Level Engineering
Current Plan=p01
Default Exp/Contr=0.3,0.1
English Units
Geom File=g01
Flow File=f01
Plan File=p01
BEGIN DESCRIPTION:
UNT027 IN SUCR
END DESCRIPTION:

--- UNT027 IN SUCR.p01 (plan) ---

Plan Title=Multiple Run
Short Identifier=Multiple
Geom File=g01
Flow File=f01
Subcritical Flow
K Sum by GR= 0
Std Step Tol= 0.01
Critical Tol= 0.01
Num of Std Step Trials= 20
Max Error Tol= 0.3
Flow Tol Ratio= 0.001
Split Flow NTrial= 30
Split Flow Tol= 0.02
Split Flow Ratio= 0.02
Log Output Level= 0
Friction Slope Method= 1
Unsteady Friction Slope Method= 2
Unsteady Bridges Friction Slope Method= 1
Parabolic Critical Depth
Global Vel Dist=  1 , 1 , 1
Global Log Level= 0
CheckData=True
Encroach Param= -1, 0, 0, 0
BEGIN DESCRIPTION:
Multiple Run
END DESCRIPTION:

--- UNT027 IN SUCR.f01 (steady flow) ---

Flow Title=Multiple
Number of Profiles=7
Profile Names=10-year,25-year,50-year,1pct_min,100-year,1pct_plu,500-year
River Rch & RM= UNT027 IN SUCR,Reach-1,3788
     340     466     570     510     690     933    1018
Boundary for River Rch & Prof#=UNT027 IN SUCR,Reach-1,1
Up Type=0
Dn Type=3
Dn Slope=0.005
Boundary for River Rch & Prof#=UNT027 IN SUCR,Reach-1,2
Up Type=0
Dn Type=3
Dn Slope=0.005
Boundary for River Rch & Prof#=UNT027 IN SUCR,Reach-1,3
Up Type=0
Dn Type=3
Dn Slope=0.005
Boundary for River Rch & Prof#=UNT027 IN SUCR,Reach-1,4
Up Type=0
Dn Type=3
Dn Slope=0.005
Boundary for River Rch & Prof#=UNT027 IN SUCR,Reach-1,5
Up Type=0
Dn Type=3
Dn Slope=0.005
Boundary for River Rch & Prof#=UNT027 IN SUCR,Reach-1,6
Up Type=0
Dn Type=3
Dn Slope=0.005
Boundary for River Rch & Prof#=UNT027 IN SUCR,Reach-1,7
Up Type=0
Dn Type=3
Dn Slope=0.005

--- UNT027 IN SUCR.g01 (geometry) ---

Geom Title=Existing Conditions

River Reach=UNT027 IN SUCR,Reach-1
Reach XY= 30
      2291068.44     13437104.83      2291060.42     13436967.83
      2291313.78     13436555.53      2291382.78     13436499.37
      2291455.09     13436381.28      2291645.21     13436352.81
      2291671.62     13436294.05      2291762.45     13436219.47
      2291801.16     13435978.20      2291854.64     13435955.97
      2291906.02     13435873.33      2291870.17     13435772.51
      2291931.25     13435558.27      2292079.85     13435398.80
      2292058.09     13435307.40      2292170.42     13435282.23
      2292285.35     13435155.27      2292210.38     13435065.93
      2292208.01     13434946.64      2292496.78     13434878.35
      2292613.12     13434914.25      2292716.43     13434893.16
      2292742.85     13434823.71      2292829.29     13434739.35
      2292918.90     13434711.34      2292983.19     13434613.38
      2293065.52     13434613.02      2293141.43     13434514.84
      2293220.12     13434501.28      2293347.72     13434416.86

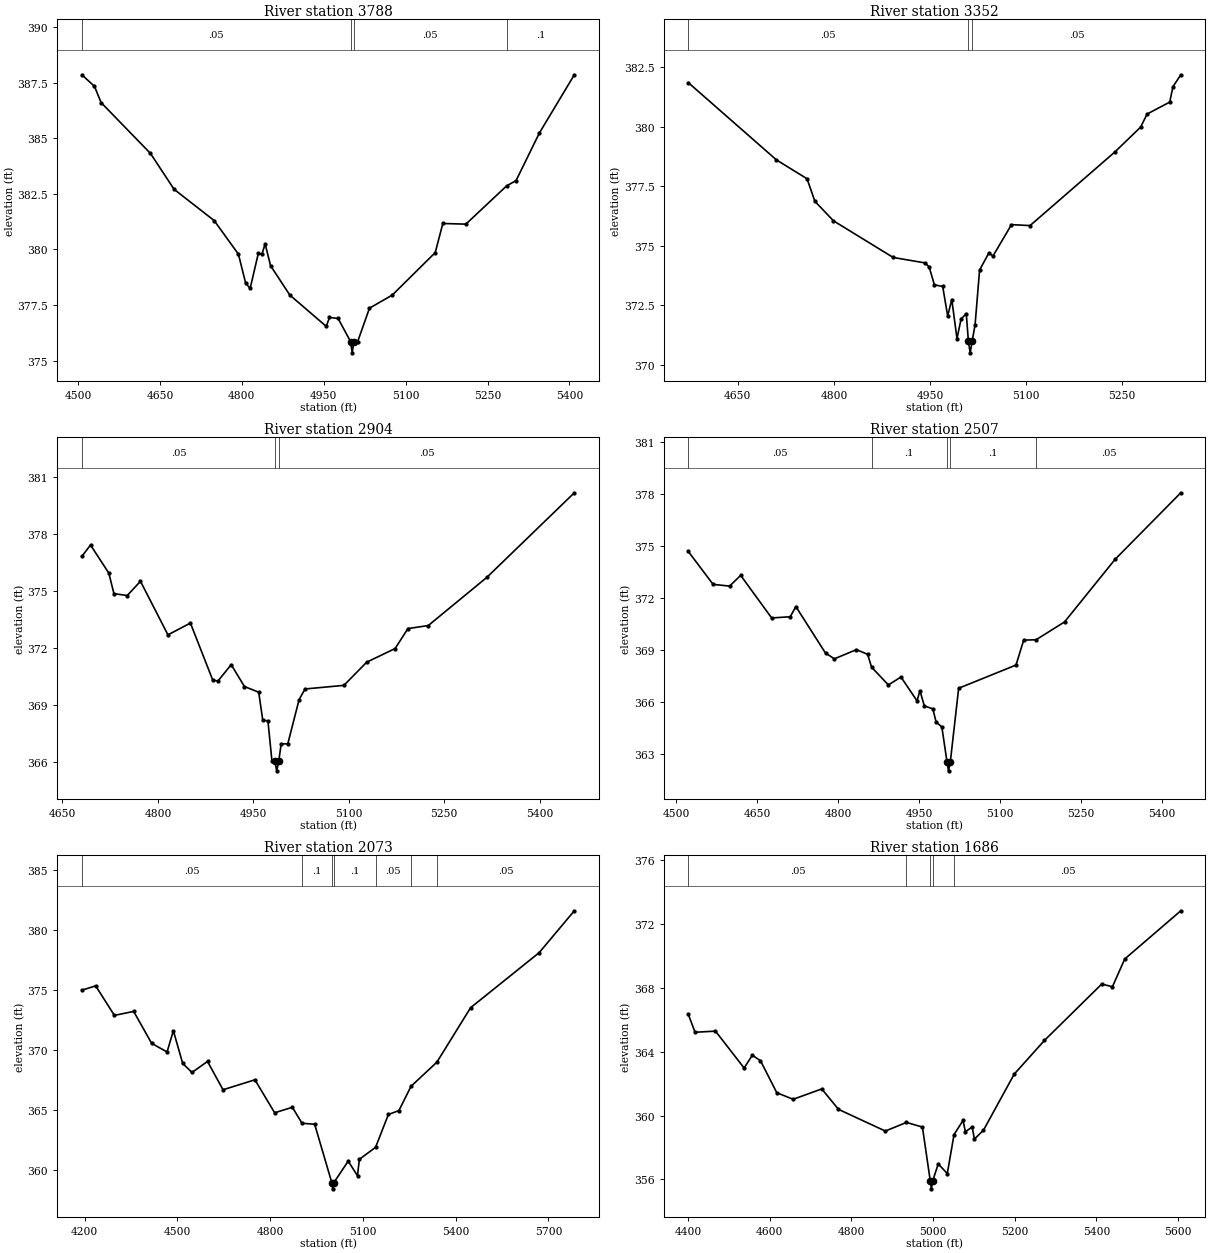
Type RM Length L Ch R = 1,3788,436,436,436
BEGIN DESCRIPTION:
UNT027 IN SUCR 4.0
END DESCRIPTION:
XS GIS Cut Line= 3
      2291487.72     13437096.85      2291238.64     13436664.09
      2290937.70     13436396.84
#Sta/Elev= 30
  4507.1  387.86  4530.2  387.34  4542.3  386.61  4632.8  384.32  4675.9  382.71
  4749.4  381.30  4793.8  379.79  4807.1  378.48  4815.3  378.25  4830.2  379.82
  4836.9  379.79  4842.7  380.25  4852.7  379.27  4887.9  377.95  4954.7  376.54
  4960.5  376.94  4976.3  376.90  4999.3  375.85  5002.1  375.35  5005.3  375.85
  5012.1  375.85  5033.8  377.36  5075.6  377.95  5154.2  379.86  5168.1  381.17
  5210.3  381.14  5284.9  382.86  5302.2  383.10  5344.9  385.24  5408.9  387.86
#Mann=4,-1,0
  4507.1    0.05       0  4999.3    0.03       0  5005.3    0.05       0
  5284.9     0.1       0
Bank Sta=4999.3,5005.3
Exp/Cntr=0.3,0.1

Type RM Length L Ch R = 1,3352,448,448,448
BEGIN DESCRIPTION:
UNT027 IN SUCR 3.0
END DESCRIPTION:
XS GIS Cut Line= 4
      2291727.91     13436749.73      2291668.11     13436574.30
      2291448.87     13436291.29      2291225.67     13436259.40
#Sta/Elev= 30
  4572.7  381.86  4710.3  378.61  4758.0  377.82  4770.3  376.87  4799.3  376.05
  4892.5  374.51  4942.3  374.28  4948.7  374.11  4956.8  373.36  4969.8  373.29
  4977.6  372.05  4984.0  372.74  4992.1  371.10  4998.5  371.92  5006.6  372.15
  5009.9  371.00  5012.7  370.50  5015.9  371.00  5020.4  371.69  5027.4  373.98
  5041.9  374.70  5048.3  374.57  5077.2  375.89  5106.2  375.85  5238.4  378.94
  5278.8  379.99  5288.9  380.54  5324.2  381.04  5329.3  381.69  5341.5  382.19
#Mann=3,-1,0
  4572.7    0.05       0  5009.9    0.03       0  5015.9    0.05       0
Bank Sta=5009.9,5015.9
Exp/Cntr=0.3,0.1

Type RM Length L Ch R = 1,2904,397,397,397
BEGIN DESCRIPTION:
UNT027 IN SUCR 2.0
END DESCRIPTION:
XS GIS Cut Line= 3
      2291987.70     13436346.82      2291788.12     13436095.51
      2291337.76     13436046.86
#Sta/Elev= 30
  4680.5  376.80  4694.1  377.40  4722.9  375.92  4730.9  374.84  4751.8  374.74
  4772.6  375.49  4815.8  372.67  4851.1  373.29  4886.3  370.28  4894.4  370.24
  4915.2  371.10  4936.0  369.95  4958.4  369.65  4964.8  368.18  4972.9  368.14
  4979.2  366.04  4983.9  366.01  4986.7  365.51  4989.9  366.01  4993.7  366.93
  5004.1  366.93  5021.9  369.26  5031.2  369.82  5092.3  370.01  5128.1  371.23
  5172.8  371.95  5192.9  373.00  5224.9  373.16  5316.7  375.69  5454.4  380.15
#Mann=3,-1,0
  4680.5    0.05       0  4983.9    0.03       0  4989.9    0.05       0
Bank Sta=4983.9,4989.9
Exp/Cntr=0.3,0.1

Type RM Length L Ch R = 1,2507,434,434,434
BEGIN DESCRIPTION:
Mapping XS a3301eda
END DESCRIPTION:
XS GIS Cut Line= 3
      2292074.70     13436151.76      2292006.93     13435828.89
      2291468.80     13435605.67
#Sta/Elev= 30
  4522.1  374.67  4568.0  372.77  4598.6  372.67  4619.1  373.29  4676.5  370.83
  4711.0  370.90  4721.3  371.49  4776.3  368.80  4792.8  368.47  4833.6  369.00
  4854.3  368.73  4861.6  367.99  4892.8  366.96  4916.1  367.42  4945.9  366.04
  4951.3  366.63  4959.4  365.75  4975.2  365.58  4981.1  364.83  4991.9  364.53
  5001.5  362.50  5004.2  362.00  5007.5  362.50  5023.0  366.77  5129.3  368.11
  5143.5  369.55  5166.4  369.57  5219.2  370.60  5312.7  374.21  5434.6  378.06
#Mann=5,-1,0
  4522.1    0.05       0  4861.6     0.1       0  5001.5    0.07       0
  5007.5     0.1       0  5166.4    0.05       0
Bank Sta=5001.5,5007.5
Exp/Cntr=0.3,0.1

Type RM Length L Ch R = 1,2073,387,387,387
BEGIN DESCRIPTION:
Mapping XS e5e87f5a
END DESCRIPTION:
XS GIS Cut Line= 4
      2292208.44     13436161.63      2292250.11     13435682.43
      2291965.39     13435251.87      2291375.10     13435328.26
#Sta/Elev= 30
  4191.2  375.00  4235.9  375.36  4296.4  372.90  4358.8  373.23  4416.8  370.57
  4466.7  369.85  4487.1  371.62  4517.2  368.90  4547.3  368.14  4597.5  369.06
  4647.7  366.70  4750.8  367.53  4814.6  364.78  4871.8  365.24  4903.1  363.91
  4944.0  363.82  4999.6  358.94  5002.3  358.44  5005.6  358.94  5052.4  360.75
  5082.5  359.53  5088.5  360.90  5140.9  361.90  5182.4  364.64  5216.3  364.96
  5255.6  366.99  5339.2  369.00  5448.2  373.54  5670.0  378.13  5783.6  381.62
#Mann=7,-1,0
  4191.2    0.05       0  4903.1     0.1       0  4999.6    0.07       0
  5005.6     0.1       0  5140.9    0.05       0  5255.6     0.1       0
  5339.2    0.05       0
Bank Sta=4999.6,5005.6
Exp/Cntr=0.3,0.1

Type RM Length L Ch R = 1,1686,549,549,549
BEGIN DESCRIPTION:
Mapping XS 522c0074
END DESCRIPTION:
XS GIS Cut Line= 4
      2292357.71     13435713.31      2292377.65     13435230.97
      2292022.88     13435047.60      2291701.36     13435083.33
#Sta/Elev= 30
  4401.2  366.34  4417.7  365.22  4467.7  365.29  4537.8  362.98  4557.8  363.78
  4577.8  363.44  4617.8  361.43  4657.9  361.02  4727.9  361.67  4768.8  360.39
  4883.5  359.03  4935.2  359.57  4974.3  359.28  4993.5  355.91  4996.2  355.41
  4999.5  355.91  5013.0  356.97  5035.2  356.37  5051.7  358.81  5073.8  359.70
  5079.4  358.99  5096.0  359.28  5101.6  358.53  5123.7  359.08  5199.1  362.60
  5273.1  364.71  5413.3  368.24  5439.4  368.07  5469.6  369.81  5606.8  372.83
#Mann=5,-1,0
  4401.2    0.05       0  4935.2     0.1       0  4993.5    0.07       0
  4999.5     0.1       0  5051.7    0.05       0
Bank Sta=4993.5,4999.5
Exp/Cntr=0.3,0.1

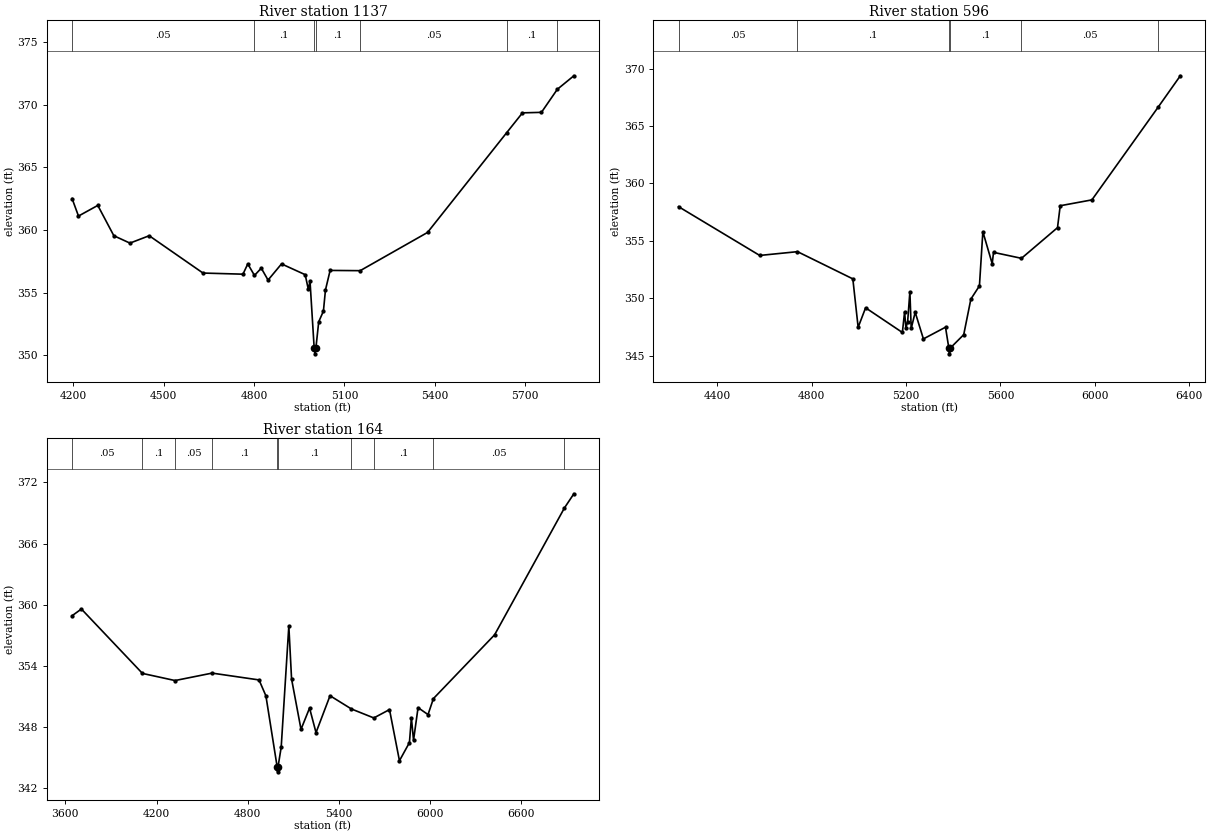
Type RM Length L Ch R = 1,1137,541,541,541
BEGIN DESCRIPTION:
Mapping XS eac079c8
END DESCRIPTION:
XS GIS Cut Line= 4
      2292479.29     13435626.84      2292632.05     13435217.15
      2292402.89     13434765.76      2291715.38     13434987.99
#Sta/Elev= 30
  4195.8  362.51  4217.1  361.11  4281.2  361.96  4334.5  359.54  4387.9  358.95
  4451.9  359.54  4630.5  356.56  4763.2  356.47  4779.2  357.29  4801.4  356.37
  4824.0  356.95  4846.5  356.00  4891.2  357.29  4969.8  356.43  4980.2  355.26
  4985.8  355.92  4999.5  350.61  5002.2  350.11  5005.5  350.61  5014.7  352.67
  5030.3  353.52  5037.1  355.21  5052.6  356.77  5152.4  356.75  5375.9  359.80
  5639.2  367.78  5691.2  369.35  5754.2  369.39  5806.9  371.23  5861.8  372.31
#Mann=7,-1,0
  4195.8    0.05       0  4801.4     0.1       0  4999.5    0.07       0
  5005.5     0.1       0  5152.4    0.05       0  5639.2     0.1       0
  5806.9    0.05       0
Bank Sta=4999.5,5005.5
Exp/Cntr=0.3,0.1

Type RM Length L Ch R = 1,596,432,432,432
BEGIN DESCRIPTION:
Mapping XS d526b776
END DESCRIPTION:
XS GIS Cut Line= 5
      2292688.56     13435422.32      2292947.67     13434820.39
      2292748.36     13434413.81      2292285.96     13434637.03
      2291847.48     13434888.16
#Sta/Elev= 30
  4235.7  357.98  4579.8  353.73  4739.9  354.06  4974.5  351.69  4997.0  347.47
  5028.6  349.17  5184.5  347.02  5193.9  348.82  5199.4  347.42  5206.8  347.96
  5216.3  350.57  5221.9  347.37  5238.8  348.78  5273.6  346.46  5367.3  347.48
  5381.4  345.66  5384.1  345.16  5387.4  345.66  5444.5  346.83  5474.8  349.93
  5511.1  351.08  5525.6  355.80  5565.2  353.01  5570.8  354.00  5689.3  353.48
  5842.0  356.15  5853.5  358.06  5987.8  358.57  6268.0  366.63  6362.6  369.38
#Mann=6,-1,0
  4235.7    0.05       0  4739.9     0.1       0  5381.4    0.07       0
  5387.4     0.1       0  5689.3    0.05       0  6268.0     0.1       0
Bank Sta=5381.4,5387.4
Exp/Cntr=0.3,0.1

Type RM Length L Ch R = 1,164,0,0,0
BEGIN DESCRIPTION:
UNT027 IN SUCR 1.0
END DESCRIPTION:
XS GIS Cut Line= 5
      2292760.53     13435685.89      2293296.98     13434894.24
      2293192.82     13434389.03      2292859.48     13434081.74
      2291729.30     13434864.71
#Sta/Elev= 30
  3644.2  358.92  3705.5  359.58  4107.1  353.26  4321.4  352.56  4565.1  353.29
  4873.9  352.62  4919.1  351.06  4993.0  344.10  4995.8  343.60  4999.0  344.10
  5019.7  346.02  5069.9  357.91  5087.9  352.71  5150.0  347.77  5206.2  349.86
  5248.7  347.45  5340.9  351.07  5481.5  349.77  5628.9  348.89  5732.0  349.71
  5797.5  344.69  5863.1  346.47  5876.0  348.90  5890.1  346.70  5919.8  349.90
  5985.4  349.22  6020.9  350.79  6423.4  357.05  6883.0  369.51  6944.6  370.89
#Mann=10,-1,0
  3644.2    0.05       0  4107.1     0.1       0  4321.4    0.05       0
  4565.1     0.1       0  4993.0    0.07       0  4999.0     0.1       0
  5481.5    0.05       0  5628.9     0.1       0  6020.9    0.05       0
  6883.0     0.1       0
Bank Sta=4993,4999
Exp/Cntr=0.3,0.1

Chan Stop Cuts=-1