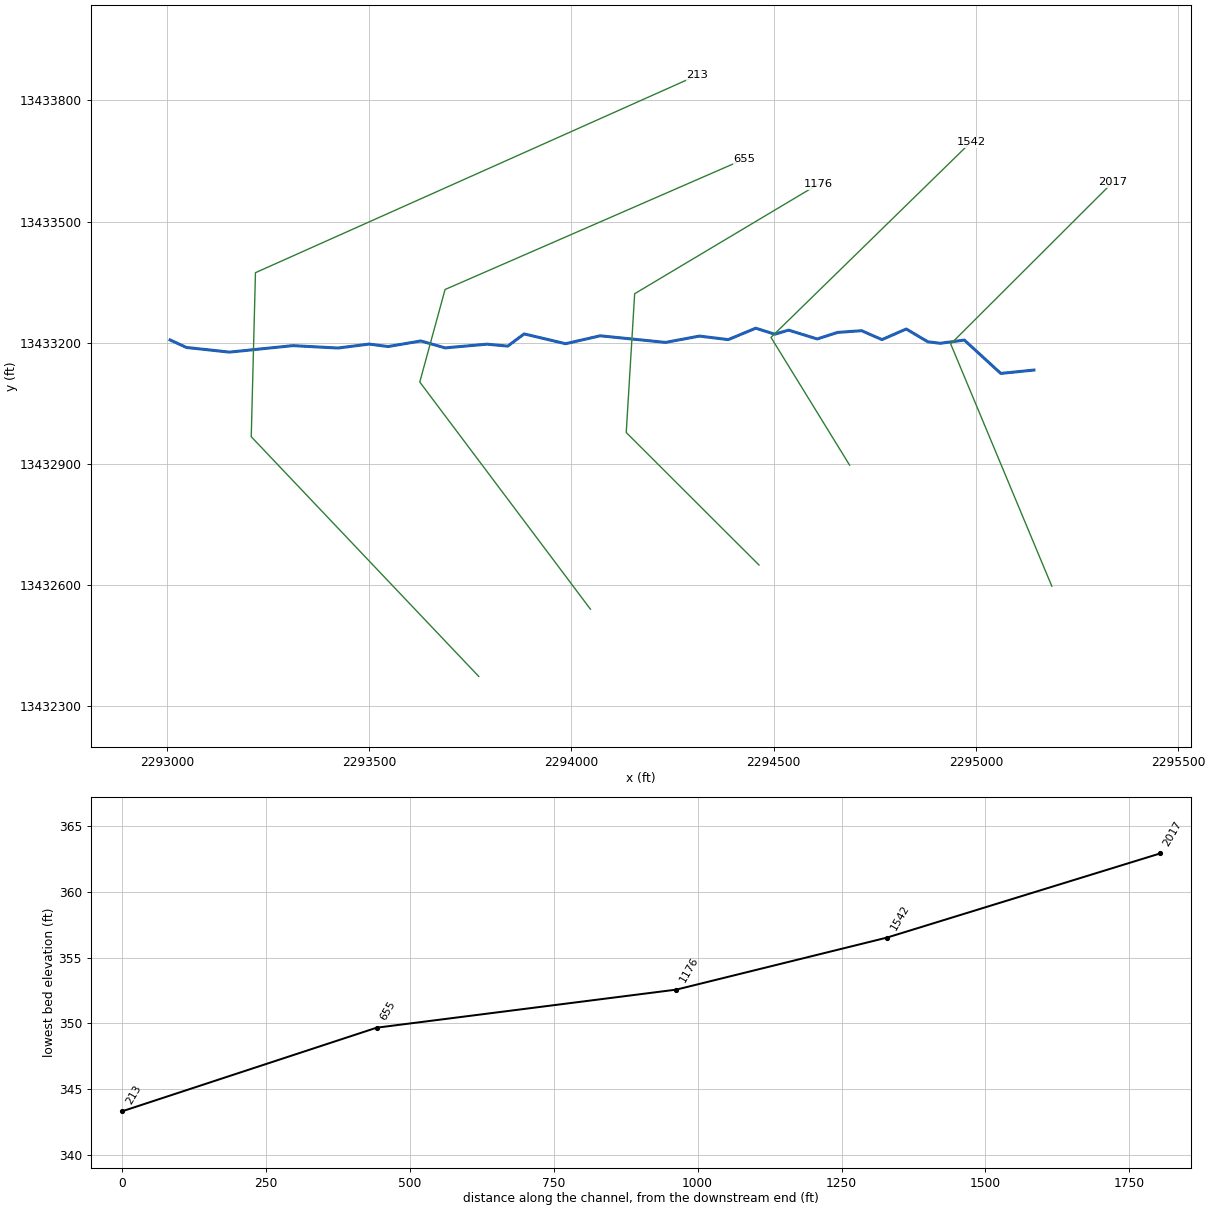
--- UNT028 IN SUCR.prj (project) ---

Proj Title=UNT028 IN SUCR Base Level Engineering
Current Plan=p01
Default Exp/Contr=0.3,0.1
English Units
Geom File=g01
Flow File=f01
Plan File=p01
BEGIN DESCRIPTION:
UNT028 IN SUCR
END DESCRIPTION:

--- UNT028 IN SUCR.p01 (plan) ---

Plan Title=Multiple Run
Short Identifier=Multiple
Geom File=g01
Flow File=f01
Subcritical Flow
K Sum by GR= 0
Std Step Tol= 0.01
Critical Tol= 0.01
Num of Std Step Trials= 20
Max Error Tol= 0.3
Flow Tol Ratio= 0.001
Split Flow NTrial= 30
Split Flow Tol= 0.02
Split Flow Ratio= 0.02
Log Output Level= 0
Friction Slope Method= 1
Unsteady Friction Slope Method= 2
Unsteady Bridges Friction Slope Method= 1
Parabolic Critical Depth
Global Vel Dist=  1 , 1 , 1
Global Log Level= 0
CheckData=True
Encroach Param= -1, 0, 0, 0
BEGIN DESCRIPTION:
Multiple Run
END DESCRIPTION:

--- UNT028 IN SUCR.f01 (steady flow) ---

Flow Title=Multiple
Number of Profiles=7
Profile Names=10-year,25-year,50-year,1pct_min,100-year,1pct_plu,500-year
River Rch & RM= UNT028 IN SUCR,Reach-1,2017
     178     232     274     237     321     434     440
Boundary for River Rch & Prof#=UNT028 IN SUCR,Reach-1,1
Up Type=0
Dn Type=3
Dn Slope=0.005
Boundary for River Rch & Prof#=UNT028 IN SUCR,Reach-1,2
Up Type=0
Dn Type=3
Dn Slope=0.005
Boundary for River Rch & Prof#=UNT028 IN SUCR,Reach-1,3
Up Type=0
Dn Type=3
Dn Slope=0.005
Boundary for River Rch & Prof#=UNT028 IN SUCR,Reach-1,4
Up Type=0
Dn Type=3
Dn Slope=0.005
Boundary for River Rch & Prof#=UNT028 IN SUCR,Reach-1,5
Up Type=0
Dn Type=3
Dn Slope=0.005
Boundary for River Rch & Prof#=UNT028 IN SUCR,Reach-1,6
Up Type=0
Dn Type=3
Dn Slope=0.005
Boundary for River Rch & Prof#=UNT028 IN SUCR,Reach-1,7
Up Type=0
Dn Type=3
Dn Slope=0.005

--- UNT028 IN SUCR.g01 (geometry) ---

Geom Title=Existing Conditions

River Reach=UNT028 IN SUCR,Reach-1
Reach XY= 30
      2295143.46     13433132.24      2295061.51     13433123.90
      2294971.41     13433206.49      2294911.90     13433198.54
      2294881.19     13433202.26      2294827.83     13433233.94
      2294767.73     13433207.68      2294717.32     13433229.76
      2294658.35     13433225.54      2294607.60     13433209.27
      2294536.92     13433231.14      2294502.77     13433221.01
      2294455.72     13433235.96      2294387.79     13433207.67
      2294316.43     13433216.40      2294232.75     13433200.76
      2294071.03     13433217.09      2293985.52     13433197.52
      2293883.14     13433221.77      2293842.62     13433191.56
      2293791.11     13433196.34      2293687.85     13433187.16
      2293627.60     13433204.33      2293546.62     13433190.46
      2293500.12     13433196.63      2293422.73     13433186.80
      2293311.29     13433192.76      2293154.73     13433176.68
      2293048.22     13433188.18      2293007.72     13433206.85

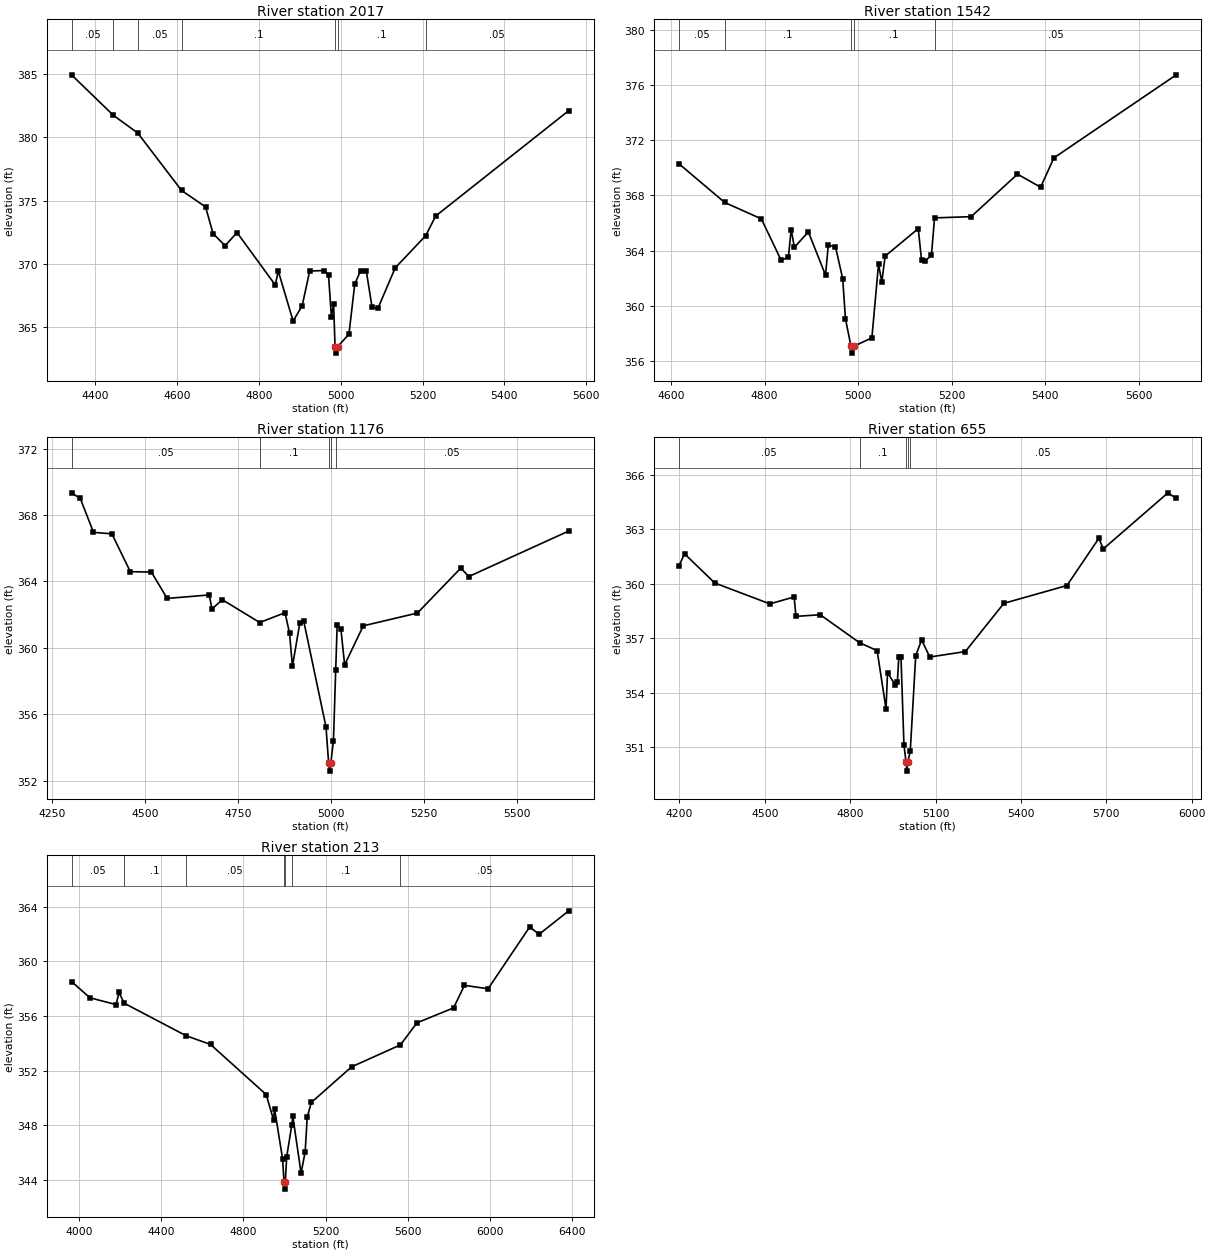
Type RM Length L Ch R = 1,2017,475,475,475
BEGIN DESCRIPTION:
UNT028 IN SUCR 3.0
END DESCRIPTION:
XS GIS Cut Line= 3
      2295187.72     13432596.87      2294937.72     13433196.85
      2295337.74     13433596.88
#Sta/Elev= 30
  4341.6  384.95  4443.9  381.75  4503.5  380.35  4610.6  375.81  4669.3  374.51
  4687.7  372.40  4717.0  371.44  4746.2  372.48  4839.9  368.33  4847.0  369.45
  4883.3  365.49  4905.5  366.69  4923.9  369.44  4959.1  369.48  4969.9  369.12
  4977.0  365.82  4982.4  366.83  4985.9  363.45  4988.6  362.95  4991.9  363.45
  5019.9  364.45  5034.0  368.40  5048.2  369.46  5062.3  369.45  5076.4  366.57
  5090.6  366.48  5133.0  369.69  5207.4  372.23  5232.0  373.79  5557.3  382.12
#Mann=7,-1,0
  4341.6    0.05       0  4443.9     0.1       0  4503.5    0.05       0
  4610.6     0.1       0  4985.9    0.07       0  4991.9     0.1       0
  5207.4    0.05       0
Bank Sta=4985.9,4991.9
Exp/Cntr=0.3,0.1

Type RM Length L Ch R = 1,1542,366,366,366
BEGIN DESCRIPTION:
UNT028 IN SUCR 2.0
END DESCRIPTION:
XS GIS Cut Line= 3
      2294687.73     13432896.84      2294493.42     13433213.13
      2294987.70     13433696.84
#Sta/Elev= 30
  4617.2  370.30  4714.8  367.49  4793.1  366.30  4835.6  363.28  4851.0  363.53
  4856.9  365.52  4863.7  364.23  4893.6  365.35  4930.3  362.21  4936.2  364.39
  4951.6  364.27  4967.0  361.95  4972.9  359.04  4984.7  357.04  4987.4  356.54
  4990.7  357.04  5029.4  357.65  5043.6  363.01  5050.6  361.70  5057.7  363.59
  5128.5  365.59  5135.5  363.30  5142.6  363.22  5156.7  363.65  5163.3  366.37
  5241.6  366.46  5340.6  369.55  5390.1  368.60  5418.3  370.73  5680.0  376.77
#Mann=5,-1,0
  4617.2    0.05       0  4714.8     0.1       0  4984.7    0.07       0
  4990.7     0.1       0  5163.3    0.05       0
Bank Sta=4984.7,4990.7
Exp/Cntr=0.3,0.1

Type RM Length L Ch R = 1,1176,521,521,521
BEGIN DESCRIPTION:
Mapping XS ec6f3547
END DESCRIPTION:
XS GIS Cut Line= 4
      2294463.68     13432649.42      2294135.53     13432977.57
      2294156.36     13433321.32      2294609.27     13433592.02
#Sta/Elev= 30
  4303.2  369.34  4326.8  369.00  4362.2  366.96  4411.7  366.87  4461.2  364.59
  4517.7  364.57  4560.2  362.98  4673.3  363.19  4680.4  362.35  4708.6  362.90
  4808.9  361.53  4876.8  362.12  4889.0  360.89  4896.8  358.89  4916.8  361.52
  4926.9  361.64  4987.0  355.24  4994.0  353.08  4996.7  352.58  5000.0  353.08
  5007.0  354.41  5013.1  358.68  5017.0  361.41  5027.0  361.14  5037.1  358.98
  5087.1  361.33  5232.6  362.10  5349.3  364.81  5370.7  364.30  5639.3  367.04
#Mann=5,-1,0
  4303.2    0.05       0  4808.9     0.1       0  4994.0    0.07       0
  5000.0     0.1       0  5013.1    0.05       0
Bank Sta=4994,5000
Exp/Cntr=0.3,0.1

Type RM Length L Ch R = 1,655,442,442,442
BEGIN DESCRIPTION:
Mapping XS bd0f67a7
END DESCRIPTION:
XS GIS Cut Line= 4
      2294046.96     13432540.10      2293625.11     13433102.57
      2293687.61     13433331.74      2294427.17     13433654.64
#Sta/Elev= 30
  4198.4  361.00  4217.6  361.66  4323.9  360.05  4517.6  358.90  4603.0  359.28
  4609.3  358.21  4694.7  358.30  4832.7  356.76  4894.7  356.32  4925.9  353.11
  4931.1  355.11  4957.8  354.44  4965.7  354.59  4970.9  355.97  4978.5  355.95
  4988.8  351.14  4996.2  350.18  4999.0  349.68  5002.2  350.18  5011.0  350.77
  5030.3  356.05  5051.0  356.91  5079.7  355.97  5204.6  356.27  5340.1  358.93
  5561.7  359.91  5673.8  362.51  5689.7  361.93  5916.7  365.02  5946.0  364.71
#Mann=5,-1,0
  4198.4    0.05       0  4832.7     0.1       0  4996.2    0.07       0
  5002.2     0.1       0  5011.0    0.05       0
Bank Sta=4996.2,5002.2
Exp/Cntr=0.3,0.1

Type RM Length L Ch R = 1,213,0,0,0
BEGIN DESCRIPTION:
UNT028 IN SUCR 1.0
END DESCRIPTION:
XS GIS Cut Line= 4
      2293770.96     13432373.39      2293208.44     13432967.15
      2293218.86     13433373.40      2294311.31     13433862.40
#Sta/Elev= 30
  3963.1  358.53  4052.6  357.34  4180.0  356.84  4194.2  357.73  4219.6  356.94
  4520.8  354.56  4639.9  353.92  4910.8  350.25  4946.8  348.40  4951.8  349.19
  4990.8  345.54  4997.8  343.82  5000.5  343.32  5003.8  343.82  5010.8  345.68
  5035.9  348.05  5040.8  348.65  5080.8  344.49  5100.8  346.06  5110.8  348.59
  5130.8  349.67  5326.8  352.28  5564.9  353.89  5644.7  355.50  5823.5  356.60
  5876.4  358.25  5991.4  358.00  6194.1  362.53  6239.8  361.99  6384.3  363.71
#Mann=7,-1,0
  3963.1    0.05       0  4219.6     0.1       0  4520.8    0.05       0
  4997.8    0.03       0  5003.8    0.05       0  5035.9     0.1       0
  5564.9    0.05       0
Bank Sta=4997.8,5003.8
Exp/Cntr=0.3,0.1

Chan Stop Cuts=-1