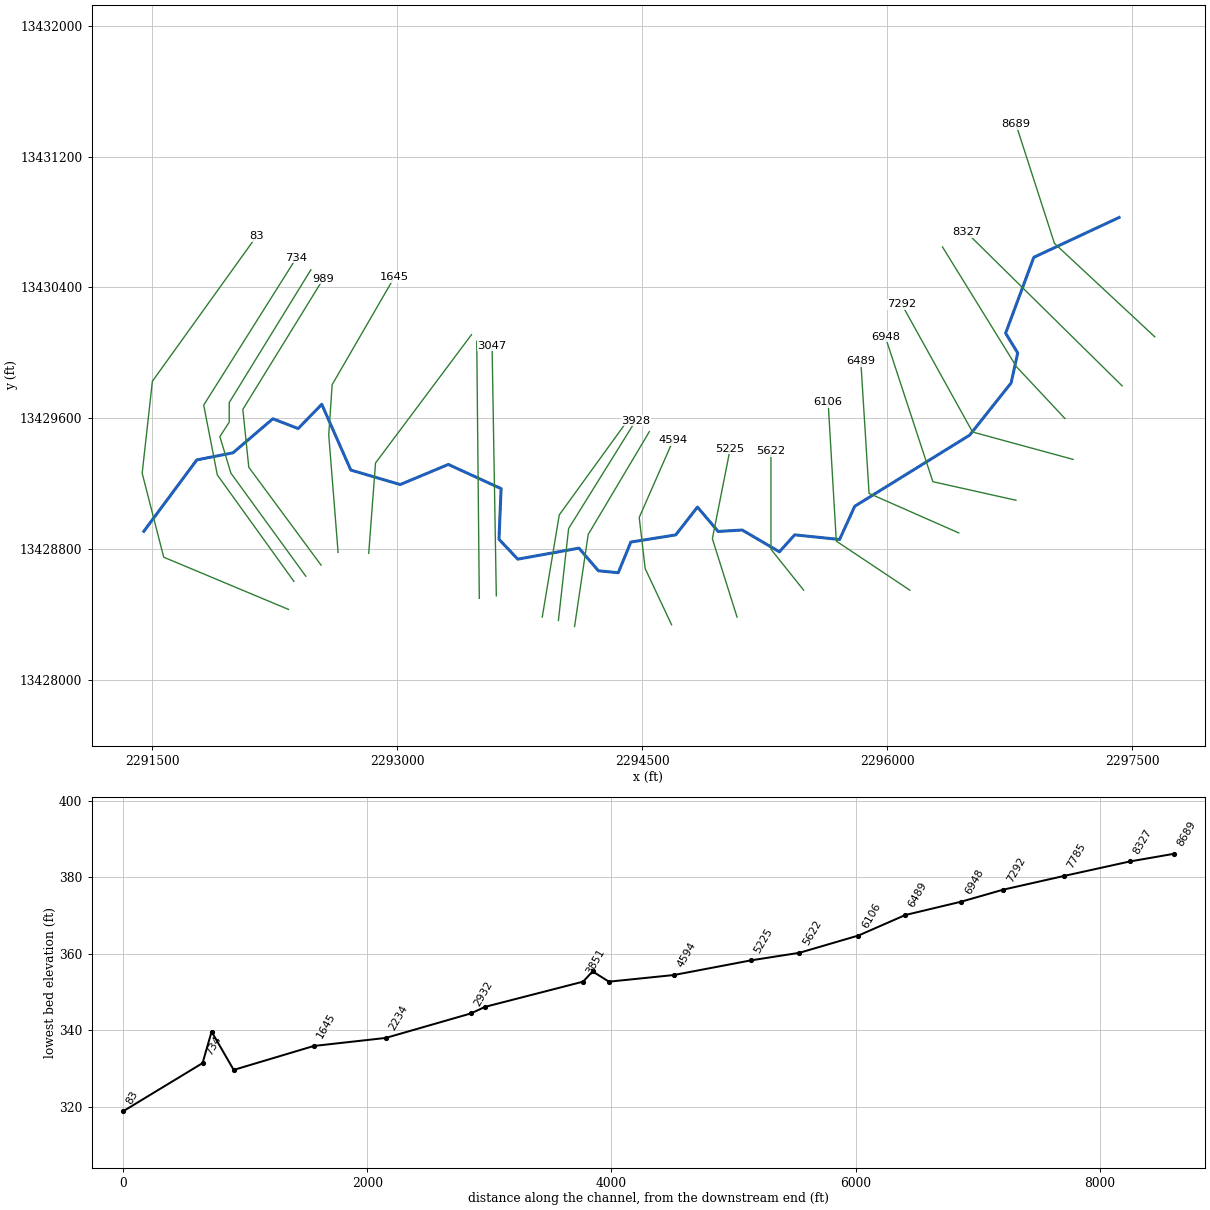
--- UNT029 IN SUCR.prj (project) ---

Proj Title=UNT029 IN SUCR Base Level Engineering
Current Plan=p01
Default Exp/Contr=0.3,0.1
English Units
Geom File=g01
Flow File=f01
Plan File=p01
BEGIN DESCRIPTION:
UNT029 IN SUCR
END DESCRIPTION:

--- UNT029 IN SUCR.p01 (plan) ---

Plan Title=Multiple Run
Short Identifier=Multiple
Geom File=g01
Flow File=f01
Subcritical Flow
K Sum by GR= 0
Std Step Tol= 0.01
Critical Tol= 0.01
Num of Std Step Trials= 20
Max Error Tol= 0.3
Flow Tol Ratio= 0.001
Split Flow NTrial= 30
Split Flow Tol= 0.02
Split Flow Ratio= 0.02
Log Output Level= 0
Friction Slope Method= 1
Unsteady Friction Slope Method= 2
Unsteady Bridges Friction Slope Method= 1
Parabolic Critical Depth
Global Vel Dist=  1 , 1 , 1
Global Log Level= 0
CheckData=True
Encroach Param= -1, 0, 0, 0
BEGIN DESCRIPTION:
Multiple Run
END DESCRIPTION:

--- UNT029 IN SUCR.f01 (steady flow) ---

Flow Title=Multiple
Number of Profiles=7
Profile Names=10-year,25-year,50-year,1pct_min,100-year,1pct_plu,500-year
River Rch & RM= UNT029 IN SUCR,Reach-1,8689
     646     918    1147    1048    1417    1916    2169
River Rch & RM= UNT029 IN SUCR,Reach-1,2932
     846    1221    1542    1421    1922    2600    3001
Boundary for River Rch & Prof#=UNT029 IN SUCR,Reach-1,1
Up Type=0
Dn Type=3
Dn Slope=0.005
Boundary for River Rch & Prof#=UNT029 IN SUCR,Reach-1,2
Up Type=0
Dn Type=3
Dn Slope=0.005
Boundary for River Rch & Prof#=UNT029 IN SUCR,Reach-1,3
Up Type=0
Dn Type=3
Dn Slope=0.005
Boundary for River Rch & Prof#=UNT029 IN SUCR,Reach-1,4
Up Type=0
Dn Type=3
Dn Slope=0.005
Boundary for River Rch & Prof#=UNT029 IN SUCR,Reach-1,5
Up Type=0
Dn Type=3
Dn Slope=0.005
Boundary for River Rch & Prof#=UNT029 IN SUCR,Reach-1,6
Up Type=0
Dn Type=3
Dn Slope=0.005
Boundary for River Rch & Prof#=UNT029 IN SUCR,Reach-1,7
Up Type=0
Dn Type=3
Dn Slope=0.005

--- UNT029 IN SUCR.g01 (geometry) ---

Geom Title=Existing Conditions

River Reach=UNT029 IN SUCR,Reach-1
Reach XY= 30
      2297419.50     13430827.11      2296897.06     13430583.22
      2296724.40     13430119.03      2296798.38     13429998.07
      2296758.01     13429814.47      2296504.04     13429495.04
      2295800.58     13429060.06      2295707.72     13428856.86
      2295432.82     13428885.25      2295339.25     13428781.44
      2295111.73     13428914.71      2294964.31     13428906.06
      2294837.60     13429055.12      2294704.47     13428884.72
      2294429.72     13428841.12      2294352.68     13428653.41
      2294231.15     13428665.34      2294112.11     13428803.84
      2293737.33     13428736.57      2293622.31     13428858.09
      2293635.29     13429167.88      2293312.20     13429315.97
      2293017.68     13429192.94      2292714.99     13429281.57
      2292537.23     13429684.00      2292392.70     13429535.57
      2292237.75     13429595.46      2291993.95     13429387.28
      2291771.96     13429343.55      2291447.72     13428906.85

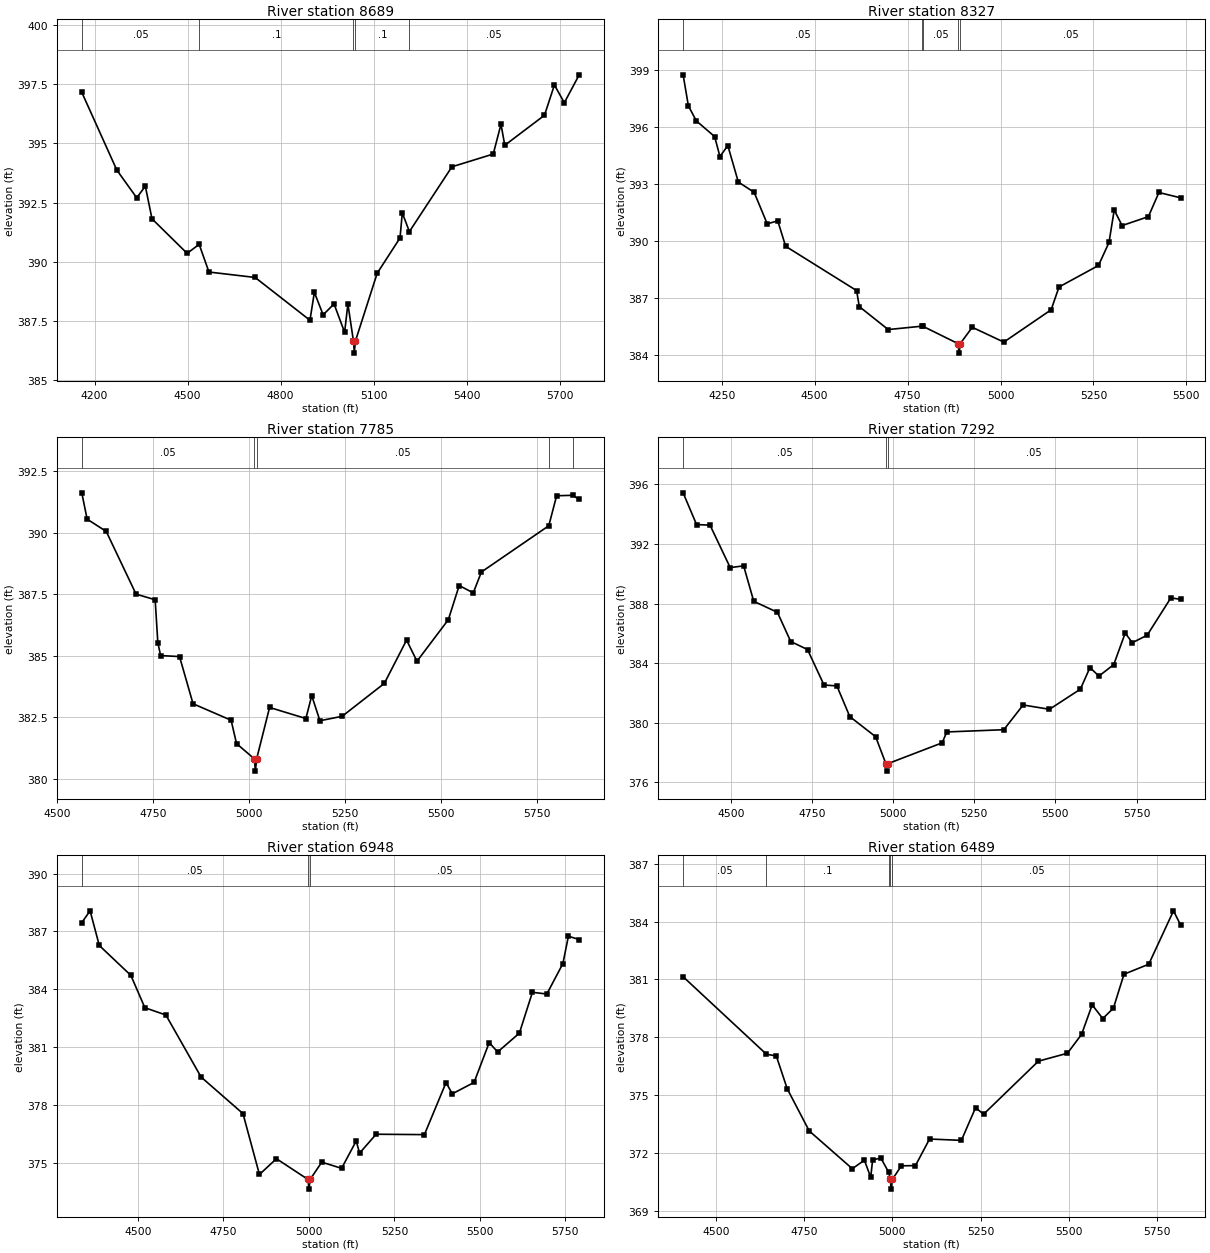
Type RM Length L Ch R = 1,8689,362,362,362
BEGIN DESCRIPTION:
UNT029 IN SUCR 16.0
END DESCRIPTION:
XS GIS Cut Line= 3
      2297637.75     13430096.83      2297023.28     13430668.79
      2296787.72     13431396.86
#Sta/Elev= 30
  4158.6  397.16  4271.7  393.87  4335.8  392.70  4363.6  393.19  4385.1  391.81
  4498.4  390.35  4537.3  390.73  4568.8  389.56  4717.8  389.33  4894.7  387.52
  4908.9  388.70  4937.2  387.75  4972.4  388.21  5006.5  387.01  5017.1  388.21
  5035.1  386.63  5037.8  386.13  5041.1  386.63  5111.6  389.51  5185.2  391.00
  5192.6  392.06  5215.5  391.27  5352.7  394.01  5486.0  394.55  5511.0  395.81
  5523.2  394.92  5651.3  396.19  5683.3  397.47  5715.3  396.72  5763.3  397.90
#Mann=5,-1,0
  4158.6    0.05       0  4537.3     0.1       0  5035.1    0.07       0
  5041.1     0.1       0  5215.5    0.05       0
Bank Sta=5035.1,5041.1
Exp/Cntr=0.3,0.1

Type RM Length L Ch R = 1,8327,542,542,542
BEGIN DESCRIPTION:
UNT029 IN SUCR 15.0
END DESCRIPTION:
XS GIS Cut Line= 2
      2297437.73     13429796.84      2296484.55     13430735.97
#Sta/Elev= 30
  4146.2  398.76  4160.3  397.13  4181.6  396.34  4231.0  395.51  4245.2  394.46
  4266.4  395.04  4294.7  393.12  4337.2  392.58  4372.5  390.92  4400.7  391.08
  4422.0  389.74  4612.9  387.41  4620.0  386.57  4697.8  385.36  4790.1  385.54
  4790.4  385.54  4885.7  384.62  4888.5  384.12  4891.7  384.62  4924.0  385.48
  5008.9  384.70  5136.2  386.40  5157.4  387.60  5263.5  388.73  5291.8  389.94
  5305.9  391.65  5327.1  390.83  5397.8  391.30  5426.1  392.57  5484.3  392.29
#Mann=5,-1,0
  4146.2    0.05       0  4790.1     0.1       0  4790.4    0.05       0
  4885.7    0.03       0  4891.7    0.05       0
Bank Sta=4885.7,4891.7
Exp/Cntr=0.3,0.1

Type RM Length L Ch R = 1,7785,493,493,493
BEGIN DESCRIPTION:
UNT029 IN SUCR 14.0
END DESCRIPTION:
XS GIS Cut Line= 3
      2297087.72     13429596.85      2296791.08     13429913.58
      2296337.70     13430646.89
#Sta/Elev= 30
  4563.5  391.63  4577.4  390.56  4627.2  390.06  4704.9  387.51  4754.7  387.28
  4761.6  385.54  4768.9  385.01  4818.2  384.97  4853.4  383.05  4952.6  382.38
  4966.7  381.43  5013.1  380.81  5015.9  380.31  5019.1  380.81  5052.8  382.90
  5147.4  382.45  5162.7  383.38  5184.0  382.36  5241.9  382.54  5351.9  383.88
  5409.8  385.64  5436.9  384.78  5518.6  386.47  5546.9  387.86  5583.5  387.56
  5604.8  388.41  5780.3  390.29  5800.8  391.51  5842.3  391.53  5859.6  391.36
#Mann=5,-1,0
  4563.5    0.05       0  5013.1    0.03       0  5019.1    0.05       0
  5780.3     0.1       0  5842.3    0.05       0
Bank Sta=5013.1,5019.1
Exp/Cntr=0.3,0.1

Type RM Length L Ch R = 1,7292,344,344,344
BEGIN DESCRIPTION:
UNT029 IN SUCR 13.0
END DESCRIPTION:
XS GIS Cut Line= 3
      2297137.71     13429346.86      2296521.98     13429514.28
      2296087.71     13430296.88
#Sta/Elev= 30
  4352.6  395.44  4394.0  393.31  4435.5  393.27  4497.7  390.42  4539.1  390.54
  4570.2  388.16  4643.2  387.42  4684.2  385.46  4736.0  384.92  4786.8  382.54
  4826.5  382.48  4866.3  380.42  4945.9  379.07  4977.5  377.26  4980.2  376.76
  4983.5  377.26  5151.0  378.66  5165.2  379.39  5341.0  379.54  5400.5  381.20
  5481.7  380.91  5576.9  382.26  5606.5  383.71  5634.1  383.14  5679.8  383.91
  5715.2  386.03  5737.0  385.38  5782.7  385.88  5855.9  388.39  5885.7  388.29
#Mann=3,-1,0
  4352.6    0.05       0  4977.5   0.035       0  4983.5    0.05       0
Bank Sta=4977.5,4983.5
Exp/Cntr=0.3,0.1

Type RM Length L Ch R = 1,6948,459,459,459
BEGIN DESCRIPTION:
UNT029 IN SUCR 12.0
END DESCRIPTION:
XS GIS Cut Line= 3
      2296787.72     13429096.86      2296278.93     13429210.46
      2295987.73     13430096.83
#Sta/Elev= 30
  4336.0  387.46  4360.3  388.07  4387.2  386.27  4479.4  384.72  4520.4  383.04
  4581.9  382.66  4684.8  379.44  4807.3  377.54  4855.4  374.38  4905.1  375.20
  4997.5  374.12  5000.2  373.62  5003.5  374.12  5037.6  375.02  5095.6  374.70
  5138.3  376.12  5148.2  375.49  5196.6  376.47  5337.7  376.45  5400.9  379.15
  5419.3  378.57  5482.9  379.16  5527.2  381.23  5551.8  380.74  5615.4  381.72
  5653.5  383.84  5695.6  383.75  5742.6  385.33  5758.7  386.75  5790.3  386.58
#Mann=3,-1,0
  4336.0    0.05       0  4997.5   0.035       0  5003.5    0.05       0
Bank Sta=4997.5,5003.5
Exp/Cntr=0.3,0.1

Type RM Length L Ch R = 1,6489,383,383,383
BEGIN DESCRIPTION:
UNT029 IN SUCR 11.0
END DESCRIPTION:
XS GIS Cut Line= 3
      2296437.71     13428896.86      2295888.30     13429138.84
      2295837.72     13429946.82
#Sta/Elev= 30
  4406.9  381.14  4642.9  377.12  4671.0  377.03  4701.9  375.33  4764.3  373.14
  4886.4  371.18  4920.7  371.62  4938.6  370.73  4944.0  371.64  4967.4  371.73
  4989.7  370.99  4994.0  370.62  4996.7  370.12  5000.0  370.62  5025.3  371.33
  5065.4  371.34  5105.4  372.72  5195.6  372.65  5235.7  374.34  5258.7  374.01
  5413.9  376.76  5496.2  377.17  5536.3  378.15  5566.3  379.68  5596.4  378.97
  5626.5  379.51  5656.5  381.27  5726.7  381.79  5796.8  384.56  5816.8  383.83
#Mann=5,-1,0
  4406.9    0.05       0  4642.9     0.1       0  4989.7    0.05       0
  4994.0   0.035       0  5000.0    0.05       0
Bank Sta=4994,5000
Exp/Cntr=0.3,0.1

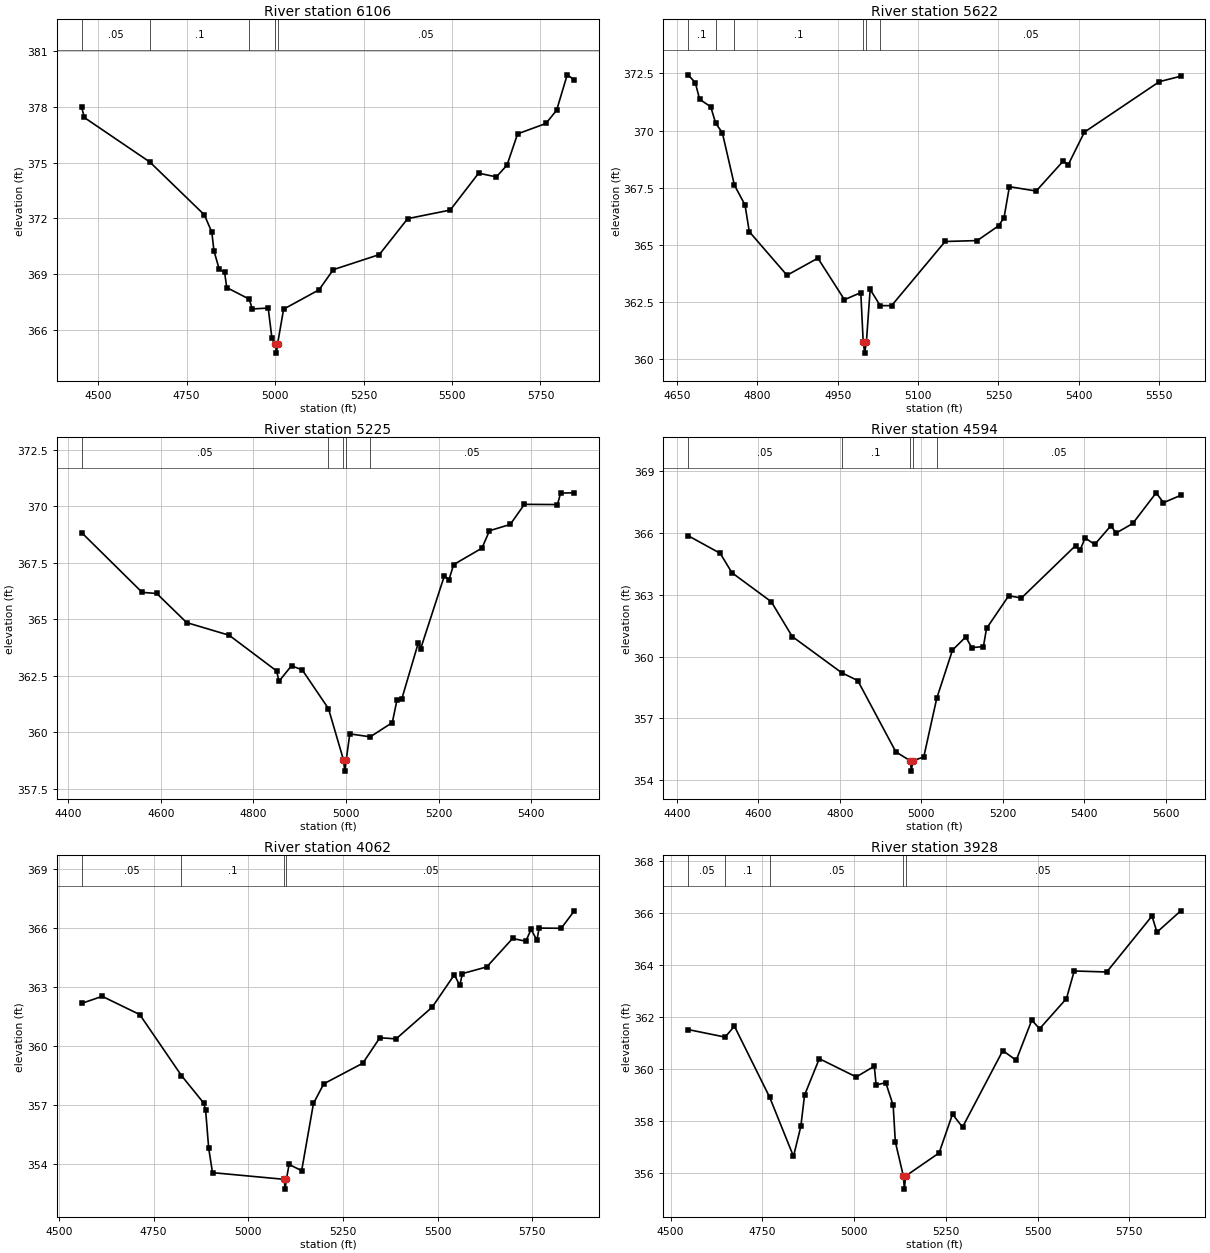
Type RM Length L Ch R = 1,6106,484,484,484
BEGIN DESCRIPTION:
UNT029 IN SUCR 10.0
END DESCRIPTION:
XS GIS Cut Line= 3
      2296137.75     13428546.83      2295687.72     13428846.85
      2295637.72     13429696.81
#Sta/Elev= 30
  4453.3  378.00  4460.9  377.42  4646.2  375.03  4800.4  372.19  4821.4  371.26
  4827.4  370.26  4842.4  369.27  4857.5  369.10  4863.5  368.29  4927.0  367.67
  4935.6  367.14  4980.7  367.19  4991.2  365.57  5001.2  365.27  5003.9  364.77
  5007.2  365.27  5024.2  367.13  5124.4  368.17  5164.5  369.25  5294.7  370.06
  5374.8  371.99  5495.0  372.45  5575.2  374.43  5625.3  374.23  5655.3  374.86
  5685.4  376.54  5765.5  377.10  5795.6  377.81  5825.6  379.71  5845.6  379.44
#Mann=5,-1,0
  4453.3    0.05       0  4646.2     0.1       0  4927.0    0.05       0
  5001.2    0.03       0  5007.2    0.05       0
Bank Sta=5001.2,5007.2
Exp/Cntr=0.3,0.1

Type RM Length L Ch R = 1,5622,397,397,397
BEGIN DESCRIPTION:
UNT029 IN SUCR 9.0
END DESCRIPTION:
XS GIS Cut Line= 3
      2295487.69     13428546.89      2295287.72     13428796.85
      2295287.72     13429396.85
#Sta/Elev= 30
  4670.4  372.44  4684.0  372.10  4692.0  371.37  4712.8  371.04  4722.2  370.31
  4734.4  369.91  4757.0  367.61  4776.8  366.74  4784.8  365.57  4855.2  363.66
  4912.9  364.41  4962.5  362.59  4993.0  362.90  4997.5  360.75  5000.3  360.25
  5003.5  360.75  5010.5  363.04  5029.3  362.33  5050.5  362.33  5150.5  365.14
  5210.5  365.18  5250.5  365.83  5260.5  366.19  5270.5  367.54  5320.5  367.35
  5370.5  368.65  5380.5  368.51  5410.5  369.93  5550.5  372.14  5590.5  372.38
#Mann=6,-1,0
  4670.4     0.1       0  4722.2    0.05       0  4757.0     0.1       0
  4997.5    0.07       0  5003.5     0.1       0  5029.3    0.05       0
Bank Sta=4997.5,5003.5
Exp/Cntr=0.3,0.1

Type RM Length L Ch R = 1,5225,631,631,631
BEGIN DESCRIPTION:
Mapping XS 9ec4481f
END DESCRIPTION:
XS GIS Cut Line= 3
      2295079.98     13428382.04      2294928.93     13428861.25
      2295038.15     13429412.58
#Sta/Elev= 30
  4428.8  368.84  4559.7  366.19  4591.2  366.14  4655.9  364.85  4747.7  364.29
  4850.1  362.71  4855.3  362.25  4882.4  362.94  4905.7  362.75  4962.2  361.04
  4994.6  358.77  4997.4  358.27  5000.6  358.77  5008.3  359.92  5052.4  359.79
  5100.1  360.42  5110.3  361.43  5120.5  361.46  5156.4  363.96  5161.5  363.70
  5212.7  366.93  5222.4  366.74  5232.6  367.42  5293.8  368.15  5310.0  368.92
  5354.9  369.20  5385.5  370.09  5456.9  370.08  5463.7  370.59  5493.3  370.60
#Mann=5,-1,0
  4428.8    0.05       0  4962.2     0.1       0  4994.6    0.07       0
  5000.6     0.1       0  5052.4    0.05       0
Bank Sta=4994.6,5000.6
Exp/Cntr=0.3,0.1

Type RM Length L Ch R = 1,4594,532,532,532
BEGIN DESCRIPTION:
UNT029 IN SUCR 8.0
END DESCRIPTION:
XS GIS Cut Line= 4
      2294678.92     13428335.22      2294517.47     13428678.96
      2294481.01     13428991.46      2294688.58     13429463.67
#Sta/Elev= 30
  4427.3  365.88  4506.4  365.02  4535.0  364.08  4631.8  362.67  4683.2  360.98
  4804.7  359.22  4844.1  358.84  4937.6  355.38  4973.1  354.94  4975.9  354.44
  4979.1  354.94  5006.3  355.13  5038.2  357.98  5076.8  360.32  5109.5  360.96
  5124.0  360.44  5152.8  360.49  5160.4  361.37  5215.0  362.96  5246.2  362.85
  5379.4  365.40  5389.7  365.16  5402.7  365.77  5426.1  365.45  5466.2  366.37
  5478.2  366.00  5519.5  366.47  5577.1  367.96  5595.0  367.48  5637.5  367.84
#Mann=5,-1,0
  4427.3    0.05       0  4804.7     0.1       0  4973.1    0.07       0
  4979.1     0.1       0  5038.2    0.05       0
Bank Sta=4973.1,4979.1
Exp/Cntr=0.3,0.1

Type RM Length L Ch R = 1,4062,134,134,134
BEGIN DESCRIPTION:
UNT029 IN SUCR 7.0
END DESCRIPTION:
XS GIS Cut Line= 3
      2294085.18     13428324.80      2294168.51     13428887.29
      2294543.12     13429516.83
#Sta/Elev= 30
  4559.8  362.17  4614.4  362.53  4713.5  361.60  4823.6  358.49  4882.3  357.09
  4887.3  356.75  4895.5  354.79  4905.6  353.54  5094.7  353.20  5097.4  352.70
  5100.7  353.20  5107.8  353.96  5141.0  353.64  5172.2  357.07  5199.4  358.07
  5302.5  359.12  5347.5  360.42  5390.3  360.36  5485.8  361.98  5544.2  363.63
  5558.5  363.09  5565.6  363.69  5629.8  364.03  5698.0  365.48  5733.0  365.34
  5746.7  365.94  5762.3  365.40  5768.1  366.01  5826.5  366.00  5861.0  366.89
#Mann=4,-1,0
  4559.8    0.05       0  4823.6     0.1       0  5094.7    0.07       0
  5100.7    0.05       0
Bank Sta=5094.7,5100.7
Exp/Cntr=0.3,0.1

Type RM Length L Ch R = 1,3928,77,77,77
BEGIN DESCRIPTION:
Mapping XS 8cf41c8d
END DESCRIPTION:
XS GIS Cut Line= 3
      2293986.22     13428361.22      2294048.72     13428923.75
      2294459.13     13429583.53
#Sta/Elev= 30
  4547.5  361.52  4648.6  361.23  4673.9  361.65  4770.0  358.92  4834.9  356.65
  4855.0  357.80  4865.1  359.00  4905.3  360.40  5005.9  359.70  5055.2  360.11
  5060.2  359.39  5086.4  359.48  5106.6  358.61  5112.5  357.21  5134.4  355.89
  5137.2  355.39  5140.4  355.89  5231.8  356.78  5268.4  358.27  5295.6  357.77
  5405.4  360.71  5442.0  360.34  5484.4  361.88  5505.8  361.55  5578.9  362.71
  5600.1  363.77  5688.7  363.73  5812.0  365.88  5825.6  365.26  5890.5  366.08
#Mann=5,-1,0
  4547.5    0.05       0  4648.6     0.1       0  4770.0    0.05       0
  5134.4    0.03       0  5140.4    0.05       0
Bank Sta=5134.4,5140.4
Exp/Cntr=0.3,0.1

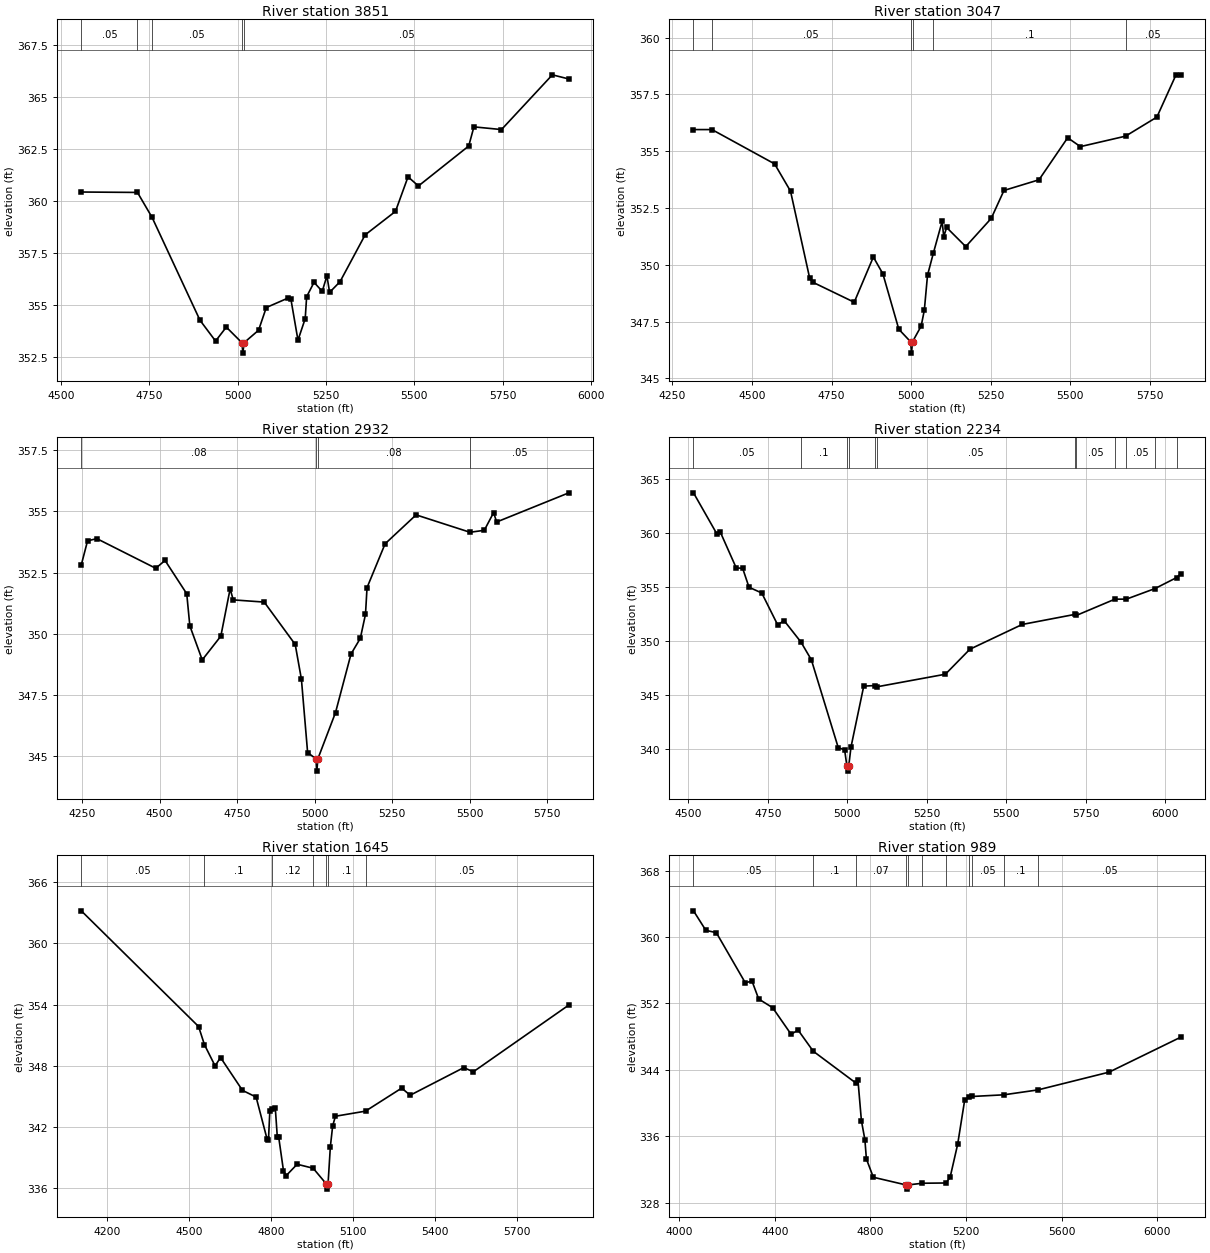
Type RM Length L Ch R = 1,3851,804,804,804
BEGIN DESCRIPTION:
UNT029 IN SUCR 6.0
END DESCRIPTION:
XS GIS Cut Line= 3
      2293887.27     13428382.12      2293991.43     13429007.08
      2294428.91     13429611.23
#Sta/Elev= 30
  4558.0  360.45  4716.9  360.43  4758.3  359.23  4893.8  354.29  4937.9  353.29
  4968.3  353.96  5012.5  353.21  5015.2  352.71  5018.5  353.21  5059.6  353.81
  5081.4  354.90  5142.2  355.35  5150.8  355.33  5171.1  353.33  5191.6  354.37
  5195.6  355.42  5216.5  356.11  5239.7  355.68  5253.0  356.42  5260.6  355.63
  5290.0  356.14  5361.1  358.39  5447.0  359.52  5482.5  361.18  5511.9  360.74
  5654.2  362.66  5668.9  363.58  5746.9  363.45  5890.9  366.08  5937.5  365.88
#Mann=5,-1,0
  4558.0    0.05       0  4716.9     0.1       0  4758.3    0.05       0
  5012.5    0.03       0  5018.5    0.05       0
Bank Sta=5012.5,5018.5
Exp/Cntr=0.3,0.1

Type RM Length L Ch R = 1,3047,115,115,115
BEGIN DESCRIPTION:
UNT029 IN SUCR 5.0
END DESCRIPTION:
XS GIS Cut Line= 2
      2293606.01     13428512.30      2293579.98     13430042.68
#Sta/Elev= 30
  4316.7  355.95  4374.7  355.95  4571.3  354.44  4621.3  353.24  4681.3  349.42
  4691.3  349.23  4821.3  348.35  4881.3  350.34  4911.3  349.60  4961.3  347.16
  4998.3  346.61  5001.1  346.11  5004.3  346.61  5031.4  347.30  5041.4  348.00
  5051.4  349.54  5070.1  350.53  5097.3  351.91  5102.3  351.24  5111.4  351.64
  5171.4  350.80  5251.4  352.04  5291.4  353.27  5401.4  353.74  5491.4  355.59
  5531.4  355.20  5673.0  355.66  5771.5  356.50  5831.5  358.36  5847.3  358.35
#Mann=6,-1,0
  4316.7     0.1       0  4374.7    0.05       0  4998.3    0.03       0
  5004.3    0.05       0  5070.1     0.1       0  5673.0    0.05       0
Bank Sta=4998.3,5004.3
Exp/Cntr=0.3,0.1

Type RM Length L Ch R = 1,2932,698,698,698
BEGIN DESCRIPTION:
UNT029 IN SUCR 4.0
END DESCRIPTION:
XS GIS Cut Line= 2
      2293501.84     13428496.69      2293486.22     13430069.61
#Sta/Elev= 30
  4247.3  352.82  4267.5  353.80  4297.5  353.89  4487.5  352.68  4517.5  353.00
  4587.5  351.64  4597.5  350.33  4637.5  348.94  4697.5  349.91  4727.5  351.84
  4737.5  351.39  4837.5  351.30  4937.5  349.57  4957.5  348.15  4977.5  345.16
  5004.5  344.90  5007.3  344.40  5010.5  344.90  5067.5  346.79  5117.5  349.18
  5147.5  349.82  5164.2  350.80  5169.2  351.89  5227.5  353.68  5327.5  354.86
  5501.4  354.15  5547.5  354.23  5577.5  354.95  5587.5  354.57  5820.3  355.76
#Mann=4,-1,0
  4247.3    0.08       0  5004.5    0.07       0  5010.5    0.08       0
  5501.4    0.05       0
Bank Sta=5004.5,5010.5
Exp/Cntr=0.3,0.1

Type RM Length L Ch R = 1,2234,589,589,589
BEGIN DESCRIPTION:
UNT029 IN SUCR 3.0
END DESCRIPTION:
XS GIS Cut Line= 3
      2292824.76     13428772.67      2292866.43     13429324.79
      2293453.84     13430109.74
#Sta/Elev= 30
  4516.1  363.72  4590.5  359.88  4600.5  360.09  4650.7  356.77  4670.7  356.75
  4690.8  354.99  4730.9  354.46  4781.0  351.51  4801.1  351.91  4854.3  349.92
  4887.0  348.28  4971.6  340.16  4991.6  339.96  4998.7  338.49  5001.4  337.99
  5004.7  338.49  5011.7  340.22  5051.8  345.85  5086.2  345.90  5094.1  345.79
  5308.7  346.95  5385.8  349.26  5550.4  351.55  5716.2  352.48  5720.4  352.38
  5842.2  353.89  5878.2  353.89  5968.3  354.87  6036.0  355.88  6050.2  356.26
#Mann=12,-1,0
  4516.1    0.05       0  4854.3     0.1       0  4998.7    0.07       0
  5004.7     0.1       0  5086.2    0.16       0  5094.1    0.05       0
  5716.2     0.1       0  5720.4    0.05       0  5842.2     0.1       0
  5878.2    0.05       0  5968.3     0.1       0  6036.0    0.05       0
Bank Sta=4998.7,5004.7
Exp/Cntr=0.3,0.1

Type RM Length L Ch R = 1,1645,656,656,656
BEGIN DESCRIPTION:
Mapping XS ca67754c
END DESCRIPTION:
XS GIS Cut Line= 4
      2292637.26     13428777.95      2292579.97     13429496.67
      2292600.80     13429803.96      2292981.00     13430460.18
#Sta/Elev= 30
  4104.0  363.19  4534.0  351.84  4555.6  350.05  4594.5  347.98  4614.5  348.80
  4694.8  345.58  4744.9  344.92  4785.1  340.80  4790.2  340.72  4795.2  343.52
  4804.2  343.73  4815.2  343.86  4822.6  341.01  4827.6  341.01  4845.2  337.70
  4855.3  337.22  4895.3  338.33  4954.0  337.94  5002.6  336.39  5005.3  335.89
  5008.6  336.39  5017.1  340.06  5025.6  342.10  5035.7  343.04  5146.0  343.54
  5278.6  345.80  5309.7  345.10  5506.2  347.81  5541.2  347.40  5891.4  353.95
#Mann=7,-1,0
  4104.0    0.05       0  4555.6     0.1       0  4804.2    0.12       0
  4954.0     0.1       0  5002.6    0.07       0  5008.6     0.1       0
  5146.0    0.05       0
Bank Sta=5002.6,5008.6
Exp/Cntr=0.3,0.1

Type RM Length L Ch R = 1,989,181,181,181
BEGIN DESCRIPTION:
Mapping XS 653d1f41
END DESCRIPTION:
XS GIS Cut Line= 4
      2292533.11     13428699.77      2292090.39     13429298.75
      2292053.93     13429652.92      2292547.73     13430453.39
#Sta/Elev= 30
  4059.0  363.15  4110.7  360.80  4154.6  360.52  4275.7  354.49  4304.1  354.68
  4332.0  352.53  4390.5  351.48  4467.7  348.28  4496.9  348.79  4560.4  346.24
  4738.9  342.41  4747.5  342.79  4762.1  337.87  4776.6  335.60  4783.0  333.26
  4812.0  331.06  4949.7  330.13  4952.5  329.63  4955.7  330.13  5017.5  330.34
  5116.3  330.37  5133.7  331.08  5165.1  335.03  5194.8  340.41  5212.0  340.72
  5225.9  340.79  5358.6  340.99  5501.1  341.58  5799.0  343.72  6100.4  347.95
#Mann=11,-1,0
  4059.0    0.05       0  4560.4     0.1       0  4738.9    0.07       0
  4949.7    0.07       0  4955.7    0.07       0  5017.5    0.12       0
  5116.3     0.1       0  5212.0    0.12       0  5225.9    0.05       0
  5358.6     0.1       0  5501.1    0.05       0
Bank Sta=4949.7,4955.7
Exp/Cntr=0.3,0.1

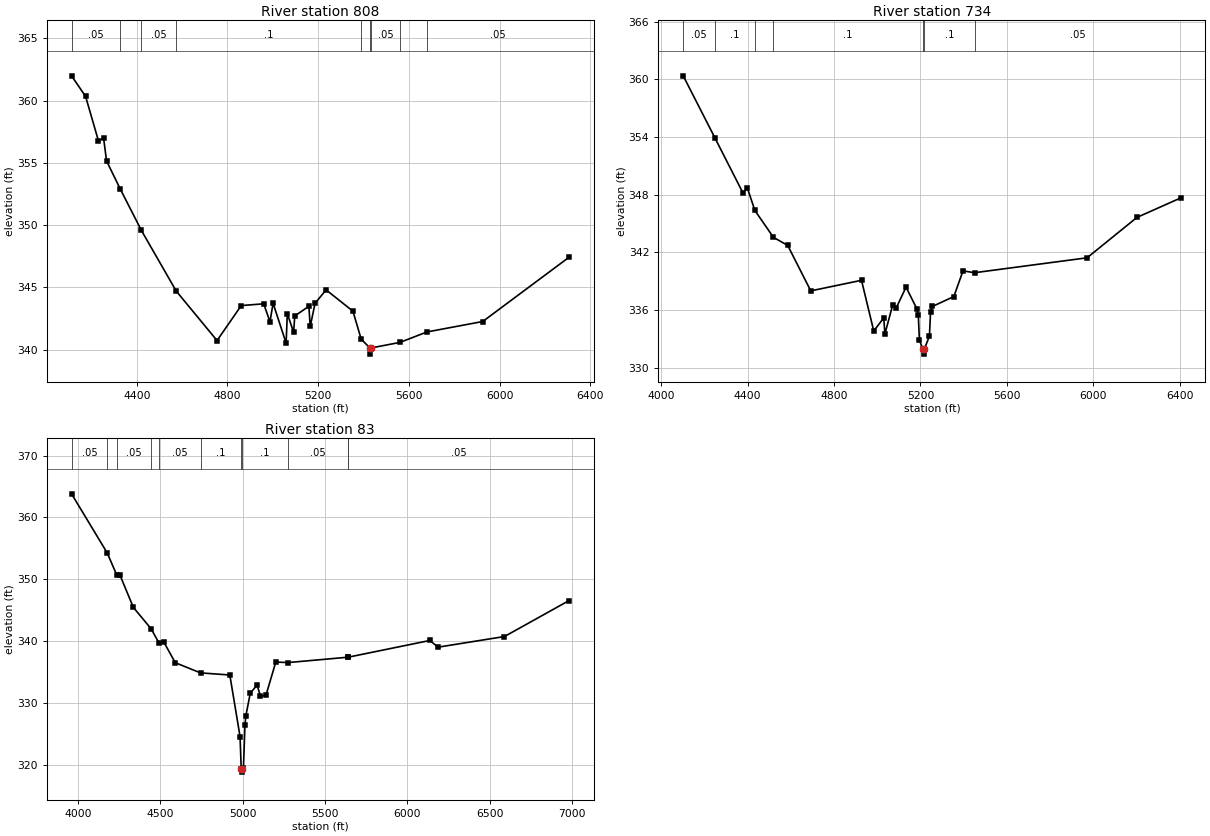
Type RM Length L Ch R = 1,808,74,74,74
BEGIN DESCRIPTION:
Mapping XS 4c4bb76b
END DESCRIPTION:
XS GIS Cut Line= 6
      2292439.34     13428632.09      2291981.01     13429262.29
      2291913.30     13429486.25      2291970.59     13429574.79
      2291970.59     13429694.58      2292470.60     13430507.09
#Sta/Elev= 30
  4112.5  361.99  4174.4  360.34  4230.8  356.79  4254.0  356.98  4266.8  355.16
  4327.0  352.91  4420.6  349.57  4574.2  344.70  4754.0  340.73  4860.7  343.54
  4959.7  343.68  4987.4  342.24  5001.0  343.73  5058.5  340.52  5063.8  342.89
  5091.5  341.40  5096.7  342.71  5158.8  343.48  5164.8  341.86  5186.0  343.72
  5234.7  344.80  5353.0  343.09  5389.5  340.84  5427.7  340.14  5430.4  339.64
  5433.7  340.14  5560.2  340.58  5679.3  341.42  5925.3  342.26  6305.0  347.41
#Mann=9,-1,0
  4112.5    0.05       0  4327.0     0.1       0  4420.6    0.05       0
  4574.2     0.1       0  5389.5    0.05       0  5427.7    0.07       0
  5433.7    0.05       0  5560.2     0.1       0  5679.3    0.05       0
Bank Sta=5427.7,5433.7
Exp/Cntr=0.3,0.1

Type RM Length L Ch R = 1,734,651,651,651
BEGIN DESCRIPTION:
UNT029 IN SUCR 2.0
END DESCRIPTION:
XS GIS Cut Line= 4
      2292366.43     13428600.83      2291897.68     13429251.87
      2291814.34     13429678.96      2292382.08     13430580.04
#Sta/Elev= 30
  4101.6  360.36  4248.2  353.91  4377.9  348.19  4398.7  348.69  4433.2  346.36
  4519.2  343.56  4585.3  342.72  4692.1  337.99  4927.0  339.09  4983.6  333.82
  5030.1  335.18  5035.2  333.50  5071.9  336.57  5086.8  336.17  5133.1  338.38
  5184.0  336.09  5190.0  335.47  5195.0  332.87  5211.6  331.91  5214.3  331.41
  5217.6  331.91  5241.5  333.29  5246.6  335.78  5255.3  336.37  5354.5  337.40
  5396.9  340.07  5450.2  339.88  5971.3  341.43  6202.0  345.63  6404.0  347.65
#Mann=7,-1,0
  4101.6    0.05       0  4248.2     0.1       0  4433.2    0.05       0
  4519.2     0.1       0  5211.6    0.07       0  5217.6     0.1       0
  5450.2    0.05       0
Bank Sta=5211.6,5217.6
Exp/Cntr=0.3,0.1

Type RM Length L Ch R = 1,83,0,0,0
BEGIN DESCRIPTION:
UNT029 IN SUCR 1.0
END DESCRIPTION:
XS GIS Cut Line= 5
      2292333.45     13428428.96      2291569.55     13428748.40
      2291437.61     13429262.29      2291500.11     13429824.79
      2292138.36     13430712.80
#Sta/Elev= 30
  3962.3  363.82  4178.6  354.27  4235.8  350.75  4255.3  350.72  4337.6  345.45
  4444.8  342.01  4492.5  339.73  4521.3  339.90  4591.8  336.51  4745.1  334.86
  4922.9  334.52  4984.9  324.57  4992.2  319.31  4994.9  318.81  4998.2  319.31
  5005.5  319.48  5014.7  326.37  5019.9  327.87  5046.8  331.56  5088.1  332.90
  5108.8  331.11  5142.2  331.24  5201.7  336.61  5276.5  336.53  5641.1  337.40
  5641.3  337.40  6136.5  340.10  6186.8  339.02  6589.5  340.74  6980.4  346.54
#Mann=11,-1,0
  3962.3    0.05       0  4178.6     0.1       0  4235.8    0.05       0
  4444.8     0.1       0  4492.5    0.05       0  4745.1     0.1       0
  4992.2    0.07       0  4998.2     0.1       0  5276.5    0.05       0
  5641.1     0.1       0  5641.3    0.05       0
Bank Sta=4992.2,4998.2
Exp/Cntr=0.3,0.1

Chan Stop Cuts=-1