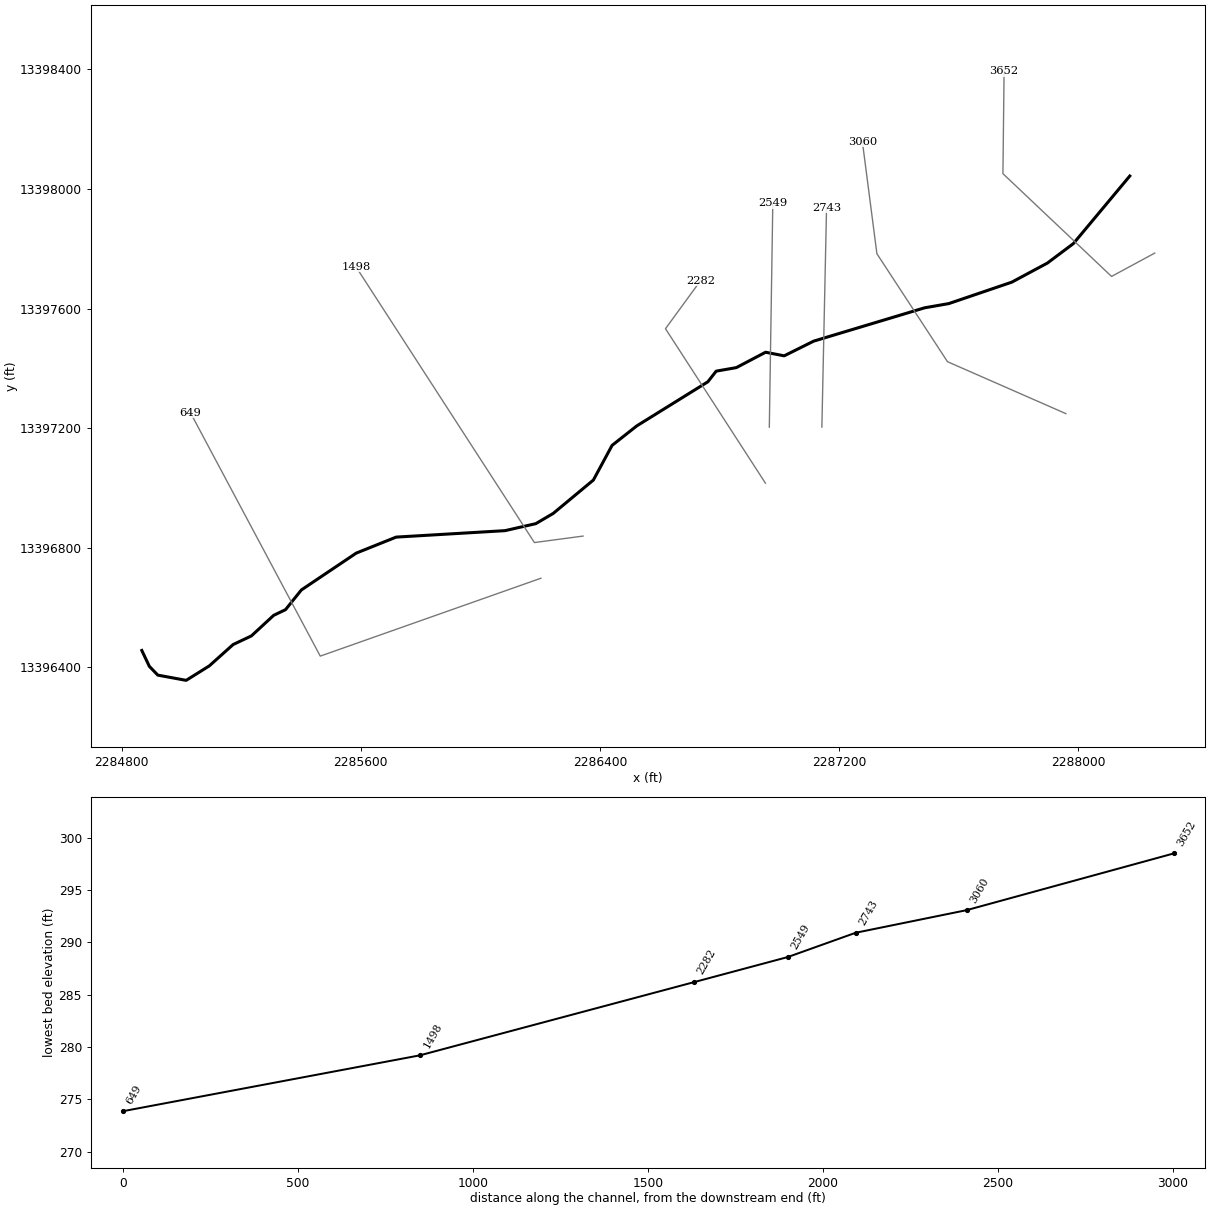
--- UNT0297 IN SUCR.prj (project) ---

Proj Title=UNT0297 IN SUCR Base Level Engineering
Current Plan=p01
Default Exp/Contr=0.3,0.1
English Units
Geom File=g01
Flow File=f01
Plan File=p01
Y Axis Title=Elevation
X Axis Title(PF)=Main Channel Distance
X Axis Title(XS)=Station
BEGIN DESCRIPTION:
UNT0297 IN SUCR
END DESCRIPTION:
DSS Export Rating Curves= 0
DSS Export Rating Curve Sorted= 0
DSS Export Volume Flow Curves= 0
DXF OffsetX= 0
DXF OffsetY= 0
DXF ScaleX= 1
DXF ScaleY= 10

--- UNT0297 IN SUCR.p01 (plan) ---

Plan Title=Multiple Run
Short Identifier=Multiple
Geom File=g01
Flow File=f01
Subcritical Flow
K Sum by GR= 0
Std Step Tol= 0.01
Critical Tol= 0.01
Num of Std Step Trials= 20
Max Error Tol= 0.3
Flow Tol Ratio= 0.001
Split Flow NTrial= 30
Split Flow Tol= 0.02
Split Flow Ratio= 0.02
Log Output Level= 0
Friction Slope Method= 1
Unsteady Friction Slope Method= 2
Unsteady Bridges Friction Slope Method= 1
Parabolic Critical Depth
Global Vel Dist=  1 , 1 , 1
Global Log Level= 0
CheckData=True
Encroach Param= -1, 0, 0, 0
BEGIN DESCRIPTION:
Multiple Run
END DESCRIPTION:

--- UNT0297 IN SUCR.f01 (steady flow) ---

Flow Title=Multiple
Program Version=4.10
Number of Profiles= 7
Profile Names=10-year,25-year,50-year,1pct_min,100-year,1pct_plu,500-year
River Rch & RM=UNT0297 IN SUCR,Reach-1         ,3652
      84     108     126     109     148     200     204
River Rch & RM=UNT0297 IN SUCR,Reach-1         ,2549
      90     117     137     119     161     218     225
River Rch & RM=UNT0297 IN SUCR,Reach-1         ,1498
     144     193     232     205     278     376     404
Boundary for River Rch & Prof#=UNT0297 IN SUCR,Reach-1         , 1
Up Type= 0
Dn Type= 3
Dn Slope=0.01
Boundary for River Rch & Prof#=UNT0297 IN SUCR,Reach-1         , 2
Up Type= 0
Dn Type= 3
Dn Slope=0.01
Boundary for River Rch & Prof#=UNT0297 IN SUCR,Reach-1         , 3
Up Type= 0
Dn Type= 3
Dn Slope=0.01
Boundary for River Rch & Prof#=UNT0297 IN SUCR,Reach-1         , 4
Up Type= 0
Dn Type= 3
Dn Slope=0.01
Boundary for River Rch & Prof#=UNT0297 IN SUCR,Reach-1         , 5
Up Type= 0
Dn Type= 3
Dn Slope=0.01
Boundary for River Rch & Prof#=UNT0297 IN SUCR,Reach-1         , 6
Up Type= 0
Dn Type= 3
Dn Slope=0.01
Boundary for River Rch & Prof#=UNT0297 IN SUCR,Reach-1         , 7
Up Type= 0
Dn Type= 3
Dn Slope=0.01
DSS Import GetInterval= 0
DSS Import GetPeak= 0
DSS Import FillOption= 0

--- UNT0297 IN SUCR.g01 (geometry) ---

Geom Title=Existing Conditions
Program Version=4.10

River Reach=UNT0297 IN SUCR ,Reach-1
Reach XY= 30
      2288171.71     13398043.53      2287983.17     13397817.59
      2287896.36     13397752.48        2287777.     13397688.46
       2287566.5     13397616.85      2287485.55     13397602.74
      2287114.73     13397491.33      2287015.96     13397442.16
       2286953.7     13397454.16      2286856.02     13397402.78
      2286788.51     13397390.94      2286760.73     13397355.35
      2286522.88     13397207.78      2286440.42     13397142.67
      2286377.81      13397026.7       2286243.6     13396915.19
      2286185.43     13396880.95      2286082.46     13396857.51
      2285718.21     13396835.92      2285584.84     13396782.42
      2285401.31     13396659.22      2285348.37     13396593.38
      2285308.63     13396574.25      2285234.16     13396505.47
      2285173.12     13396476.67      2285093.32     13396405.17
      2285016.04     13396356.88      2284921.23     13396374.35
      2284892.89     13396403.75      2284867.72     13396456.85

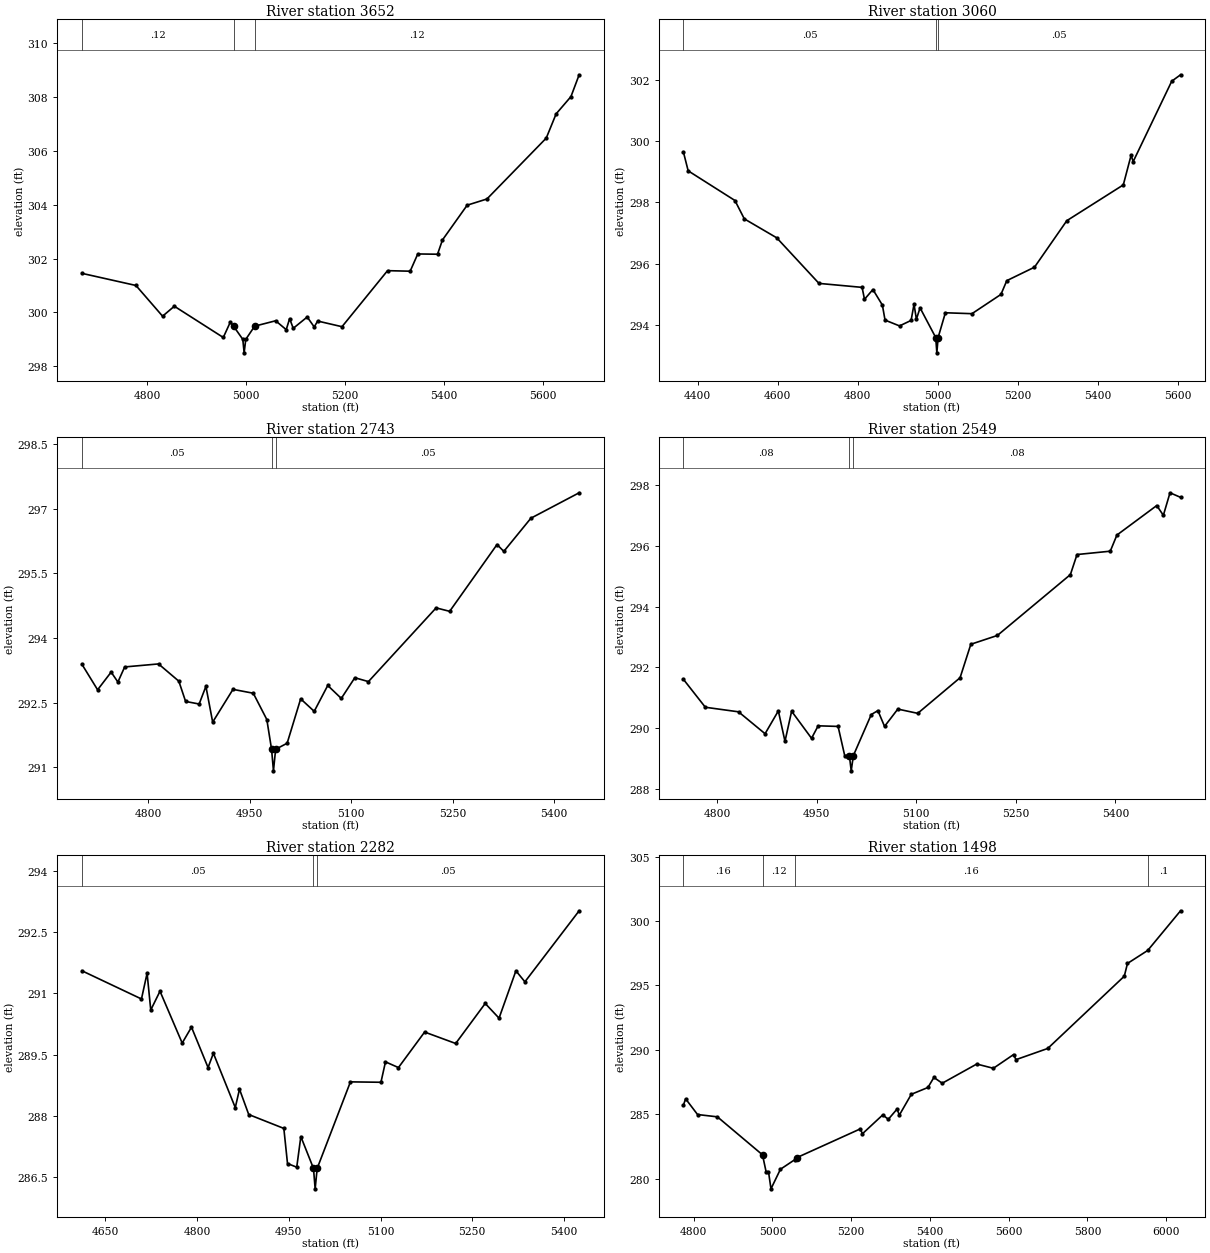
Type RM Length L Ch R = 1 ,3652    ,592,592,592
BEGIN DESCRIPTION:
UNT0297 IN SUCR 3.0
END DESCRIPTION:
XS GIS Cut Line= 4
      2288255.27      13397785.8      2288110.76     13397707.68
      2287747.48     13398051.43      2287751.36      13398393.5
#Sta/Elev= 30
  4667.6  301.45  4776.9     301  4830.8  299.86  4854.6  300.23  4953.7  299.07
  4967.9  299.64  4974.8  299.48  4993.2     299  4995.9   298.5  4999.2     299
  5017.2  299.49  5059.7  299.69  5081.1  299.36    5088  299.77  5095.3  299.41
  5123.6  299.83  5137.8  299.46  5144.7  299.68    5194  299.47  5286.2  301.55
    5332  301.53  5347.4  302.17  5387.4  302.16  5397.4  302.69  5447.4  303.98
  5487.4  304.21  5607.5  306.47  5627.5  307.37  5657.5  308.01  5674.1  308.82
#Mann= 3 , 0 , 0
  4667.6     .12       0  4974.8      .1       0  5017.2     .12       0
Bank Sta=4974.8,5017.2
XS Rating Curve= 0 ,0
Exp/Cntr=0.3,0.1

Type RM Length L Ch R = 1 ,3060    ,317,317,317
BEGIN DESCRIPTION:
Mapping XS b0474e36
END DESCRIPTION:
XS GIS Cut Line= 4
      2287957.94     13397248.91      2287562.13     13397422.51
      2287326.02     13397783.62      2287277.41     13398158.63
#Sta/Elev= 30
  4364.7  299.65  4376.7  299.03  4493.5  298.06  4516.9  297.46  4597.9  296.84
  4703.4  295.35  4811.1  295.22  4817.1  294.83  4838.1  295.15  4861.8  294.64
  4868.4  294.15  4904.6  293.96  4933.5  294.14  4940.8  294.67  4946.7  294.18
  4955.9  294.55    4995  293.58  4997.8  293.08    5001  293.58  5019.1  294.39
  5085.5  294.36  5157.9  294.99  5172.5  295.44  5241.7  295.88  5322.4   297.4
  5463.5  298.57    5483  299.54  5488.1  299.33  5584.5  301.96  5606.5  302.17
#Mann= 3 ,-1 , 0
  4364.7     .05       0    4995     .03       0    5001     .05       0
Bank Sta=4995,5001
XS Rating Curve= 0 ,0
Exp/Cntr=0.3,0.1

Type RM Length L Ch R = 1 ,2743    ,194,194,194
BEGIN DESCRIPTION:
Mapping XS f51ad4d7
END DESCRIPTION:
XS GIS Cut Line= 2
      2287142.01      13397203.8      2287157.63     13397938.13
#Sta/Elev= 30
  4702.3  293.39  4725.4   292.8  4745.4  293.21  4755.4  292.98  4765.4  293.33
  4815.4   293.4  4845.4     293  4855.4  292.53  4875.4  292.47  4885.4  292.88
  4895.4  292.05  4925.4  292.81  4955.4  292.72  4975.4  292.11  4982.4  291.42
  4985.2  290.92  4988.4  291.42  5005.4  291.56  5025.4  292.59  5045.4   292.3
  5065.4   292.9  5085.4   292.6  5105.4  293.08  5125.5  292.99  5225.5   294.7
  5245.5  294.62  5315.5  296.17  5325.5  296.01  5365.5  296.78  5436.8  297.37
#Mann= 3 ,-1 , 0
  4702.3     .05       0  4982.4     .03       0  4988.4     .05       0
Bank Sta=4982.4,4988.4
XS Rating Curve= 0 ,0
Exp/Cntr=0.3,0.1

Type RM Length L Ch R = 1 ,2549    ,267,267,267
BEGIN DESCRIPTION:
Mapping XS 98834fd7
END DESCRIPTION:
XS GIS Cut Line= 2
      2286966.23     13397203.78      2286977.93     13397952.79
#Sta/Elev= 30
  4749.1  291.61  4782.2  290.69  4832.2  290.54  4872.2  289.82  4892.2  290.57
  4902.2  289.57  4912.2  290.56  4942.2  289.67  4952.2  290.08  4982.2  290.06
  4992.2   289.1  4999.2   289.1    5002   288.6  5005.2   289.1  5032.2  290.45
  5042.2  290.58  5052.2  290.06  5072.2  290.63  5102.2  290.49    5166  291.66
  5182.2  292.76  5222.2  293.05  5332.2  295.05  5342.2  295.71  5392.3  295.82
  5402.3  296.35  5462.3  297.32  5472.3     297  5482.3  297.74  5498.2  297.59
#Mann= 3 ,-1 , 0
  4749.1     .08       0  4999.2     .07       0  5005.2     .08       0
Bank Sta=4999.2,5005.2
XS Rating Curve= 0 ,0
Exp/Cntr=0.3,0.1

Type RM Length L Ch R = 1 ,2282    ,784,784,784
BEGIN DESCRIPTION:
UNT0297 IN SUCR 2.0
END DESCRIPTION:
XS GIS Cut Line= 3
      2286953.18     13397016.41        2286619.     13397532.87
      2286735.63     13397692.69
#Sta/Elev= 30
  4611.8  291.55  4709.1  290.86  4718.3  291.49  4724.3  290.59  4739.4  291.05
  4775.7  289.78  4790.9  290.17    4818  289.18  4826.7  289.53  4862.5   288.2
  4869.4  288.65  4884.5  288.03  4941.9  287.69  4947.9  286.83    4963  286.74
  4969.7  287.49  4990.4  286.71  4993.1  286.21  4996.4  286.71  5050.8  288.83
  5100.7  288.82  5108.1  289.32  5129.3  289.18  5172.1  290.05  5222.9  289.77
  5271.2  290.75  5293.8  290.39  5321.4  291.55  5336.1  291.28  5424.8  293.02
#Mann= 3 ,-1 , 0
  4611.8     .05       0  4990.4     .03       0  4996.4     .05       0
Bank Sta=4990.4,4996.4
XS Rating Curve= 0 ,0
Exp/Cntr=0.3,0.1

Type RM Length L Ch R = 1 ,1498    ,849,849,849
BEGIN DESCRIPTION:
Mapping XS a5a49516
END DESCRIPTION:
XS GIS Cut Line= 3
      2286343.36      13396839.4      2286180.64     13396817.71
      2285583.86     13397740.01
#Sta/Elev= 30
  4773.9   285.7  4779.6   286.2  4809.9  284.98  4860.3   284.8  4974.9  281.85
  4984.1  280.52  4990.1  280.54  4996.4  279.21  5020.4  280.73  5056.2  281.46
  5062.6  281.64  5222.9  283.86  5228.8  283.49  5280.2  284.95  5294.4  284.61
  5316.5   285.4  5322.5  284.94  5352.8  286.55    5395  287.08  5410.2  287.86
  5431.3  287.41    5519   288.9  5561.2  288.57  5612.7  289.64  5618.6  289.24
  5699.3  290.11  5893.7  295.72  5901.8  296.71  5953.2  297.72  6036.6   300.8
#Mann= 4 ,-1 , 0
  4773.9     .16       0  4974.9     .12       0  5056.2     .16       0
  5953.2      .1       0
Bank Sta=4974.9,5062.6
XS Rating Curve= 0 ,0
Exp/Cntr=0.3,0.1

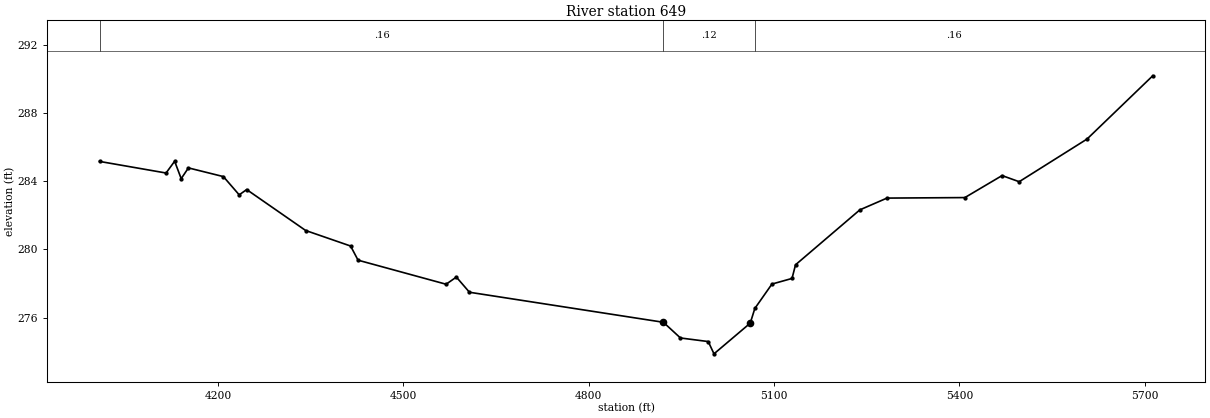
Type RM Length L Ch R = 1 ,649     ,0,0,0
BEGIN DESCRIPTION:
UNT0297 IN SUCR 1.0
END DESCRIPTION:
XS GIS Cut Line= 3
      2286202.38     13396698.37      2285464.49     13396437.93
      2285030.47     13397251.73
#Sta/Elev= 30
  4008.1  285.15  4115.8  284.47  4129.7  285.16  4140.3  284.14    4152  284.77
  4208.6  284.26  4234.2  283.19  4246.3   283.5  4341.8   281.1  4414.5  280.19
  4426.6  279.36  4569.1  277.95  4585.7  278.37  4606.9  277.48  4920.8  275.72
  4948.4   274.8  4993.4  274.59  5002.7  273.87  5061.4  275.67  5068.8  276.53
  5096.5  277.96    5129  278.29  5134.7  279.09  5238.8  282.31  5282.7     283
  5408.8  283.03    5469  284.32  5496.7  283.96  5606.5  286.46  5712.9  290.17
#Mann= 3 ,-1 , 0
  4008.1     .16       0  4920.8     .12       0  5068.8     .16       0
Bank Sta=4920.8,5061.4
XS Rating Curve= 0 ,0
Exp/Cntr=0.3,0.1

Chan Stop Cuts=-1
Use User Specified Reach Order=0
Composite Channel Slope=5