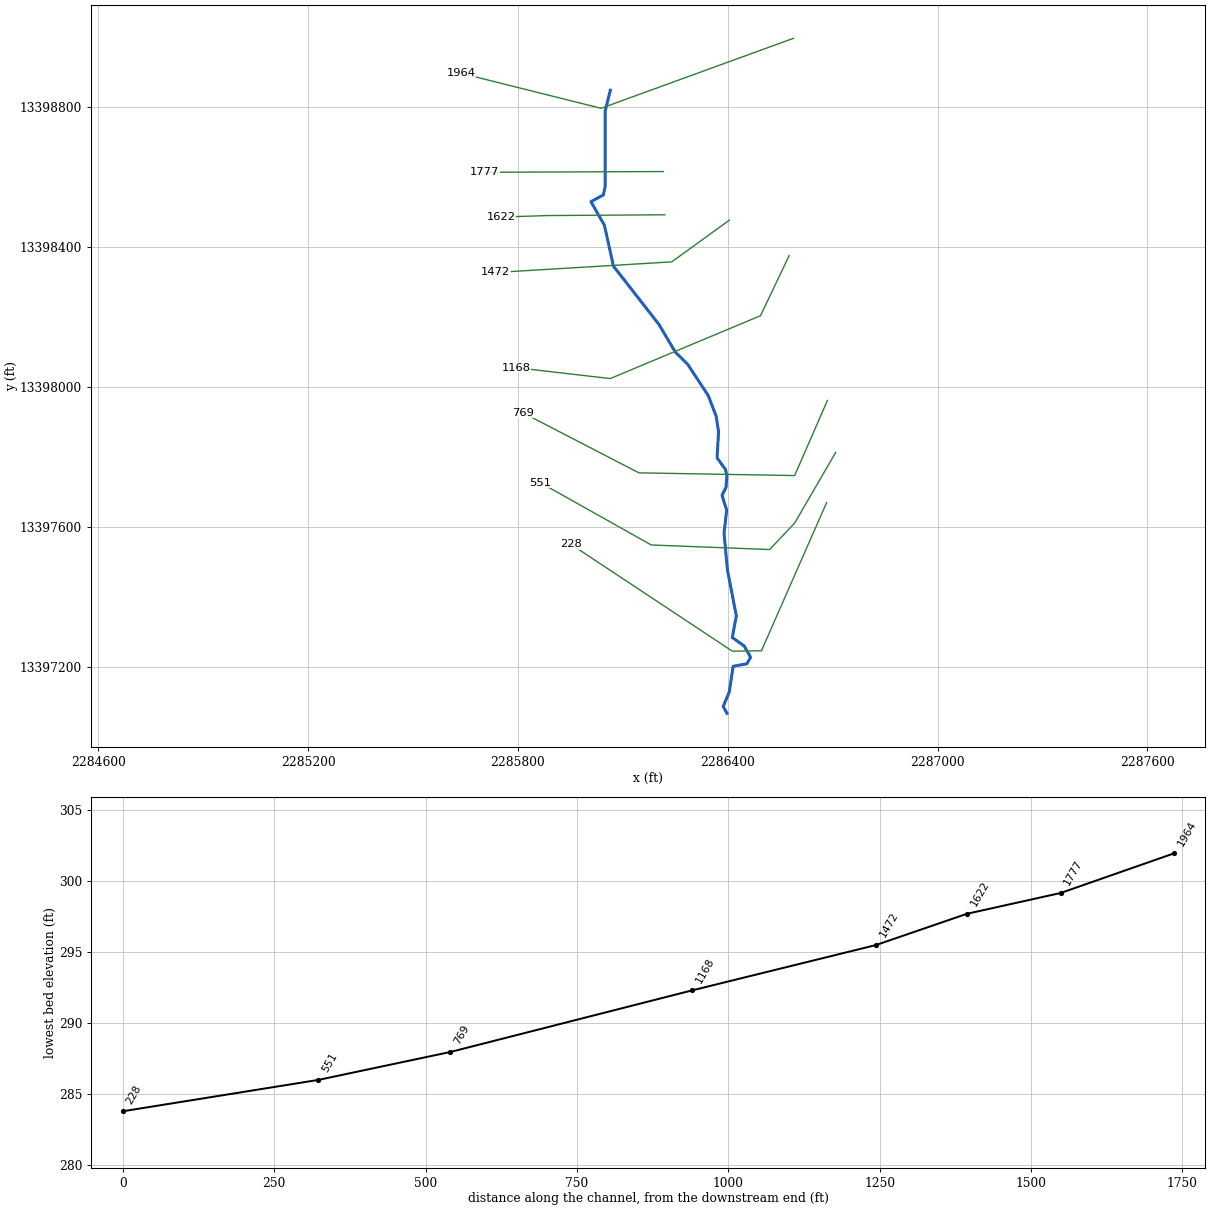
--- UNT0298 IN SUCR.prj (project) ---

Proj Title=UNT0298 IN SUCR Base Level Engineering
Current Plan=p01
Default Exp/Contr=0.3,0.1
English Units
Geom File=g01
Flow File=f01
Plan File=p01
Y Axis Title=Elevation
X Axis Title(PF)=Main Channel Distance
X Axis Title(XS)=Station
BEGIN DESCRIPTION:
UNT0298 IN SUCR
END DESCRIPTION:
DSS Export Rating Curves= 0
DSS Export Rating Curve Sorted= 0
DSS Export Volume Flow Curves= 0
DXF OffsetX= 0
DXF OffsetY= 0
DXF ScaleX= 1
DXF ScaleY= 10

--- UNT0298 IN SUCR.p01 (plan) ---

Plan Title=Multiple Run
Short Identifier=Multiple
Geom File=g01
Flow File=f01
Subcritical Flow
K Sum by GR= 0
Std Step Tol= 0.01
Critical Tol= 0.01
Num of Std Step Trials= 20
Max Error Tol= 0.3
Flow Tol Ratio= 0.001
Split Flow NTrial= 30
Split Flow Tol= 0.02
Split Flow Ratio= 0.02
Log Output Level= 0
Friction Slope Method= 1
Unsteady Friction Slope Method= 2
Unsteady Bridges Friction Slope Method= 1
Parabolic Critical Depth
Global Vel Dist=  1 , 1 , 1
Global Log Level= 0
CheckData=True
Encroach Param= -1, 0, 0, 0
BEGIN DESCRIPTION:
Multiple Run
END DESCRIPTION:

--- UNT0298 IN SUCR.f01 (steady flow) ---

Flow Title=Multiple
Program Version=4.10
Number of Profiles= 7
Profile Names=10-year,25-year,50-year,1pct_min,100-year,1pct_plu,500-year
River Rch & RM=UNT0298 IN SUCR,Reach-1         ,1964
      68      87     101      87     118     159     162
Boundary for River Rch & Prof#=UNT0298 IN SUCR,Reach-1         , 1
Up Type= 0
Dn Type= 3
Dn Slope=0.01
Boundary for River Rch & Prof#=UNT0298 IN SUCR,Reach-1         , 2
Up Type= 0
Dn Type= 3
Dn Slope=0.01
Boundary for River Rch & Prof#=UNT0298 IN SUCR,Reach-1         , 3
Up Type= 0
Dn Type= 3
Dn Slope=0.01
Boundary for River Rch & Prof#=UNT0298 IN SUCR,Reach-1         , 4
Up Type= 0
Dn Type= 3
Dn Slope=0.01
Boundary for River Rch & Prof#=UNT0298 IN SUCR,Reach-1         , 5
Up Type= 0
Dn Type= 3
Dn Slope=0.01
Boundary for River Rch & Prof#=UNT0298 IN SUCR,Reach-1         , 6
Up Type= 0
Dn Type= 3
Dn Slope=0.01
Boundary for River Rch & Prof#=UNT0298 IN SUCR,Reach-1         , 7
Up Type= 0
Dn Type= 3
Dn Slope=0.01
DSS Import GetInterval= 0
DSS Import GetPeak= 0
DSS Import FillOption= 0

--- UNT0298 IN SUCR.g01 (geometry) ---

Geom Title=Existing Conditions
Program Version=4.10

River Reach=UNT0298 IN SUCR ,Reach-1
Reach XY= 30
      2286064.36     13398848.51      2286049.61     13398789.48
      2286049.61     13398573.34       2286044.4     13398549.03
      2286008.81     13398529.93      2286047.36     13398462.24
      2286073.35      13398345.4      2286202.76     13398179.54
      2286250.77     13398098.73      2286284.89      13398065.6
      2286344.33     13397975.44      2286366.86     13397916.38
      2286373.76     13397871.88      2286369.42     13397797.16
      2286393.51     13397764.28      2286397.49     13397746.49
      2286395.17     13397713.41      2286383.57     13397690.25
        2286397.     13397648.29      2286389.36      13397581.9
       2286399.1     13397476.79      2286424.53     13397345.71
      2286412.93     13397283.76      2286447.06     13397259.42
      2286465.35     13397227.24      2286454.57     13397208.59
      2286415.32     13397201.49      2286404.33     13397128.24
      2286387.03     13397086.41      2286397.72     13397066.85

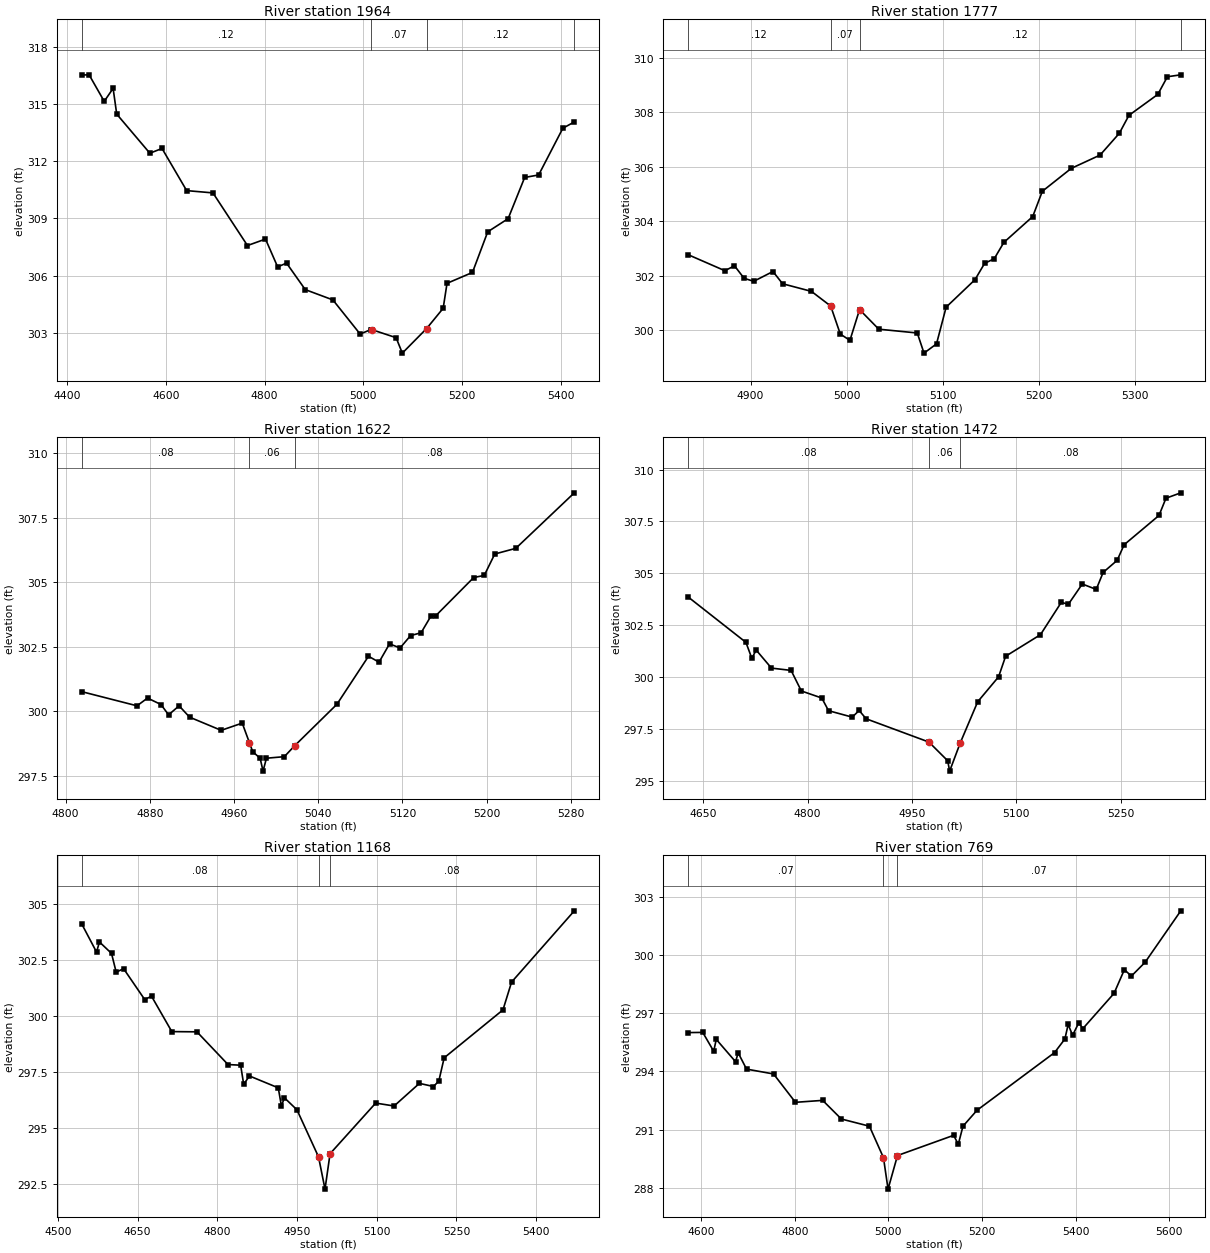
Type RM Length L Ch R = 1 ,1964    ,187,187,187
BEGIN DESCRIPTION:
UNT0298 IN SUCR 4.0
END DESCRIPTION:
XS GIS Cut Line= 3
      2286587.73     13398996.86      2286037.72     13398796.85
      2285637.68     13398896.87
#Sta/Elev= 30
  4429.5  316.52  4444.8  316.53  4475.4  315.14  4493.4  315.82  4500.7  314.47
  4567.8  312.42  4592.4  312.67  4642.3  310.46  4695.5  310.34  4765.4  307.58
  4801.9  307.92  4826.5  306.46  4844.5  306.66  4882.4  305.27  4938.3  304.73
  4993.5  302.94  5014.7  303.17  5017.3  303.17  5066.3  302.75  5078.9  301.94
  5128.1  303.23  5161.6  304.29  5169.4   305.6  5220.9  306.17  5251.8   308.3
  5293.1  308.99  5326.6  311.15  5354.9  311.28  5403.9  313.73  5427.1  314.06
#Mann= 4 ,-1 , 0
  4429.5     .12       0  5014.7     .07       0  5128.1     .12       0
  5427.1     .05       0
Bank Sta=5017.3,5128.1
XS Rating Curve= 0 ,0
Exp/Cntr=0.3,0.1

Type RM Length L Ch R = 1 ,1777    ,155,155,155
BEGIN DESCRIPTION:
Mapping XS 456c5eb5
END DESCRIPTION:
XS GIS Cut Line= 2
      2286216.04     13398616.03      2285703.85     13398613.86
#Sta/Elev= 30
    4835  302.77  4873.3  302.18  4883.3  302.36  4893.3   301.9  4903.3  301.79
  4923.3  302.15  4933.3   301.7  4963.3  301.42  4983.3  300.88  4993.3  299.85
  5003.3  299.62  5013.3  300.75  5033.3  300.03  5073.3  299.89  5080.3  299.15
  5093.3  299.49  5103.3  300.84  5133.3  301.85  5143.3  302.45  5153.3  302.62
  5163.3  303.22  5193.3  304.17  5203.3   305.1  5233.3  305.94  5263.3  306.43
  5283.3  307.23  5293.3  307.89  5323.3  308.66  5333.3  309.31  5347.2  309.38
#Mann= 4 ,-1 , 0
    4835     .12       0  4983.3     .07       0  5013.3     .12       0
  5347.2     .05       0
#XS Ineff= 1 ,-1
 5014.17    5125  300.62
Permanent Ineff=
       T
Bank Sta=4983.3,5013.3
XS Rating Curve= 0 ,0
Exp/Cntr=0.3,0.1

Type RM Length L Ch R = 1 ,1622    ,150,150,150
BEGIN DESCRIPTION:
Mapping XS 33dab36e
END DESCRIPTION:
XS GIS Cut Line= 3
      2286220.42     13398492.33        2285884.     13398490.16
       2285752.2     13398485.84
#Sta/Elev= 30
  4815.1  300.76  4867.8  300.21  4877.8  300.51  4890.6  300.26  4897.8  299.86
  4907.8  300.21  4917.8  299.77  4947.8  299.26  4967.8  299.54 4974.65  298.78
  4977.8  298.43  4984.8  298.18  4987.6  297.68  4990.8  298.18  5007.8  298.24
  5017.8  298.67  5057.8  300.27  5087.8  302.13  5097.8   301.9  5107.8  302.61
  5117.8  302.45  5127.8  302.93  5137.8  303.04  5147.2  303.69  5151.5  303.69
  5187.8  305.18  5197.8  305.26  5207.8  306.09  5227.8  306.31  5283.4  308.46
#Mann= 3 ,-1 , 0
  4815.1     .08       0 4974.65     .06       0  5017.8     .08       0
Bank Sta=4974.65,5017.8
XS Rating Curve= 0 ,0
Exp/Cntr=0.3,0.1

Type RM Length L Ch R = 1 ,1472    ,304,304,304
BEGIN DESCRIPTION:
UNT0298 IN SUCR 3.0
END DESCRIPTION:
XS GIS Cut Line= 3
      2286404.86     13398477.16      2286239.91     13398357.78
      2285736.44      13398327.4
#Sta/Elev= 30
  4628.3  303.87  4711.5  301.68    4720  300.91  4726.2  301.31  4748.2  300.44
  4776.4  300.33  4791.1  299.34  4820.5     299  4830.2  298.39  4864.2  298.08
  4874.2   298.4  4884.2     298  4974.4  296.88  5001.4  295.98  5004.2  295.48
 5019.44  296.84  5044.5  298.82  5074.5  300.02  5084.6  301.01  5134.7  302.05
  5164.7  303.61  5174.7  303.51  5194.8  304.49  5214.8  304.23  5224.8  305.05
  5244.9  305.63  5254.9  306.38    5305  307.79    5315  308.62  5336.3  308.88
#Mann= 3 , 0 , 0
  4628.3     .08       0  4974.4     .06       0 5019.44     .08       0
Bank Sta=4974.4,5019.44
XS Rating Curve= 0 ,0
Exp/Cntr=0.3,0.1

Type RM Length L Ch R = 1 ,1168    ,399,399,399
BEGIN DESCRIPTION:
UNT0298 IN SUCR 2.0
END DESCRIPTION:
XS GIS Cut Line= 4
      2286575.62     13398375.69      2286493.57     13398203.78
      2286063.88     13398024.09      2285794.33     13398055.34
#Sta/Elev= 30
  4544.4  304.13  4572.6  302.86  4578.1  303.31  4600.8   302.8  4609.6  301.96
  4623.5  302.12  4663.3  300.74  4676.1  300.89  4714.3  299.31  4761.6   299.3
  4820.1  297.84  4843.9  297.81  4849.6  296.96  4860.5  297.33  4914.7   296.8
  4920.7  295.98  4926.1  296.36  4949.9  295.82  4990.5  293.72  5002.7  292.28
  5012.2  293.86  5098.1  296.12  5132.8  295.99  5180.4     297  5206.8  296.86
  5216.9   297.1    5227  298.14  5337.7  300.28  5353.9  301.52    5472   304.7
#Mann= 3 , 0 , 0
  4544.4     .08       0  4990.5     .06       0  5012.2     .08       0
Bank Sta=4990.5,5012.2
XS Rating Curve= 0 ,0
Exp/Cntr=0.3,0.1

Type RM Length L Ch R = 1 ,769     ,218,218,218
BEGIN DESCRIPTION:
Mapping XS b6b481d0
END DESCRIPTION:
XS GIS Cut Line= 4
      2286684.96     13397961.55      2286591.23     13397746.74
      2286145.91     13397754.56      2285813.91     13397926.42
#Sta/Elev= 30
  4571.5     296    4603  296.01  4626.4  295.04  4631.9  295.65  4673.2   294.5
  4678.7  294.96  4696.6  294.12  4754.4  293.87  4801.2  292.41  4859.4  292.51
  4899.4  291.55  4959.4  291.18  4989.4  289.56  4999.2  287.94  5019.4  289.67
  5139.4  290.71  5149.4  290.25  5159.4  291.18  5189.4     292  5355.2  294.97
  5377.3  295.67  5384.3  296.42  5393.8  295.86  5406.9   296.5  5415.9  296.21
  5482.4  298.02  5504.5  299.24  5519.5  298.91  5548.8  299.62  5625.1  302.27
#Mann= 3 , 0 , 0
  4571.5     .07       0  4989.4     .05       0  5019.4     .07       0
Bank Sta=4989.4,5019.4
XS Rating Curve= 0 ,0
Exp/Cntr=0.3,0.1

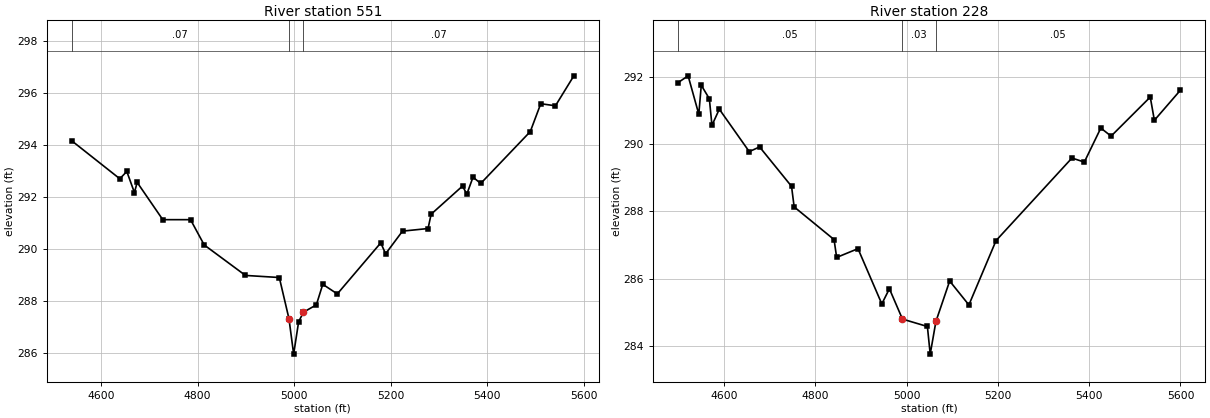
Type RM Length L Ch R = 1 ,551     ,323,323,323
BEGIN DESCRIPTION:
Mapping XS 8d1d6c63
END DESCRIPTION:
XS GIS Cut Line= 5
      2286708.65     13397813.07      2286591.47     13397611.25
      2286519.85      13397535.3      2286181.31     13397548.32
      2285864.52     13397726.25
#Sta/Elev= 30
  4539.1  294.16  4638.8   292.7  4653.3  292.98  4669.1  292.17  4674.8  292.56
  4727.8  291.13  4785.3  291.13  4813.6  290.16    4899  288.99  4969.1  288.91
  4989.1  287.33  4998.8  285.97  5009.1  287.21  5019.1  287.58  5045.8  287.86
  5059.1  288.65  5089.2  288.28  5179.2  290.24  5189.2  289.82  5224.2  290.69
  5277.1  290.79  5283.5  291.34  5348.5  292.42  5357.4  292.11  5370.2  292.76
  5386.2  292.52  5488.8  294.51  5510.5  295.58  5540.9   295.5    5579  296.65
#Mann= 3 , 0 , 0
  4539.1     .07       0  4989.1     .05       0  5019.1     .07       0
Bank Sta=4989.1,5019.1
XS Rating Curve= 0 ,0
Exp/Cntr=0.3,0.1

Type RM Length L Ch R = 1 ,228     ,0,0,0
BEGIN DESCRIPTION:
UNT0298 IN SUCR 1.0
END DESCRIPTION:
XS GIS Cut Line= 4
      2286682.64     13397669.42      2286496.35     13397245.92
      2286413.13     13397244.68       2285951.3     13397550.51
#Sta/Elev= 30
  4499.8  291.82  4521.7  292.02  4545.1  290.88  4550.5  291.74  4568.2  291.34
  4573.9  290.55    4590  291.03  4655.6  289.77  4678.2  289.91  4748.2  288.74
  4753.9  288.13  4841.3  287.16    4847  286.63  4893.7  286.89  4945.9  285.25
  4962.5   285.7  4991.1   284.8  5045.7  284.58  5051.9  283.76  5064.4  284.73
  5094.5  285.93  5136.6  285.22  5196.1  287.13  5362.3  289.58  5389.4  289.46
  5425.5  290.47    5448  290.23  5533.8  291.39  5542.8   290.7  5599.6  291.59
#Mann= 3 , 0 , 0
  4499.8     .05       0  4991.1     .03       0  5064.4     .05       0
Bank Sta=4991.1,5064.4
XS Rating Curve= 0 ,0
Exp/Cntr=0.3,0.1

Chan Stop Cuts=-1
Use User Specified Reach Order=0
Composite Channel Slope=5