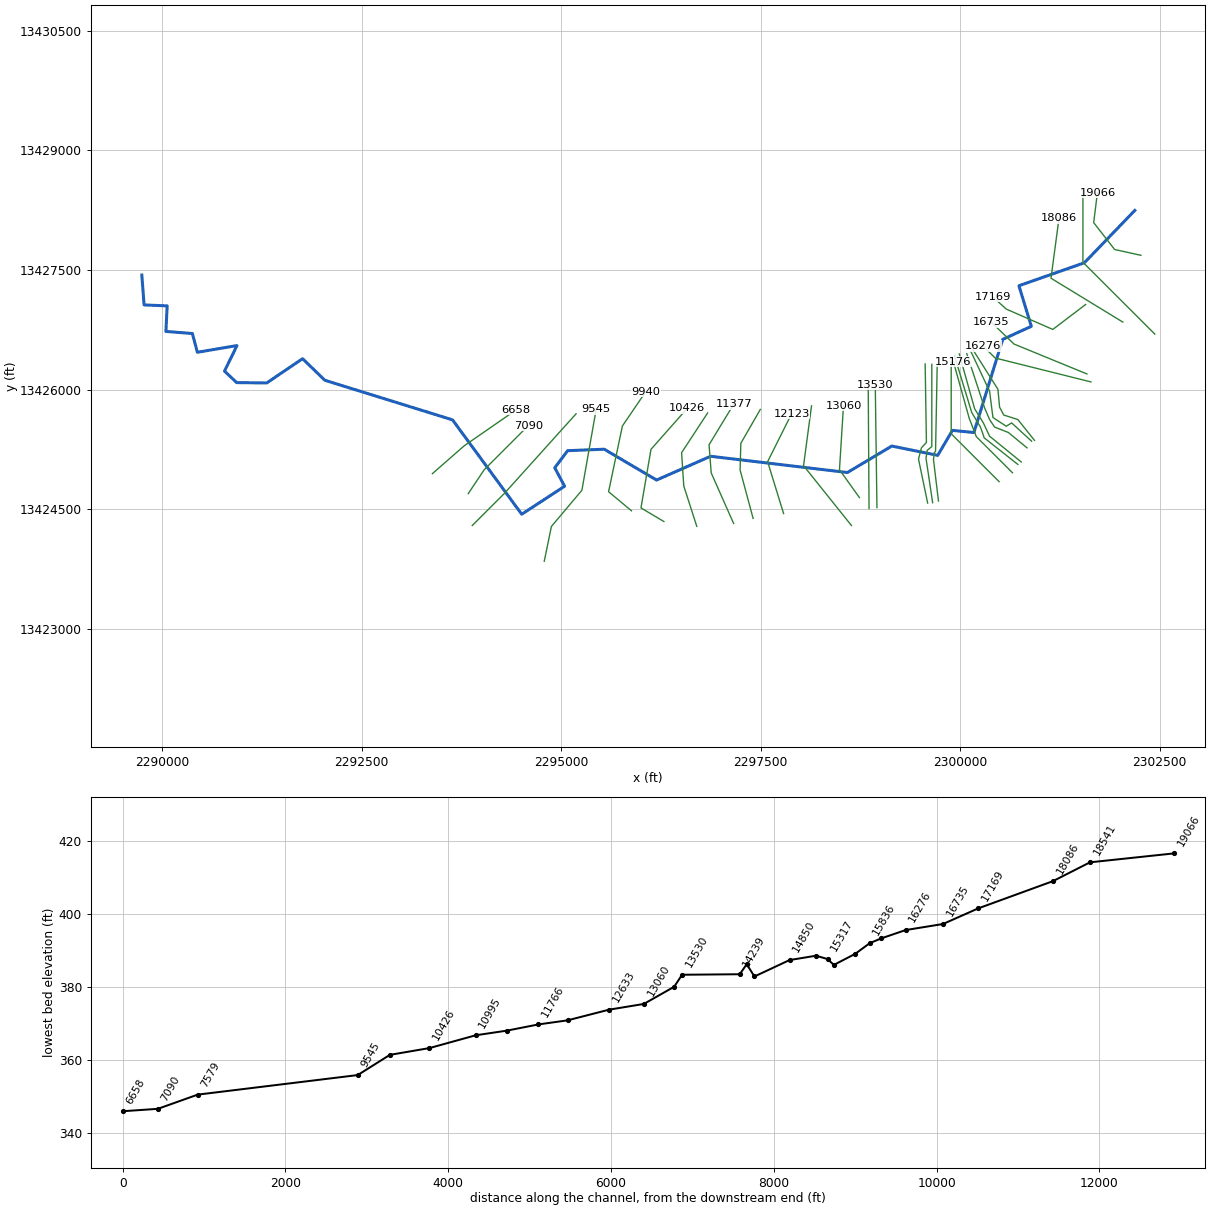
--- UNT030 IN SUCR.prj (project) ---

Proj Title=UNT030 IN SUCR Base Level Engineering
Current Plan=p01
Default Exp/Contr=0.3,0.1
English Units
Geom File=g01
Flow File=f01
Plan File=p01
Y Axis Title=Elevation
X Axis Title(PF)=Main Channel Distance
X Axis Title(XS)=Station
BEGIN DESCRIPTION:
UNT030 IN SUCR
END DESCRIPTION:
DSS Export Rating Curves= 0
DSS Export Rating Curve Sorted= 0
DSS Export Volume Flow Curves= 0
DXF OffsetX= 0
DXF OffsetY= 0
DXF ScaleX= 1
DXF ScaleY= 10

--- UNT030 IN SUCR.p01 (plan) ---

Plan Title=Multiple Run
Short Identifier=Multiple
Geom File=g01
Flow File=f01
Subcritical Flow
K Sum by GR= 0
Std Step Tol= 0.01
Critical Tol= 0.01
Num of Std Step Trials= 20
Max Error Tol= 0.3
Flow Tol Ratio= 0.001
Split Flow NTrial= 30
Split Flow Tol= 0.02
Split Flow Ratio= 0.02
Log Output Level= 0
Friction Slope Method= 1
Unsteady Friction Slope Method= 2
Unsteady Bridges Friction Slope Method= 1
Parabolic Critical Depth
Global Vel Dist=  1 , 1 , 1
Global Log Level= 0
CheckData=True
Encroach Param= -1, 0, 0, 0
BEGIN DESCRIPTION:
Multiple Run
END DESCRIPTION:

--- UNT030 IN SUCR.f01 (steady flow) ---

Flow Title=Multiple
Program Version=4.10
Number of Profiles= 7
Profile Names=10-year,25-year,50-year,1pct_min,100-year,1pct_plu,500-year
River Rch & RM=UNT030 IN SUCR,Reach-1         ,19066
     443     616     759     684     925    1251    1378
River Rch & RM=UNT030 IN SUCR,Reach-1         ,15980
     813    1172    1478    1361    1840    2489    2865
River Rch & RM=UNT030 IN SUCR,Reach-1         ,14419
     813    1172    1478    1361    1840    2489    2865
River Rch & RM=UNT030 IN SUCR,Reach-1         ,13433
     837    1207    1523    1404    1898    2567    2961
River Rch & RM=UNT030 IN SUCR,Reach-1         ,12123
    1045    1521    1931    1789    2419    3271    3812
River Rch & RM=UNT030 IN SUCR,Reach-1         ,9545
    1400    2063    2640    2462    3329    4502    5317
River Rch & RM=UNT030 IN SUCR,Reach-1         ,7579
    1400    2063    2640    2462    3329    4502    5317
River Rch & RM=UNT030 IN SUCR,Reach-1         ,206
    4762    7309    9619    9189   12427   16806   20844
Boundary for River Rch & Prof#=UNT030 IN SUCR,Reach-1         , 1
Up Type= 0
Dn Type= 3
Dn Slope=0.0091
Boundary for River Rch & Prof#=UNT030 IN SUCR,Reach-1         , 2
Up Type= 0
Dn Type= 3
Dn Slope=0.0091
Boundary for River Rch & Prof#=UNT030 IN SUCR,Reach-1         , 3
Up Type= 0
Dn Type= 3
Dn Slope=0.0091
Boundary for River Rch & Prof#=UNT030 IN SUCR,Reach-1         , 4
Up Type= 0
Dn Type= 3
Dn Slope=0.0091
Boundary for River Rch & Prof#=UNT030 IN SUCR,Reach-1         , 5
Up Type= 0
Dn Type= 3
Dn Slope=0.0091
Boundary for River Rch & Prof#=UNT030 IN SUCR,Reach-1         , 6
Up Type= 0
Dn Type= 3
Dn Slope=0.0091
Boundary for River Rch & Prof#=UNT030 IN SUCR,Reach-1         , 7
Up Type= 0
Dn Type= 3
Dn Slope=0.0091
DSS Import GetInterval= 0
DSS Import GetPeak= 0
DSS Import FillOption= 0

--- UNT030 IN SUCR.g01 (geometry) ---

Geom Title=Existing Conditions
Program Version=4.10

River Reach=UNT030 IN SUCR  ,Reach-1
Reach XY= 30
      2302187.72     13428246.85      2301555.49     13427590.39
      2300735.72     13427302.55      2300891.53     13426793.94
      2300532.81      13426630.1      2300172.04      13425462.4
      2299902.94     13425489.53      2299719.09     13425176.63
        2299143.     13425292.77      2298586.97     13424961.02
      2296873.32     13425164.69      2296196.65      13424866.7
      2295540.51     13425253.25        2295083.       13425235.
      2294920.65     13425020.87      2295044.13     13424788.92
      2294507.03     13424437.84      2293640.26     13425621.19
      2292040.43     13426117.65      2291761.72     13426388.17
      2291312.42       13426084.      2290936.26     13426088.13
      2290783.48     13426232.23      2290939.94     13426552.25
      2290443.46     13426468.47       2290381.4     13426703.76
      2290049.63      13426729.8      2290065.26     13427050.11
      2289776.19     13427062.09      2289747.72     13427436.85

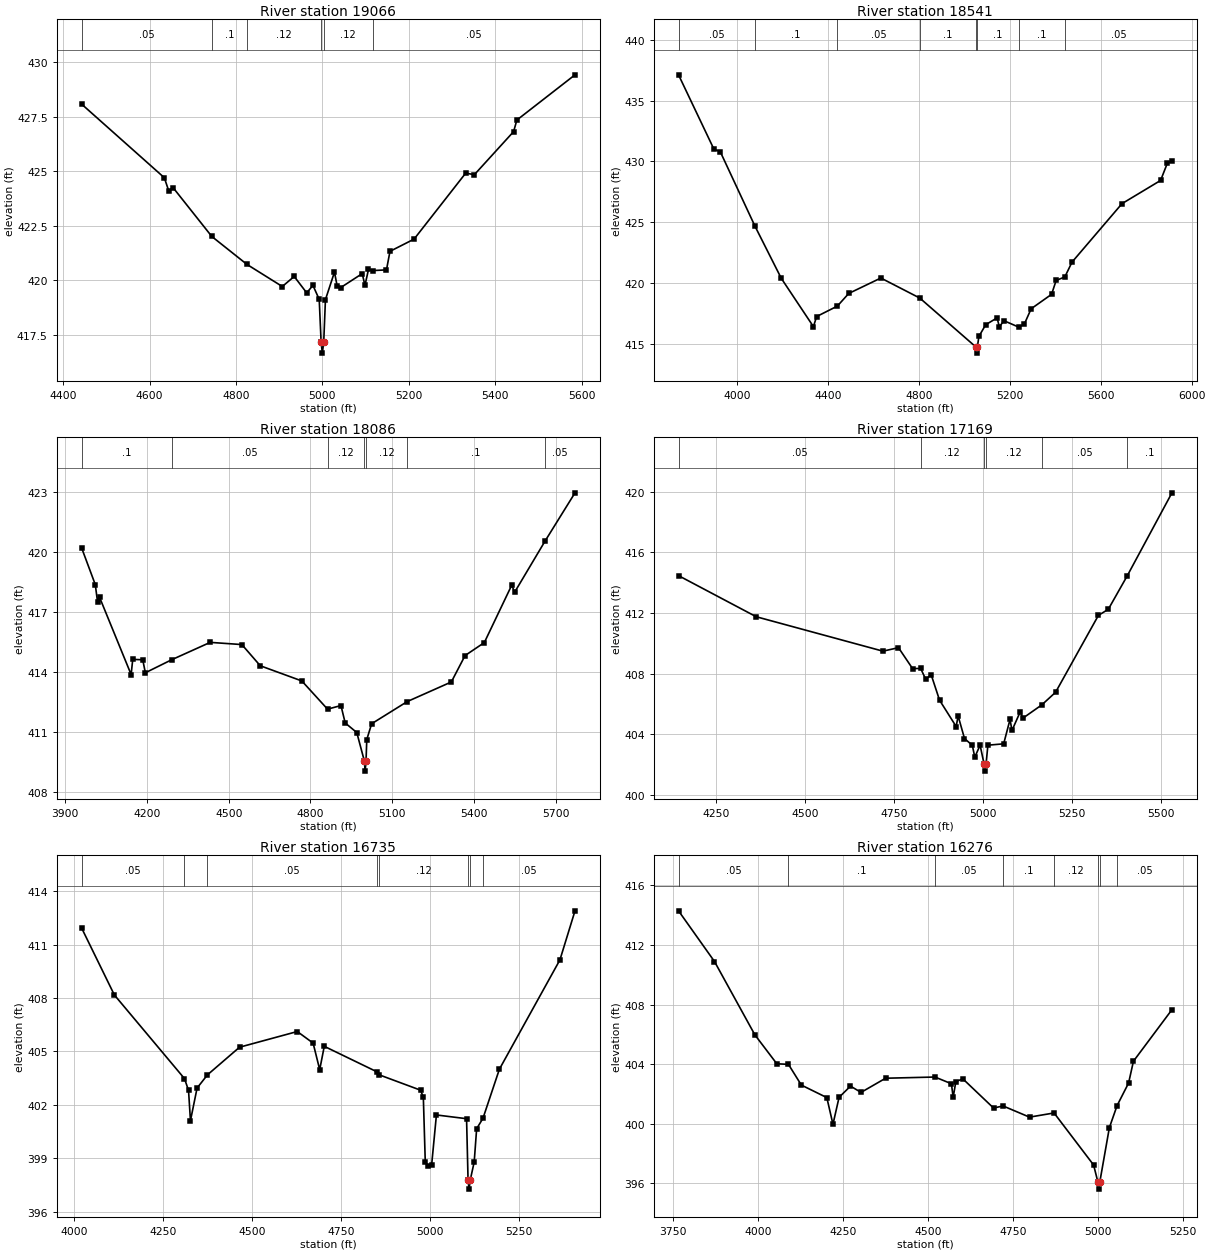
Type RM Length L Ch R = 1 ,19066   ,1031,1031,1031
BEGIN DESCRIPTION:
UNT030 IN SUCR 34.0
END DESCRIPTION:
XS GIS Cut Line= 4
      2302264.59     13427684.02      2301934.74     13427756.94
      2301672.58     13428093.74      2301718.95     13428467.86
#Sta/Elev= 30
  4442.8  428.07  4634.2   424.7  4644.4   424.1  4654.7  424.24  4744.1  422.01
  4825.5  420.73  4907.2  419.72  4934.7  420.18  4963.6  419.43  4978.1  419.77
  4992.6  419.13    4997  417.17  4999.8  416.67    5003  417.17    5007  419.12
  5027.9  420.38  5034.2  419.73  5042.3  419.67  5092.1  420.31  5098.4  419.77
  5106.6   420.5  5116.3  420.45  5148.2  420.48  5156.3  421.33  5212.1  421.89
  5331.5  424.91  5351.6  424.84  5442.3  426.81  5449.9  427.34  5584.4  429.41
#Mann= 6 ,-1 , 0
  4442.8     .05       0  4744.1      .1       0  4825.5     .12       0
    4997     .07       0    5003     .12       0  5116.3     .05       0
Bank Sta=4997,5003
XS Rating Curve= 0 ,0
Exp/Cntr=0.3,0.1

Type RM Length L Ch R = 1 ,18541   ,455,455,455
BEGIN DESCRIPTION:
UNT030 IN SUCR 33.0
END DESCRIPTION:
XS GIS Cut Line= 3
      2302437.73     13426696.85      2301537.72     13427596.85
      2301537.72     13428496.85
#Sta/Elev= 30
  3740.4  437.12    3896  431.01  3924.3  430.79  4076.9  424.67    4193  420.37
  4334.4   416.4  4348.5  417.23  4439.8  418.09  4489.9  419.13  4631.4   420.4
  4802.9  418.75  5050.2  414.72    5053  414.22  5056.2  414.72  5063.2   415.6
  5093.2  416.56  5143.2  417.12  5153.2  416.38  5173.2  416.89  5238.5  416.36
  5263.2  416.61  5293.2  417.87  5383.2  419.06  5403.2   420.2  5441.5  420.49
  5473.2  421.71  5693.2  426.52  5863.2  428.43  5893.2  429.86  5913.2  430.02
#Mann= 8 ,-1 , 0
  3740.4     .05       0  4076.9      .1       0  4439.8     .05       0
  4802.9      .1       0  5050.2     .07       0  5056.2      .1       0
  5238.5      .1       0  5441.5     .05       0
Bank Sta=5050.2,5056.2
XS Rating Curve= 0 ,0
Exp/Cntr=0.3,0.1

Type RM Length L Ch R = 1 ,18086   ,917,917,917
BEGIN DESCRIPTION:
UNT030 IN SUCR 32.0
END DESCRIPTION:
XS GIS Cut Line= 3
      2302037.72     13426846.85      2301137.72     13427396.85
      2301237.72     13428146.87
#Sta/Elev= 30
  3959.8  420.22  4010.1  418.38  4018.4  417.51  4025.6  417.75  4141.7  413.88
  4147.6  414.64  4184.3  414.62  4193.9  413.97  4290.4  414.62    4432  415.49
  4548.2  415.38  4615.8  414.32  4768.4  413.56  4862.7  412.15    4912  412.33
  4927.5  411.46  4970.1  410.98    4998  409.55  5000.7  409.05    5004  409.55
  5006.8  410.63  5024.6  411.42  5155.4  412.53  5317.2  413.51  5367.6  414.83
  5438.3  415.48  5539.2  418.36  5549.2  417.99  5661.4  420.56  5771.2  422.97
#Mann= 7 ,-1 , 0
  3959.8      .1       0  4290.4     .05       0  4862.7     .12       0
    4998     .07       0    5004     .12       0  5155.4      .1       0
  5661.4     .05       0
Bank Sta=4998,5004
XS Rating Curve= 0 ,0
Exp/Cntr=0.3,0.1

Type RM Length L Ch R = 1 ,17169   ,434,434,434
BEGIN DESCRIPTION:
UNT030 IN SUCR 31.0
END DESCRIPTION:
XS GIS Cut Line= 4
      2301571.74     13427067.42      2301160.26     13426754.91
      2300576.93     13427010.12      2300405.05     13427166.38
#Sta/Elev= 30
  4144.3  414.47  4362.5  411.76  4718.3  409.49    4762  409.72  4801.6  408.34
  4824.3  408.35  4838.4  407.64  4853.9  407.93  4877.3  406.26    4924  404.52
  4929.5  405.22  4947.4  403.73  4969.4  403.28  4976.3   402.5  4991.2  403.29
  5002.1  402.08  5004.9  401.58  5008.1  402.08  5013.1  403.29  5057.4  403.38
  5075.3  404.99  5080.7  404.26  5104.1   405.5  5111.3  405.07  5164.6  405.95
  5203.2  406.78  5323.5  411.85  5351.2  412.25  5404.5  414.46    5530  419.93
#Mann= 6 ,-1 , 0
  4144.3     .05       0  4824.3     .12       0  5002.1     .07       0
  5008.1     .12       0  5164.6     .05       0  5404.5      .1       0
Bank Sta=5002.1,5008.1
XS Rating Curve= 0 ,0
Exp/Cntr=0.3,0.1

Type RM Length L Ch R = 1 ,16735   ,459,459,459
BEGIN DESCRIPTION:
UNT030 IN SUCR 30.0
END DESCRIPTION:
XS GIS Cut Line= 3
      2301587.71     13426196.86      2300674.99      13426571.4
       2300387.7     13426846.87
#Sta/Elev= 30
  4021.6  411.93  4113.6  408.17  4310.3  403.48  4321.7  402.82  4327.1  401.12
  4345.7  402.95  4374.8  403.69  4464.8  405.24  4626.9  406.12  4671.3  405.47
  4689.8  403.98  4702.6  405.29  4850.4  403.86  4855.5   403.7  4972.8  402.83
  4980.6  402.43    4986  398.82  4994.4  398.57    5004  398.66  5017.3  401.44
  5101.9  401.23  5106.1  397.78  5108.9  397.28  5112.1  397.78  5123.3   398.8
  5130.2  400.67  5147.9  401.25  5194.1  404.01  5363.9  410.14  5406.2  412.89
#Mann= 8 ,-1 , 0
  4021.6     .05       0  4310.3      .1       0  4374.8     .05       0
  4850.4      .1       0  4855.5     .12       0  5106.1     .07       0
  5112.1     .12       0  5147.9     .05       0
Bank Sta=5106.1,5112.1
XS Rating Curve= 0 ,0
Exp/Cntr=0.3,0.1

Type RM Length L Ch R = 1 ,16276   ,296,296,296
BEGIN DESCRIPTION:
UNT030 IN SUCR 29.0
END DESCRIPTION:
XS GIS Cut Line= 3
      2301637.68     13426096.86      2300437.72     13426396.85
      2300287.74     13426546.84
#Sta/Elev= 30
  3767.5  414.29  3873.1  410.89  3991.7  405.97  4056.1  404.03  4090.3  403.99
  4128.2   402.6    4203  401.76    4221  399.97    4239  401.78  4272.5  402.53
  4303.5  402.11  4375.6  403.06  4520.5  403.14  4568.9  402.69    4574  401.77
  4581.8  402.83  4602.4  403.02  4692.6  401.06  4720.5   401.2  4798.2  400.45
  4870.3  400.73  4986.4  397.24  4998.8  396.12  5001.6  395.62  5004.8  396.12
  5032.7  399.74  5055.3  401.22  5089.2  402.74  5103.4   404.2  5216.5  407.66
#Mann= 8 ,-1 , 0
  3767.5     .05       0  4090.3      .1       0  4520.5     .05       0
  4720.5      .1       0  4870.3     .12       0  4998.8     .07       0
  5004.8     .12       0  5055.3     .05       0
Bank Sta=4998.8,5004.8
XS Rating Curve= 0 ,0
Exp/Cntr=0.3,0.1

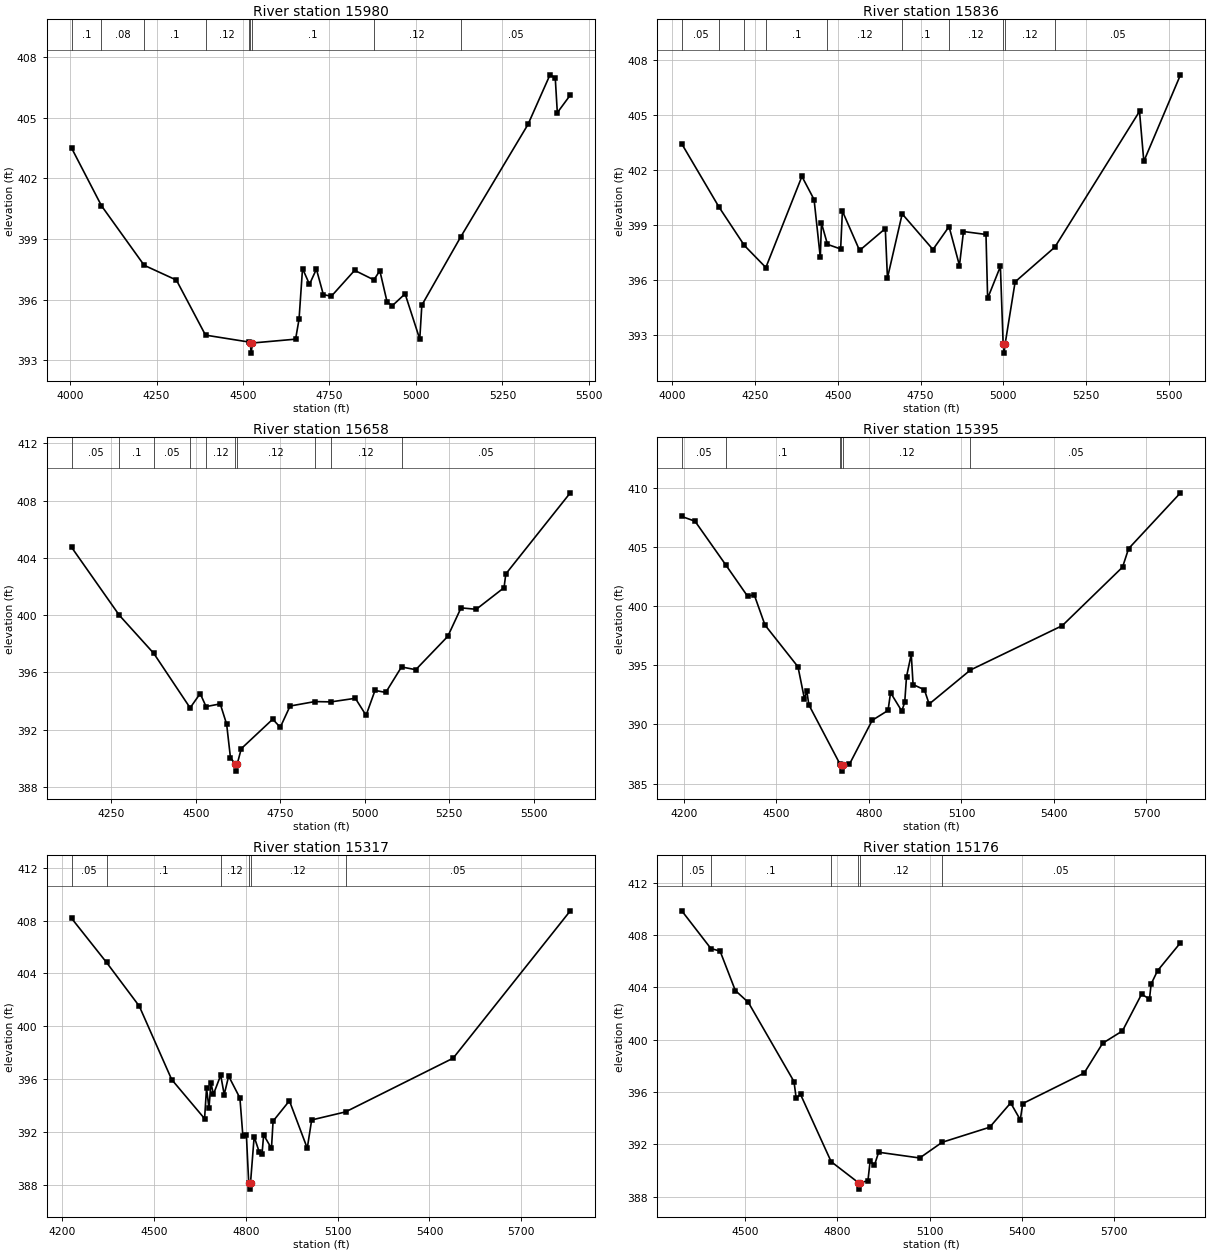
Type RM Length L Ch R = 1 ,15980   ,144,144,144
BEGIN DESCRIPTION:
Mapping XS c57fbb7e
END DESCRIPTION:
XS GIS Cut Line= 6
      2300931.11     13425364.28      2300722.76      13425624.7
      2300545.68       13425682.       2300493.6     13425780.95
      2300472.76     13426004.91      2300160.24     13426499.74
#Sta/Elev= 30
  4004.5  403.49  4090.9  400.64  4214.3   397.7  4307.4  396.97  4391.6  394.25
  4516.5  393.91    4521  393.86  4523.7  393.36    4527  393.86    4652  394.05
    4662  395.03  4672.1  397.54  4692.2  396.76  4712.2  397.51  4732.3  396.25
  4755.4  396.17  4822.7  397.45  4878.3  396.98  4895.6  397.43  4916.8  395.87
  4932.1  395.71  4968.6  396.29    5011  394.05    5017  395.73    5129  399.09
  5323.9  404.66  5387.5  407.11  5402.7  406.96  5408.7  405.24  5446.2  406.11
#Mann= 9 ,-1 , 0
  4004.5      .1       0  4090.9     .08       0  4214.3      .1       0
  4391.6     .12       0  4516.5      .1       0    4521     .07       0
    4527      .1       0  4878.3     .12       0    5129     .05       0
Bank Sta=4521,4527
XS Rating Curve= 0 ,0
Exp/Cntr=0.3,0.1

Type RM Length L Ch R = 1 ,15836   ,178,178,178
BEGIN DESCRIPTION:
UNT030 IN SUCR 28.0
END DESCRIPTION:
XS GIS Cut Line= 6
      2300894.66     13425353.85      2300644.64     13425583.04
      2300576.93     13425541.37      2300410.26     13425650.75
       2300368.6     13425978.87      2300134.21     13426478.89
#Sta/Elev= 30
  4029.3  403.42  4141.7  399.98  4218.3  397.89  4283.1  396.69    4392  401.65
  4428.7  400.39  4447.5  397.24    4451  399.11  4469.2  397.95  4508.9   397.7
  4514.2  399.76  4566.1  397.62  4643.7  398.81  4650.2  396.12  4694.7  399.61
  4787.6  397.67  4836.2  398.92  4867.6   396.8  4879.8  398.65  4947.7  398.49
  4952.7  395.01  4991.2  396.75  4999.5  392.53  5002.3  392.03  5005.5  392.53
  5035.7  395.91  5155.6   397.8  5411.2  405.19  5424.2  402.47  5534.9  407.18
#Mann= 10 ,-1 , 0
  4029.3     .05       0  4141.7     .08       0  4218.3     .05       0
  4283.1      .1       0  4469.2     .12       0  4694.7      .1       0
  4836.2     .12       0  4999.5     .07       0  5005.5     .12       0
  5155.6     .05       0
Bank Sta=4999.5,5005.5
XS Rating Curve= 0 ,0
Exp/Cntr=0.3,0.1

Type RM Length L Ch R = 1 ,15658   ,263,263,263
BEGIN DESCRIPTION:
Mapping XS 22ba017c
END DESCRIPTION:
XS GIS Cut Line= 6
      2300837.34     13425270.55      2300602.97     13425463.25
       2300431.1     13425530.95       2300368.6      13425624.7
       2300306.1     13425770.54       2300082.6     13426451.42
#Sta/Elev= 30
  4132.4  404.74  4273.4     400  4375.6  397.33  4483.2  393.52    4513  394.52
  4530.4  393.61  4572.4   393.8  4591.3  392.38  4602.6  390.04  4616.7   389.6
  4619.4   389.1  4622.7   389.6  4634.6  390.67  4727.8  392.73    4750  392.16
  4779.1  393.65  4852.3  393.96  4900.2  393.94  4972.2  394.19    5004     393
  5030.5  394.74  5062.3   394.6  5108.9  396.38  5151.1  396.19  5245.9  398.52
  5285.1  400.51  5330.1  400.41  5412.4  401.92  5417.6  402.88  5608.5  408.55
#Mann= 10 ,-1 , 0
  4132.4     .05       0  4273.4      .1       0  4375.6     .05       0
  4483.2      .1       0  4530.4     .12       0  4616.7     .07       0
  4622.7     .12       0  4852.3      .1       0  4900.2     .12       0
  5108.9     .05       0
Bank Sta=4616.7,4622.7
XS Rating Curve= 0 ,0
Exp/Cntr=0.3,0.1

Type RM Length L Ch R = 1 ,15395   ,78,78,78
BEGIN DESCRIPTION:
Mapping XS 468b96a0
END DESCRIPTION:
XS GIS Cut Line= 5
      2300764.44     13425093.45       2300368.6     13425416.37
      2300290.47     13425583.04       2300181.1     13425760.12
      2299988.38     13426447.67
#Sta/Elev= 30
  4193.1  407.58    4236  407.18  4335.1  403.51  4406.9  400.82  4427.7  400.98
  4462.9   398.4  4569.9  394.87  4590.7  392.18  4598.6  392.81  4605.1  391.66
  4705.2  386.69  4710.9  386.55  4713.6  386.05  4716.9  386.55  4736.7  386.63
  4810.7  390.35  4861.9  391.18  4870.1  392.68  4906.4  391.13    4916  391.86
  4921.8  394.03  4937.2  395.93  4943.1  393.37  4979.8  392.93  4995.2  391.72
  5129.1   394.6  5426.9  398.35  5622.4   403.3  5641.9  404.86  5810.2  409.58
#Mann= 6 ,-1 , 0
  4193.1     .05       0  4335.1      .1       0  4705.2     .12       0
  4710.9     .07       0  4716.9     .12       0  5129.1     .05       0
Bank Sta=4710.9,4716.9
XS Rating Curve= 0 ,0
Exp/Cntr=0.3,0.1

Type RM Length L Ch R = 1 ,15317   ,141,141,141
BEGIN DESCRIPTION:
UNT030 IN SUCR 27.0
END DESCRIPTION:
XS GIS Cut Line= 6
       2300722.8     13425062.18      2300300.89     13425395.54
      2300280.06     13425458.04      2300254.01     13425530.95
      2300144.64     13425713.25      2299931.11     13426416.33
#Sta/Elev= 30
  4231.4  408.17  4345.5  404.83  4452.4  401.52  4558.2  395.96  4665.6     393
    4672   395.3    4680  393.79  4686.4  395.71  4694.5  394.84  4718.3  396.29
  4729.7  394.82  4744.2  396.22    4781  394.56  4790.6  391.71  4802.1  391.77
  4809.7  388.16  4812.4  387.66  4815.7  388.16  4827.5  391.63  4844.4  390.45
  4853.2  390.32  4858.5  391.77    4884  390.74  4889.3  392.81  4942.6  394.35
  5000.9  390.76  5015.3   392.9  5125.9  393.51  5477.3  397.58  5859.8  408.74
#Mann= 6 ,-1 , 0
  4231.4     .05       0  4345.5      .1       0  4718.3     .12       0
  4809.7     .07       0  4815.7     .12       0  5125.9     .05       0
Bank Sta=4809.7,4815.7
XS Rating Curve= 0 ,0
Exp/Cntr=0.3,0.1

Type RM Length L Ch R = 1 ,15176   ,326,326,326
BEGIN DESCRIPTION:
Mapping XS 806279b1
END DESCRIPTION:
XS GIS Cut Line= 4
      2300655.06     13424958.04      2300201.93     13425411.16
      2300113.39     13425640.33      2299915.46      13426348.7
#Sta/Elev= 30
  4294.1  409.85  4388.7  406.97  4418.7  406.77  4468.2  403.76  4510.6  402.85
  4659.1   396.8  4666.1  395.54  4680.3  395.82  4779.9  390.68  4868.2  389.08
    4871  388.58  4874.2  389.08  4899.5  389.21  4906.6  390.71  4920.7  390.41
  4934.4   391.4  5067.9  390.96  5140.9  392.16  5295.5  393.31  5363.8  395.17
    5395  393.88  5403.1  395.12  5602.7  397.45    5663  399.73  5727.3  400.67
  5789.6  403.48  5815.2  403.11  5820.7  404.26  5841.5  405.27  5916.1  407.41
#Mann= 6 ,-1 , 0
  4294.1     .05       0  4388.7      .1       0  4779.9     .12       0
  4868.2     .07       0  4874.2     .12       0  5140.9     .05       0
Bank Sta=4868.2,4874.2
XS Rating Curve= 0 ,0
Exp/Cntr=0.3,0.1

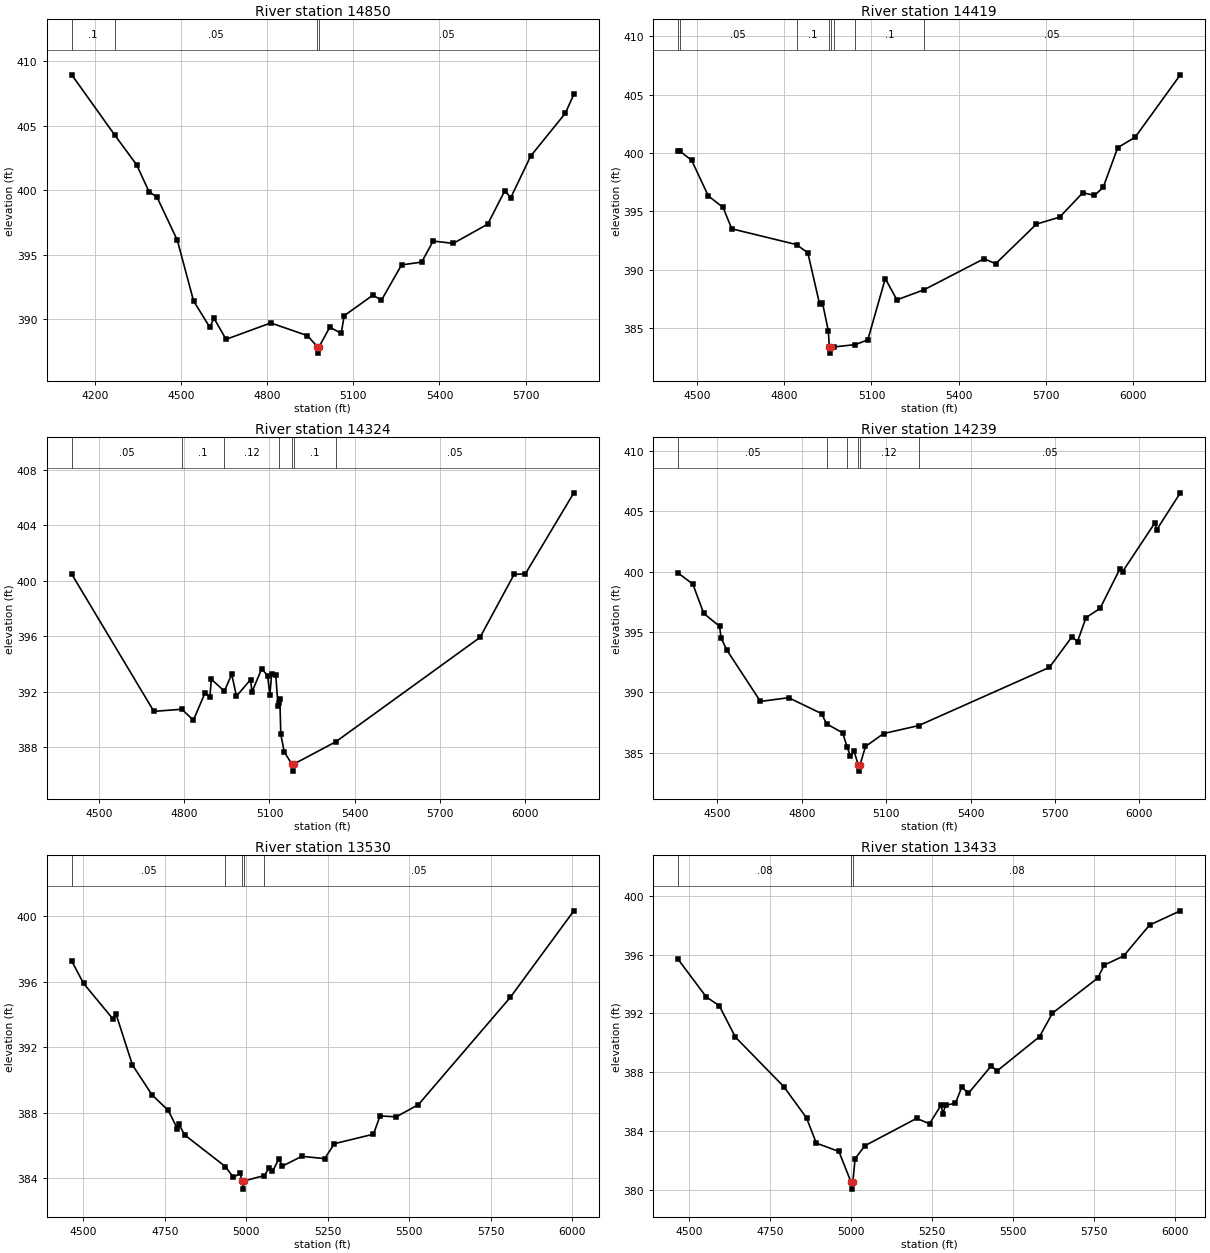
Type RM Length L Ch R = 1 ,14850   ,431,431,431
BEGIN DESCRIPTION:
UNT030 IN SUCR 26.0
END DESCRIPTION:
XS GIS Cut Line= 3
      2300487.74     13424846.83      2299887.72     13425446.85
      2299887.72     13426346.89
#Sta/Elev= 30
  4119.5  408.96  4268.8   404.3  4345.8  401.97  4388.2  399.91  4416.5  399.47
  4487.2  396.13  4543.8  391.42  4600.4  389.38  4614.5  390.09  4656.9  388.45
  4812.5  389.72  4939.8  388.74  4975.1  387.88  4977.8  387.38  4981.1  387.88
  5018.1  389.39  5058.1  388.91  5068.1  390.28  5168.1  391.87  5198.1  391.49
  5268.1  394.22  5338.1  394.44  5378.1  396.07  5448.1  395.89  5568.1  397.38
  5628.1  399.99  5648.1  399.42  5718.1  402.67  5838.1  405.97  5868.1  407.45
#Mann= 4 ,-1 , 0
  4119.5      .1       0  4268.8     .05       0  4975.1     .03       0
  4981.1     .05       0
Bank Sta=4975.1,4981.1
XS Rating Curve= 0 ,0
Exp/Cntr=0.3,0.1

Type RM Length L Ch R = 1 ,14419   ,95,95,95
BEGIN DESCRIPTION:
Mapping XS ec30bb51
END DESCRIPTION:
XS GIS Cut Line= 5
      2299727.97     13424603.89      2299665.47      13425124.7
      2299675.89     13425208.04      2299691.51     13425228.87
      2299712.34     13426322.19
#Sta/Elev= 30
  4434.9  400.19  4439.5  400.18  4481.1  399.37  4538.6  396.32    4589  395.35
  4619.2  393.51    4842  392.16    4881  391.45  4921.3  387.09  4931.4  387.17
  4951.5  384.78    4955  383.37  4957.8  382.87    4961  383.37    4971   383.4
  5044.8   383.6  5087.5  384.01  5147.5  389.25  5187.5  387.43  5280.7  388.29
  5487.5  390.95  5527.5  390.52  5667.6  393.91  5747.6  394.51  5827.6   396.6
  5867.6  396.37  5897.6  397.06  5947.6  400.46  6007.6  401.35    6163  406.69
#Mann= 8 ,-1 , 0
  4434.9      .1       0  4439.5     .05       0    4842      .1       0
    4955     .07       0    4961      .1       0    4971     .12       0
  5044.8      .1       0  5280.7     .05       0
Bank Sta=4955,4961
XS Rating Curve= 0 ,0
Exp/Cntr=0.3,0.1

Type RM Length L Ch R = 1 ,14324   ,85,85,85
BEGIN DESCRIPTION:
UNT030 IN SUCR 25.0
END DESCRIPTION:
XS GIS Cut Line= 5
      2299655.06     13424582.99      2299571.72     13425140.33
      2299587.35     13425239.29      2299644.64     13425286.16
      2299644.64     13426317.42
#Sta/Elev= 30
  4403.5  400.48  4692.7  390.57  4791.3  390.72  4832.1  389.93  4872.5  391.88
  4890.2  391.63  4895.2  392.89  4941.3  392.03    4967  393.25  4983.8  391.67
  5033.4  392.86  5038.5  391.97  5072.7  393.65  5093.5  393.15  5101.4  391.76
  5107.9  393.27  5122.2  393.21  5130.1  390.97  5133.2   391.2  5136.6  391.45
    5140  388.92  5151.9  387.65  5178.9  386.75  5181.7  386.25  5184.9  386.75
  5333.6  388.37  5841.9  395.91  5961.9  400.46  6001.9  400.51  6172.5  406.36
#Mann= 7 ,-1 , 0
  4403.5     .05       0  4791.3      .1       0  4941.3     .12       0
  5133.2      .1       0  5178.9     .07       0  5184.9      .1       0
  5333.6     .05       0
Bank Sta=5178.9,5184.9
XS Rating Curve= 0 ,0
Exp/Cntr=0.3,0.1

Type RM Length L Ch R = 1 ,14239   ,709,709,709
BEGIN DESCRIPTION:
Mapping XS 6fe3607a
END DESCRIPTION:
XS GIS Cut Line= 5
      2299592.56     13424577.82      2299477.97     13425129.91
      2299514.43     13425270.54      2299576.93     13425338.25
      2299561.31     13426322.24
#Sta/Elev= 30
  4360.6  399.88  4412.4  398.98  4451.5  396.54  4507.6  395.48  4512.8  394.52
  4533.2  393.52  4652.9  389.26  4753.1  389.57  4870.3  388.25  4888.3   387.4
  4945.3  386.66  4960.9  385.51    4973  384.71  4985.8  385.14  5000.9  383.99
  5003.7  383.49  5006.9  383.99  5026.4  385.53  5090.9   386.6  5215.5  387.26
  5680.6  392.08  5760.6  394.61  5780.6  394.22  5810.6   396.2  5860.6  396.96
  5930.6  400.21  5940.6     400  6056.4  404.07  6061.4  403.45    6146  406.53
#Mann= 6 ,-1 , 0
  4360.6     .05       0  4888.3      .1       0  4960.9     .12       0
  5000.9     .07       0  5006.9     .12       0  5215.5     .05       0
Bank Sta=5000.9,5006.9
XS Rating Curve= 0 ,0
Exp/Cntr=0.3,0.1

Type RM Length L Ch R = 1 ,13530   ,97,97,97
BEGIN DESCRIPTION:
UNT030 IN SUCR 24.0
END DESCRIPTION:
XS GIS Cut Line= 2
      2298957.14     13424520.58      2298936.31     13426062.03
#Sta/Elev= 30
    4464  397.25  4500.3  395.89  4590.3  393.73  4600.3     394  4650.3  390.92
  4710.3   389.1  4760.3  388.15  4788.2  387.04  4793.2   387.3  4810.3  386.66
  4935.9  384.72  4960.3  384.06  4980.3  384.31  4987.3  383.85  4990.1  383.35
  4993.3  383.85  5055.4  384.18  5070.3  384.65  5080.3  384.44  5100.3   385.2
  5110.3  384.75  5170.3  385.35  5240.4  385.21  5270.4  386.12  5390.4   386.7
  5410.4  387.81  5460.4  387.76  5528.2   388.5  5810.4  395.04  6005.6  400.32
#Mann= 5 ,-1 , 0
    4464     .05       0  4935.9      .1       0  4987.3     .07       0
  4993.3      .1       0  5055.4     .05       0
Bank Sta=4987.3,4993.3
XS Rating Curve= 0 ,0
Exp/Cntr=0.3,0.1

Type RM Length L Ch R = 1 ,13433   ,373,373,373
BEGIN DESCRIPTION:
UNT030 IN SUCR 23.0
END DESCRIPTION:
XS GIS Cut Line= 2
      2298858.18     13424510.14      2298847.77       13426062.
#Sta/Elev= 30
  4465.3  395.67    4552  393.12    4592  392.53    4642  390.39    4792  387.01
    4862  384.89    4892  383.18    4962  382.61    4999  380.55  5001.8  380.05
    5005  380.55    5012  382.12    5042     383    5202  384.86    5242   384.5
    5278  385.77    5283  385.16    5292  385.76    5322  385.89    5342     387
    5362  386.56    5432  388.41    5452  388.11    5582  390.42    5622  392.02
    5762  394.41    5782  395.29    5842  395.91    5922  398.01  6017.2  398.98
#Mann= 3 ,-1 , 0
  4465.3     .08       0    4999     .07       0    5005     .08       0
Bank Sta=4999,5005
XS Rating Curve= 0 ,0
Exp/Cntr=0.3,0.1

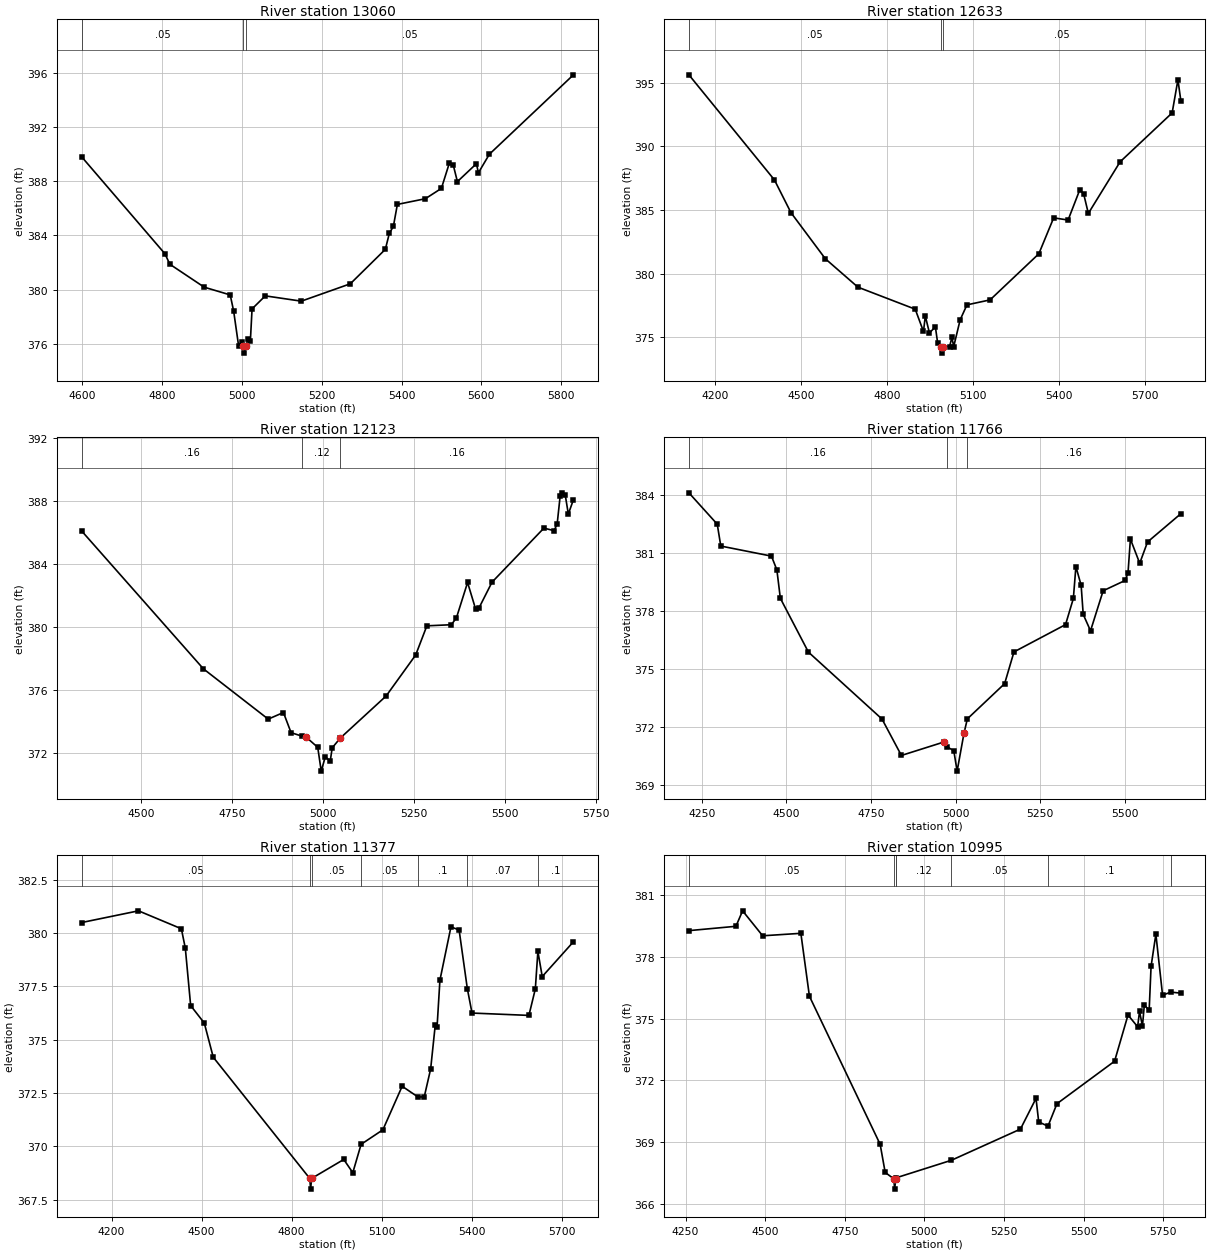
Type RM Length L Ch R = 1 ,13060   ,427,427,427
BEGIN DESCRIPTION:
UNT030 IN SUCR 22.0
END DESCRIPTION:
XS GIS Cut Line= 3
      2298737.69     13424646.89      2298487.72     13424996.85
      2298537.72     13425796.83
#Sta/Elev= 30
  4598.8  389.81  4807.7  382.65    4820  381.88    4906  380.19  4971.1  379.62
  4979.7  378.43    4992  375.89  5000.6  376.18  5003.7  375.83  5006.5  375.33
  5009.7  375.83  5015.3  376.38  5021.5  376.19  5025.8  378.59  5058.9  379.55
  5149.1  379.16  5271.8  380.44  5359.5  382.98  5369.5  384.16  5379.6  384.67
  5389.6  386.29  5459.7  386.71  5499.8  387.47  5519.8  389.34  5529.8  389.16
  5539.9  387.97  5587.5  389.29  5592.5  388.62    5620  389.99  5830.4  395.84
#Mann= 3 ,-1 , 0
  4598.8     .05       0  5003.7     .03       0  5009.7     .05       0
Bank Sta=5003.7,5009.7
XS Rating Curve= 0 ,0
Exp/Cntr=0.3,0.1

Type RM Length L Ch R = 1 ,12633   ,510,510,510
BEGIN DESCRIPTION:
UNT030 IN SUCR 21.0
END DESCRIPTION:
XS GIS Cut Line= 3
      2298637.72     13424296.86      2298037.72     13425046.85
      2298137.72     13425796.86
#Sta/Elev= 30
  4109.6  395.61  4408.1  387.36  4465.8  384.79  4585.8  381.17  4699.5  378.94
  4899.6  377.21  4928.4  375.46  4934.8  376.67  4949.2  375.35    4970  375.82
    4978  374.54  4989.4  374.26  4992.2  373.76  4995.4  374.26  5019.6  374.28
  5027.6  374.99    5034  374.28  5056.5  376.38  5080.2  377.55  5160.9  377.94
  5331.1  381.56  5382.8  384.38  5433.2  384.21  5473.6  386.56  5487.5  386.27
  5503.9  384.73  5614.8  388.78  5796.4  392.62  5816.6  395.22  5826.7  393.59
#Mann= 3 ,-1 , 0
  4109.6     .05       0  4989.4     .03       0  4995.4     .05       0
Bank Sta=4989.4,4995.4
XS Rating Curve= 0 ,0
Exp/Cntr=0.3,0.1

Type RM Length L Ch R = 1 ,12123   ,357,357,357
BEGIN DESCRIPTION:
UNT030 IN SUCR 20.0
END DESCRIPTION:
XS GIS Cut Line= 3
      2297787.72     13424446.84      2297587.72     13425096.85
      2297887.72     13425696.85
#Sta/Elev= 30
  4336.1  386.08  4670.9  377.32  4848.8  374.13  4890.6  374.55  4911.6  373.27
  4942.9  373.04  4953.4  372.98  4984.8  372.34  4994.4  370.83  5005.7  371.75
    5019  371.45  5024.6  372.31  5046.9  372.93  5172.7   375.6  5253.8   378.2
  5284.5  380.05  5351.6  380.12  5365.6  380.55  5396.3   382.8  5418.7  381.09
  5427.1  381.16  5463.4  382.82  5605.9  386.25  5633.9  386.09  5642.3  386.51
  5650.7  388.32  5656.3  388.49  5664.6  388.34    5673  387.14    5687  388.06
#Mann= 3 ,-1 , 0
  4336.1     .16       0  4942.9     .12       0  5046.9     .16       0
Bank Sta=4953.4,5046.9
XS Rating Curve= 0 ,0
Exp/Cntr=0.3,0.1

Type RM Length L Ch R = 1 ,11766   ,389,389,389
BEGIN DESCRIPTION:
UNT030 IN SUCR 19.0
END DESCRIPTION:
XS GIS Cut Line= 4
      2297405.84     13424385.98      2297242.97     13424992.24
      2297252.02     13425327.07      2297496.19     13425752.11
#Sta/Elev= 30
    4212  384.09  4295.7  382.47  4306.2  381.34  4455.8  380.82  4471.8  380.11
  4482.1  378.64    4565  375.86  4782.4   372.4  4839.6  370.52  4964.4  371.21
  4974.4  370.97  4994.4  370.76  5004.2  369.71  5024.4  371.66  5034.4  372.41
  5144.5  374.23  5172.1  375.87  5324.4  377.28  5347.5  378.63    5355  380.28
  5370.5  379.31  5376.6  377.81  5398.2  376.96  5435.5  379.03  5500.2  379.56
  5508.9  379.94    5516   381.7  5543.5  380.45  5566.6  381.55  5664.9  383.01
#Mann= 3 ,-1 , 0
    4212     .16       0  4974.4     .12       0  5034.4     .16       0
Bank Sta=4964.4,5024.4
XS Rating Curve= 0 ,0
Exp/Cntr=0.3,0.1

Type RM Length L Ch R = 1 ,11377   ,382,382,382
BEGIN DESCRIPTION:
UNT030 IN SUCR 18.0
END DESCRIPTION:
XS GIS Cut Line= 4
      2297161.52      13424322.6      2296880.99     13424956.04
      2296853.84     13425308.97      2297161.52     13425815.73
#Sta/Elev= 30
    4100  380.49  4289.9  381.04  4432.8   380.2    4446  379.29  4463.8   376.6
  4509.3  375.78  4539.1  374.18  4860.8   368.5  4863.6     368  4866.8   368.5
  4974.1  369.39  5004.2  368.77  5031.9   370.1  5104.5  370.78  5168.7  372.82
  5221.2  372.32  5242.3  372.32  5263.7  373.63  5279.1   375.7    5285  375.58
  5294.6  377.79  5331.4  380.29  5358.6  380.14    5386  377.39  5401.6  376.25
  5591.2  376.14  5612.6  377.38  5621.1  379.14  5635.6  377.96  5739.6  379.59
#Mann= 7 ,-1 , 0
    4100     .05       0  4860.8     .07       0  4866.8     .05       0
  5031.9     .05       0  5221.2      .1       0    5386     .07       0
  5621.1      .1       0
Bank Sta=4860.8,4866.8
XS Rating Curve= 0 ,0
Exp/Cntr=0.3,0.1

Type RM Length L Ch R = 1 ,10995   ,569,569,569
BEGIN DESCRIPTION:
UNT030 IN SUCR 17.0
END DESCRIPTION:
XS GIS Cut Line= 4
      2296700.02     13424286.35      2296537.12     13424793.15
      2296509.97     13425209.43      2296835.77     13425707.18
#Sta/Elev= 30
  4260.6  379.26  4408.2  379.47  4429.2  380.22  4492.2  379.01  4612.1  379.13
    4639  376.08  4861.1   368.9  4876.8  367.54  4903.9  367.23  4906.6  366.73
  4909.9  367.23  4911.5  367.28  5084.9  368.13  5301.5  369.64  5350.4  371.13
  5358.8  369.99  5387.9  369.78  5416.1  370.87    5597  372.93  5639.2  375.17
  5669.4   374.6  5675.4  375.35  5684.5  374.63  5690.5  375.66  5705.6  375.39
  5711.6  377.53  5726.7  379.09  5747.7  376.13  5773.6  376.28    5805  376.23
#Mann= 7 ,-1 , 0
  4260.6     .05       0  4903.9     .07       0  4909.9     .05       0
  4911.5     .12       0  5084.9     .05       0  5387.9      .1       0
  5773.6     .07       0
Bank Sta=4903.9,4909.9
XS Rating Curve= 0 ,0
Exp/Cntr=0.3,0.1

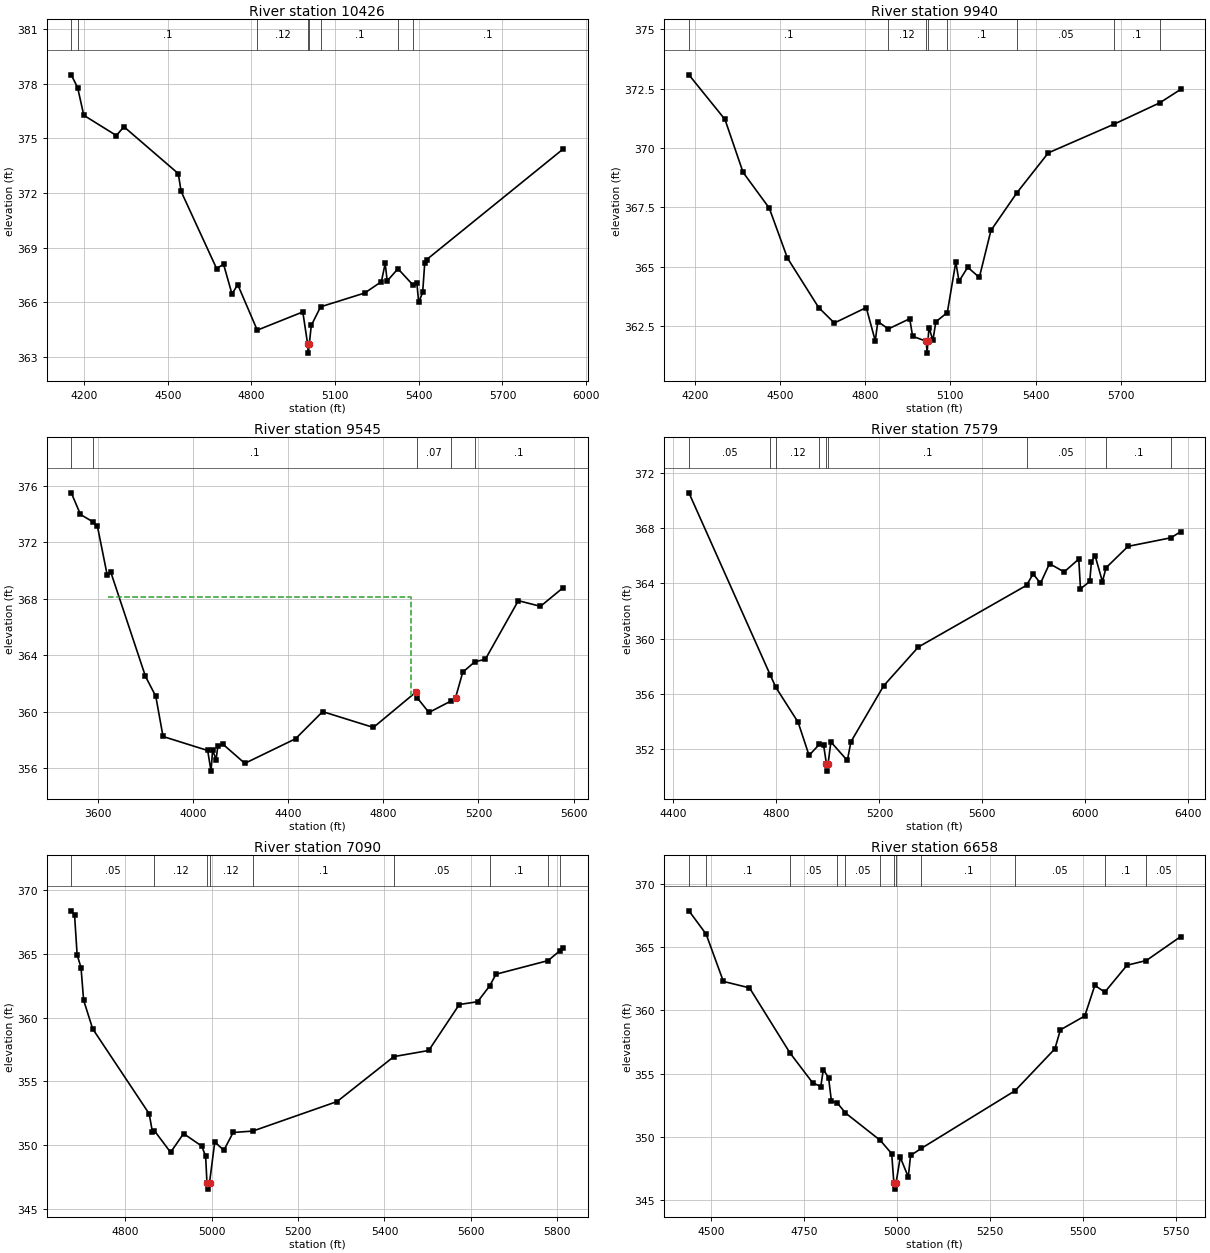
Type RM Length L Ch R = 1 ,10426   ,486,486,486
BEGIN DESCRIPTION:
UNT030 IN SUCR 16.0
END DESCRIPTION:
XS GIS Cut Line= 4
      2296287.76     13424346.83      2296001.09     13424517.46
      2296126.44     13425251.67      2296580.08       13425765.
#Sta/Elev= 30
  4154.1  378.48  4177.1  377.77    4199  376.26  4315.8  375.15    4343  375.63
  4537.8  373.06    4548  372.08  4675.2  367.85  4700.1  368.09  4730.3  366.45
  4750.9  366.97  4820.9  364.47  4984.2  365.47  5001.5  363.71  5004.2  363.21
  5007.5  363.71  5014.6  364.73    5048  365.75  5206.4  366.51  5265.9  367.13
  5279.5  368.13  5286.8  367.17  5325.4  367.84  5379.6  366.94    5393  367.07
  5399.7  365.99  5413.9  366.54  5421.4  368.17  5428.1  368.34  5917.6  374.41
#Mann= 8 ,-1 , 0
  4154.1     .05       0  4177.1      .1       0  4820.9     .12       0
  5001.5     .07       0  5007.5     .12       0    5048      .1       0
  5325.4     .05       0  5379.6      .1       0
Bank Sta=5001.5,5007.5
XS Rating Curve= 0 ,0
Exp/Cntr=0.3,0.1

Type RM Length L Ch R = 1 ,9940    ,395,395,395
BEGIN DESCRIPTION:
Mapping XS 7f790d7b
END DESCRIPTION:
XS GIS Cut Line= 4
      2295881.69     13424481.67      2295595.19     13424720.42
      2295768.29     13425544.16      2296060.08     13425972.91
#Sta/Elev= 30
  4178.7  373.08  4305.7   371.2  4369.5  368.97  4461.9  367.46  4525.7  365.36
  4635.9  363.27  4691.1  362.62  4803.5  363.27  4835.3  361.87  4844.3  362.68
  4881.5  362.37  4956.7   362.8    4967  362.06    5015  361.85  5017.8  361.35
    5021  361.85  5024.5  362.43  5038.5  361.89  5048.7  362.67  5089.2  363.06
  5119.1  365.19  5130.4  364.38  5161.1  364.97    5202  364.54  5242.9  366.52
  5335.1  368.12    5445  369.79  5674.9  370.99  5837.8   371.9    5912  372.47
#Mann= 8 ,-1 , 0
  4178.7      .1       0  4881.5     .12       0    5015     .07       0
    5021     .12       0  5089.2      .1       0  5335.1     .05       0
  5674.9      .1       0  5837.8     .05       0
Bank Sta=5015,5021
XS Rating Curve= 0 ,0
Exp/Cntr=0.3,0.1

Type RM Length L Ch R = 1 ,9545    ,1966,1966,1966
BEGIN DESCRIPTION:
UNT030 IN SUCR 15.0
END DESCRIPTION:
XS GIS Cut Line= 4
      2294789.35     13423848.93      2294878.89     13424284.67
      2295260.91     13424738.32      2295439.87     13425752.43
#Sta/Elev= 30
  3488.2  375.49  3526.9  373.96  3579.8  373.43  3598.4  373.11  3639.2  369.68
  3654.3  369.88  3800.2   362.5  3843.4   361.1    3874  358.25  4061.6  357.26
  4075.7   355.8  4082.5   357.3  4096.8  356.62  4104.5  357.57  4125.4  357.71
  4217.7  356.35    4431  358.09  4544.9  360.01  4758.2  358.89  4937.6   361.4
  4942.7  360.98  4991.7  359.95  5083.1  360.75  5103.4  360.99  5133.9   362.8
  5184.7  363.54  5228.7  363.71  5367.5  367.86  5460.6  367.46  5555.9  368.78
#Mann= 5 ,-1 , 0
  3488.2     .05       0  3579.8      .1       0  4942.7     .07       0
  5083.1     .12       0  5184.7      .1       0
#XS Ineff= 1 ,-1
 3641.57  4916.2368.1408
Permanent Ineff=
       T
Bank Sta=4937.6,5103.4
XS Rating Curve= 0 ,0
Exp/Cntr=0.3,0.1

Type RM Length L Ch R = 1 ,7579    ,489,489,489
BEGIN DESCRIPTION:
UNT030 IN SUCR 14.0
END DESCRIPTION:
XS GIS Cut Line= 3
      2293887.69     13424296.82      2294287.72     13424696.85
      2295187.72     13425696.86
#Sta/Elev= 30
    4460  370.55  4776.2  357.37  4797.6  356.49  4884.3  353.96  4926.7  351.57
    4967  352.37  4983.3  352.31  4994.4  350.93  4997.2  350.43  5000.4  350.93
  5011.6  352.54  5075.4   351.2  5089.6  352.56  5216.7   356.6  5351.2   359.4
  5771.6  363.86  5797.4  364.69  5825.8  364.01    5861  365.43  5917.8  364.83
  5974.6  365.76  5981.3  363.61  6017.2  364.14  6023.9  365.58  6038.1     366
  6066.5  364.13  6080.5  365.13  6165.9  366.68  6332.9   367.3  6371.1  367.75
#Mann= 9 ,-1 , 0
    4460     .05       0  4776.2      .1       0  4797.6     .12       0
    4967      .1       0  4994.4     .07       0  5000.4      .1       0
  5771.6     .05       0  6080.5      .1       0  6332.9     .05       0
Bank Sta=4994.4,5000.4
XS Rating Curve= 0 ,0
Exp/Cntr=0.3,0.1

Type RM Length L Ch R = 1 ,7090    ,432,432,432
BEGIN DESCRIPTION:
UNT030 IN SUCR 13.0
END DESCRIPTION:
XS GIS Cut Line= 3
       2293837.7     13424696.82      2294037.72     13424996.85
      2294587.71     13425546.84
#Sta/Elev= 30
  4675.1  368.39  4682.7  368.08  4688.7  364.93  4697.7  363.93  4703.7  361.37
  4724.7  359.12  4855.4  352.45  4862.9  351.03  4867.7  351.11    4905  349.42
    4935  350.89  4977.1  349.91  4986.1  349.11  4989.1  347.03  4991.9  346.53
  4995.1  347.03  5007.2  350.24  5028.2  349.58  5049.8  350.98  5095.2  351.09
  5290.3  353.41  5421.8  356.94  5502.4  357.42  5573.1  361.03  5615.5  361.25
  5643.6   362.5    5658  363.41  5778.6  364.48  5805.4  365.24  5813.5  365.49
#Mann= 9 ,-1 , 0
  4675.1     .05       0  4867.7     .12       0  4989.1     .07       0
  4995.1     .12       0  5095.2      .1       0  5421.8     .05       0
  5643.6      .1       0  5778.6     .05       0  5805.4      .1       0
Bank Sta=4989.1,4995.1
XS Rating Curve= 0 ,0
Exp/Cntr=0.3,0.1

Type RM Length L Ch R = 1 ,6658    ,485,485,485
BEGIN DESCRIPTION:
UNT030 IN SUCR 12.0
END DESCRIPTION:
XS GIS Cut Line= 3
       2293387.7     13424946.84      2293787.72     13425296.85
      2294437.72     13425746.85
#Sta/Elev= 30
  4440.7  367.87  4486.9  366.03  4533.3  362.29  4603.5  361.78  4712.2  356.64
  4773.4  354.27  4795.2  353.98  4801.9  355.32  4816.1  354.68  4823.7  352.82
  4839.5  352.68  4861.5  351.89  4955.2  349.72  4985.7  348.67  4991.5  346.37
  4994.3  345.87  4997.5  346.37  5008.7  348.39  5030.3  346.83  5036.4  348.53
  5065.8   349.1  5317.3  353.65  5424.3  356.96  5439.1  358.46  5504.7  359.56
  5531.7  361.98  5558.4  361.44  5618.2  363.57    5670  363.94  5762.8  365.84
#Mann= 12 ,-1 , 0
  4440.7     .05       0  4486.9      .1       0  4712.2     .05       0
  4839.5     .12       0  4861.5     .05       0  4955.2     .12       0
  4991.5     .07       0  4997.5     .12       0  5065.8      .1       0
  5317.3     .05       0  5558.4      .1       0    5670     .05       0
Bank Sta=4991.5,4997.5
XS Rating Curve= 0 ,0
Exp/Cntr=0.3,0.1