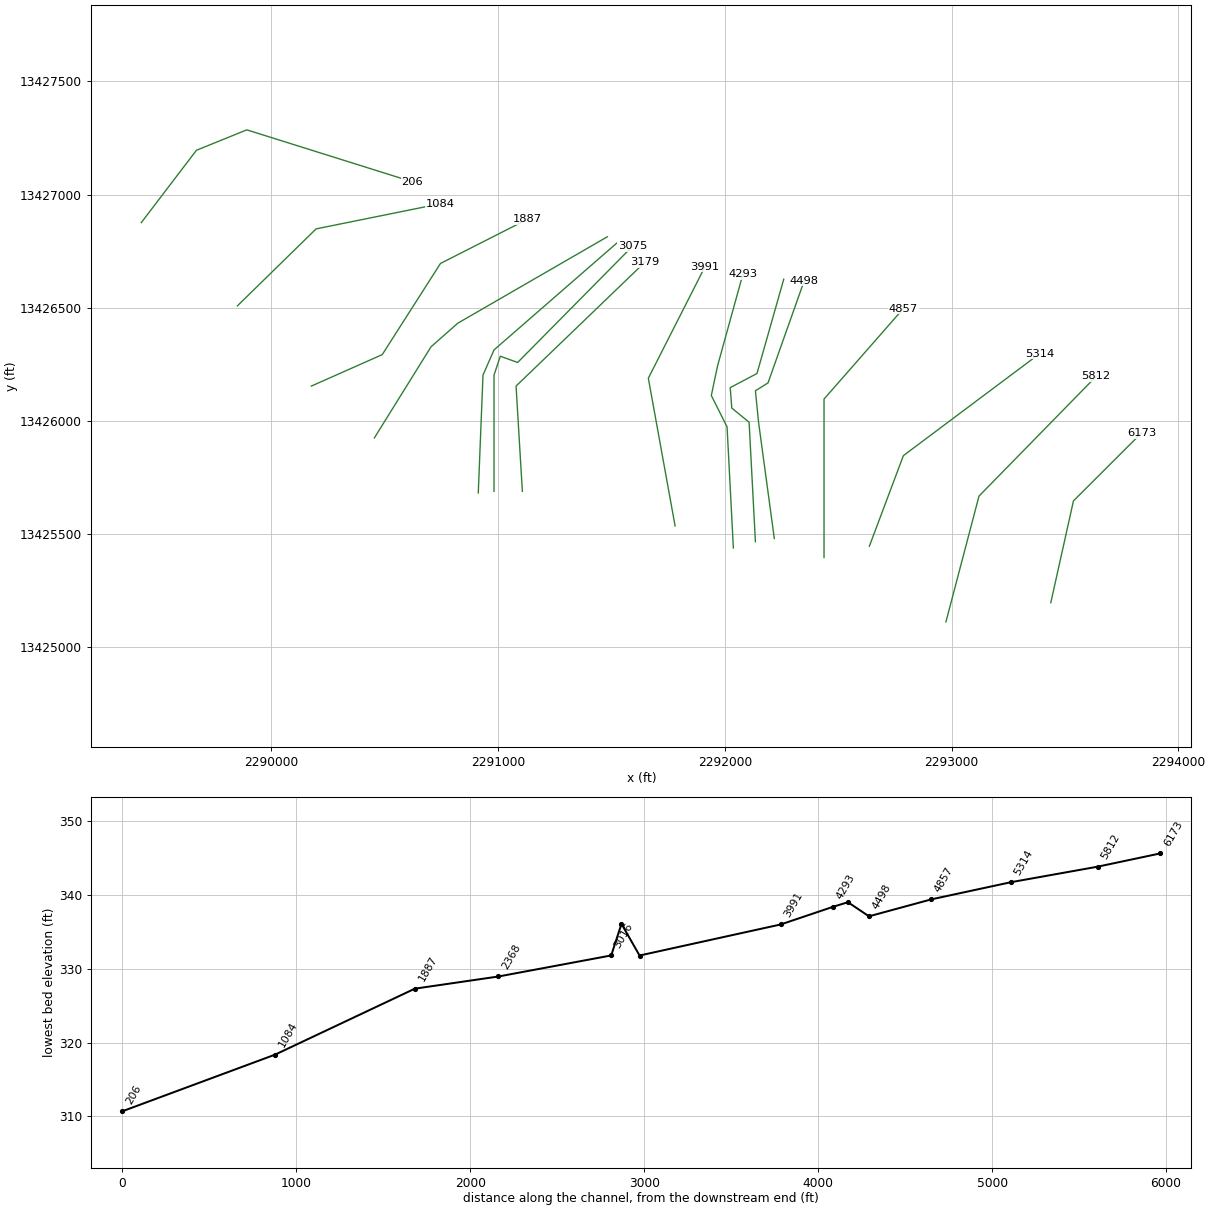
HEC-RAS study UNT030 IN SUCR.prj: UNT030 IN SUCR Base Level Engineering

--- UNT030 IN SUCR.g01 (geometry) --- (continued)

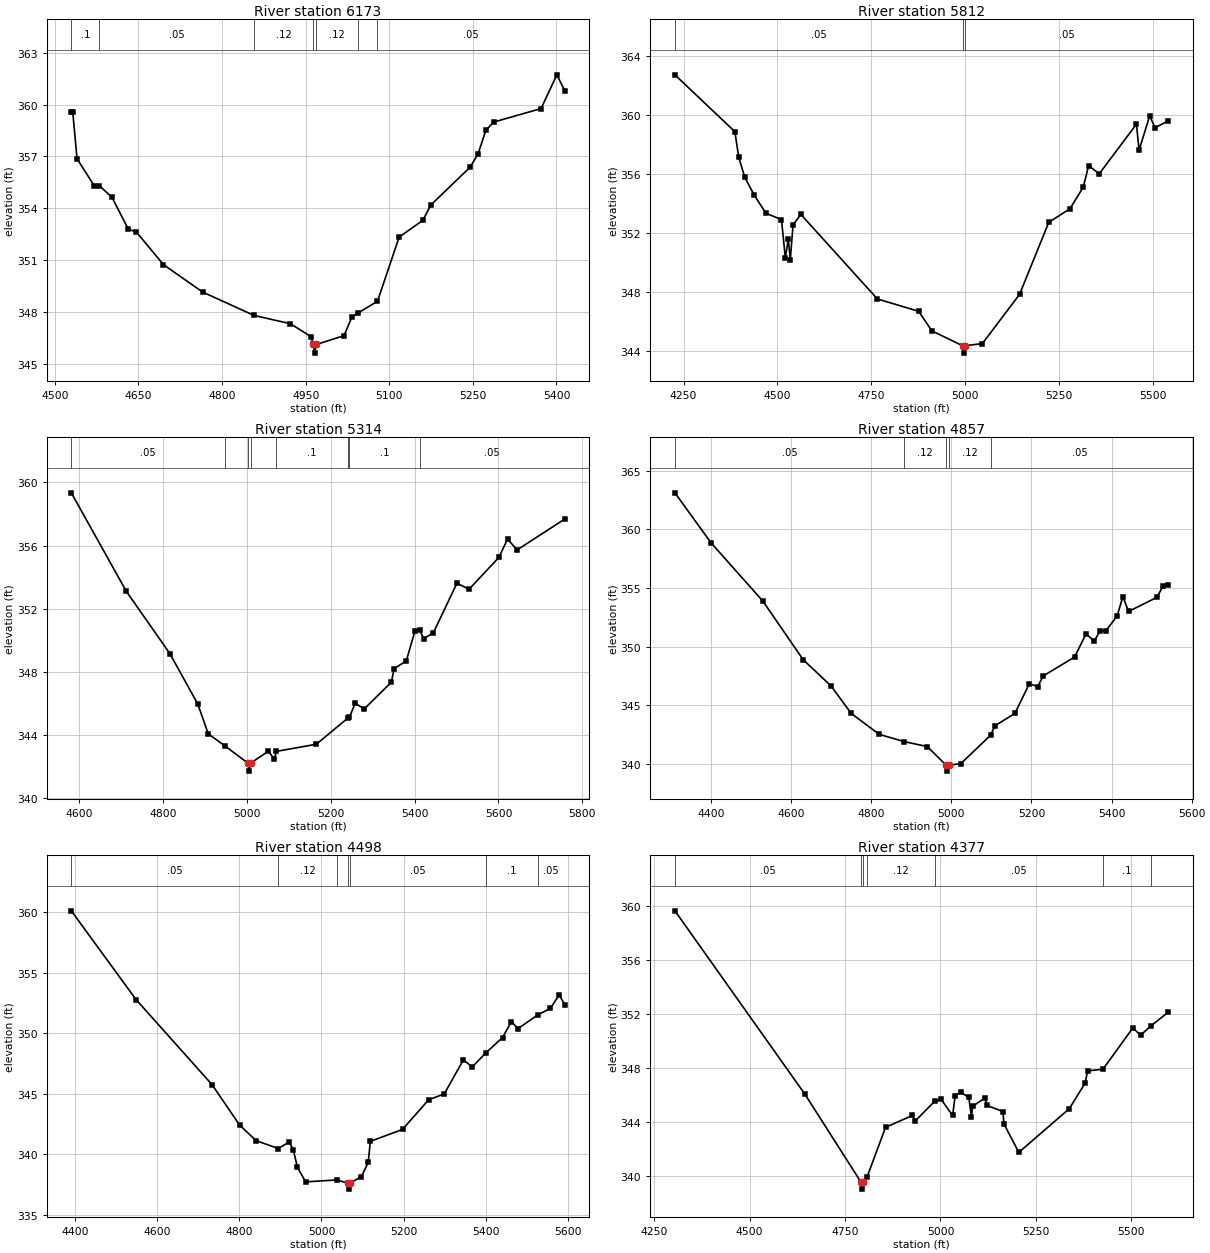
Type RM Length L Ch R = 1 ,6173    ,361,361,361
BEGIN DESCRIPTION:
UNT030 IN SUCR 11.0
END DESCRIPTION:
XS GIS Cut Line= 3
      2293437.73     13425196.88      2293537.72     13425646.85
      2293837.71     13425946.84
#Sta/Elev= 30
  4529.6  359.59  4532.1  359.59  4539.8  356.87  4570.6  355.31    4580  355.31
  4602.6  354.63    4632  352.79  4646.1  352.64  4694.8  350.75  4765.2  349.16
  4857.4  347.81  4922.7  347.33  4959.8  346.58  4963.2  346.13    4966  345.63
  4969.2  346.13  5018.8  346.64    5033  347.72    5044  347.95  5078.9  348.63
  5117.8  352.34  5160.3  353.31  5174.4  354.19  5245.1  356.38  5259.3  357.15
  5273.4  358.52  5287.5  358.99  5372.4  359.77  5400.7  361.72  5414.8  360.81
#Mann= 7 ,-1 , 0
  4529.6      .1       0    4580     .05       0  4857.4     .12       0
  4963.2     .07       0  4969.2     .12       0    5044      .1       0
  5078.9     .05       0
Bank Sta=4963.2,4969.2
XS Rating Curve= 0 ,0
Exp/Cntr=0.3,0.1

Type RM Length L Ch R = 1 ,5812    ,498,498,498
BEGIN DESCRIPTION:
UNT030 IN SUCR 10.0
END DESCRIPTION:
XS GIS Cut Line= 3
      2292975.36     13425112.52       2293121.2     13425668.11
      2293637.74     13426196.87
#Sta/Elev= 30
    4227  362.73  4386.6  358.87  4396.9  357.12    4413  355.77  4438.3  354.55
  4469.3  353.33  4510.6   352.9    4521   350.3  4528.9  351.58  4534.1  350.18
  4541.6  352.55  4562.3  353.25    4766  347.51  4875.8  346.67  4911.3  345.34
    4993  344.33  4995.7  343.83    4999  344.33  5045.6  344.48  5144.6  347.82
  5222.3  352.71  5278.9  353.64  5314.3  355.11  5328.5  356.56  5356.8  356.01
  5455.8  359.38  5462.8  357.61  5491.1  359.95  5505.2  359.13  5540.6  359.61
#Mann= 3 ,-1 , 0
    4227     .05       0    4993     .03       0    4999     .05       0
Bank Sta=4993,4999
XS Rating Curve= 0 ,0
Exp/Cntr=0.3,0.1

Type RM Length L Ch R = 1 ,5314    ,457,457,457
BEGIN DESCRIPTION:
UNT030 IN SUCR 9.0
END DESCRIPTION:
XS GIS Cut Line= 3
      2292637.71     13425446.82      2292787.72     13425846.85
      2293387.69     13426296.83
#Sta/Elev= 30
  4580.8  359.34  4711.7  353.12  4815.8  349.17  4882.6  345.97  4907.5  344.09
  4947.6  343.32  5002.4  342.23  5005.1  341.73  5008.4  342.23  5050.8  342.99
  5065.3  342.49    5070  342.98  5165.3  343.43  5241.1   345.1  5244.5  345.14
    5258  346.02  5279.9  345.67  5344.5  347.36  5350.8  348.21  5379.9   348.7
  5400.8   350.6  5412.3  350.64  5421.6  350.11  5444.5  350.48  5500.8  353.62
  5529.9  353.24  5600.8  355.25  5621.6  356.41  5644.5  355.73    5758  357.68
#Mann= 8 ,-1 , 0
  4580.8     .05       0  4947.6     .12       0  5002.4     .07       0
  5008.4     .12       0    5070      .1       0  5241.1     .05       0
  5244.5      .1       0  5412.3     .05       0
Bank Sta=5002.4,5008.4
XS Rating Curve= 0 ,0
Exp/Cntr=0.3,0.1

Type RM Length L Ch R = 1 ,4857    ,359,359,359
BEGIN DESCRIPTION:
UNT030 IN SUCR 8.0
END DESCRIPTION:
XS GIS Cut Line= 3
      2292437.72     13425396.87      2292437.72     13426096.85
      2292787.72     13426496.86
#Sta/Elev= 30
  4310.2   363.1  4400.2  358.85  4530.2  353.86  4630.2   348.9  4700.2  346.65
  4750.2  344.32  4820.2  342.54  4882.8  341.92  4940.2   341.5  4987.2  339.91
  4989.9  339.41  4993.2  339.91  5023.9  340.05  5097.9  342.46  5109.4  343.28
  5158.7  344.32  5194.8  346.85  5215.7  346.61  5229.9  347.52  5307.7  349.12
  5336.2  351.08  5357.1  350.49  5371.3  351.35  5385.6  351.34    5414  352.62
  5428.3  354.27  5442.5     353  5513.7  354.21  5527.9  355.14  5541.7  355.24
#Mann= 5 ,-1 , 0
  4310.2     .05       0  4882.8     .12       0  4987.2     .07       0
  4993.2     .12       0  5097.9     .05       0
Bank Sta=4987.2,4993.2
XS Rating Curve= 0 ,0
Exp/Cntr=0.3,0.1

Type RM Length L Ch R = 1 ,4498    ,121,121,121
BEGIN DESCRIPTION:
Mapping XS e74d4fda
END DESCRIPTION:
XS GIS Cut Line= 5
      2292218.42     13425480.62      2292148.98      13425994.5
      2292135.09     13426133.39      2292190.65     13426168.11
      2292350.38     13426619.54
#Sta/Elev= 30
  4390.4  360.13  4548.1  352.79  4733.2  345.76  4800.3  342.42  4840.7  341.12
  4894.8  340.47  4921.4  341.01  4931.4  340.37  4941.5   338.9  4961.6  337.71
  5037.2  337.87  5063.9  337.61  5066.7  337.11  5069.9  337.61  5097.6  338.15
    5114  339.33  5119.1  341.06  5197.6  342.05  5261.2   344.5  5299.2  344.98
  5346.1  347.81  5367.3  347.21  5401.5  348.41  5441.5  349.65  5462.8  350.97
  5479.3  350.39  5526.7  351.51  5558.2  352.07  5579.4  353.18  5592.9  352.37
#Mann= 7 ,-1 , 0
  4390.4     .05       0  4894.8     .12       0  5037.2     .05       0
  5063.9     .07       0  5069.9     .05       0  5401.5      .1       0
  5526.7     .05       0
Bank Sta=5063.9,5069.9
XS Rating Curve= 0 ,0
Exp/Cntr=0.3,0.1

Type RM Length L Ch R = 1 ,4377    ,84,84,84
BEGIN DESCRIPTION:
UNT030 IN SUCR 7.0
END DESCRIPTION:
XS GIS Cut Line= 6
      2292135.09     13425466.69      2292107.31      13425994.5
      2292030.92       13426057.      2292023.98     13426147.27
      2292142.04     13426209.77      2292260.09     13426626.42
#Sta/Elev= 30
  4304.4  359.61    4645  346.04  4792.2  339.52    4795  339.02  4798.2  339.52
  4808.1  339.94  4856.1  343.59  4926.4  344.47  4934.1  344.07  4984.5  345.51
  5001.7  345.66  5031.9  344.47  5038.5  345.93  5052.8  346.19  5074.3   345.8
  5081.3  344.36    5084  345.14  5116.7  345.77  5121.7  345.21  5163.8  344.76
  5166.2  343.85  5205.3  341.74  5337.5  344.97  5379.1  346.87  5385.4  347.77
  5425.7  347.89  5503.8  350.94  5524.6  350.41  5550.8  351.09  5596.9  352.11
#Mann= 7 ,-1 , 0
  4304.4     .05       0  4792.2     .03       0  4798.2     .05       0
  4808.1     .12       0  4984.5     .05       0  5425.7      .1       0
  5550.8     .05       0
Bank Sta=4792.2,4798.2
XS Rating Curve= 0 ,0
Exp/Cntr=0.3,0.1

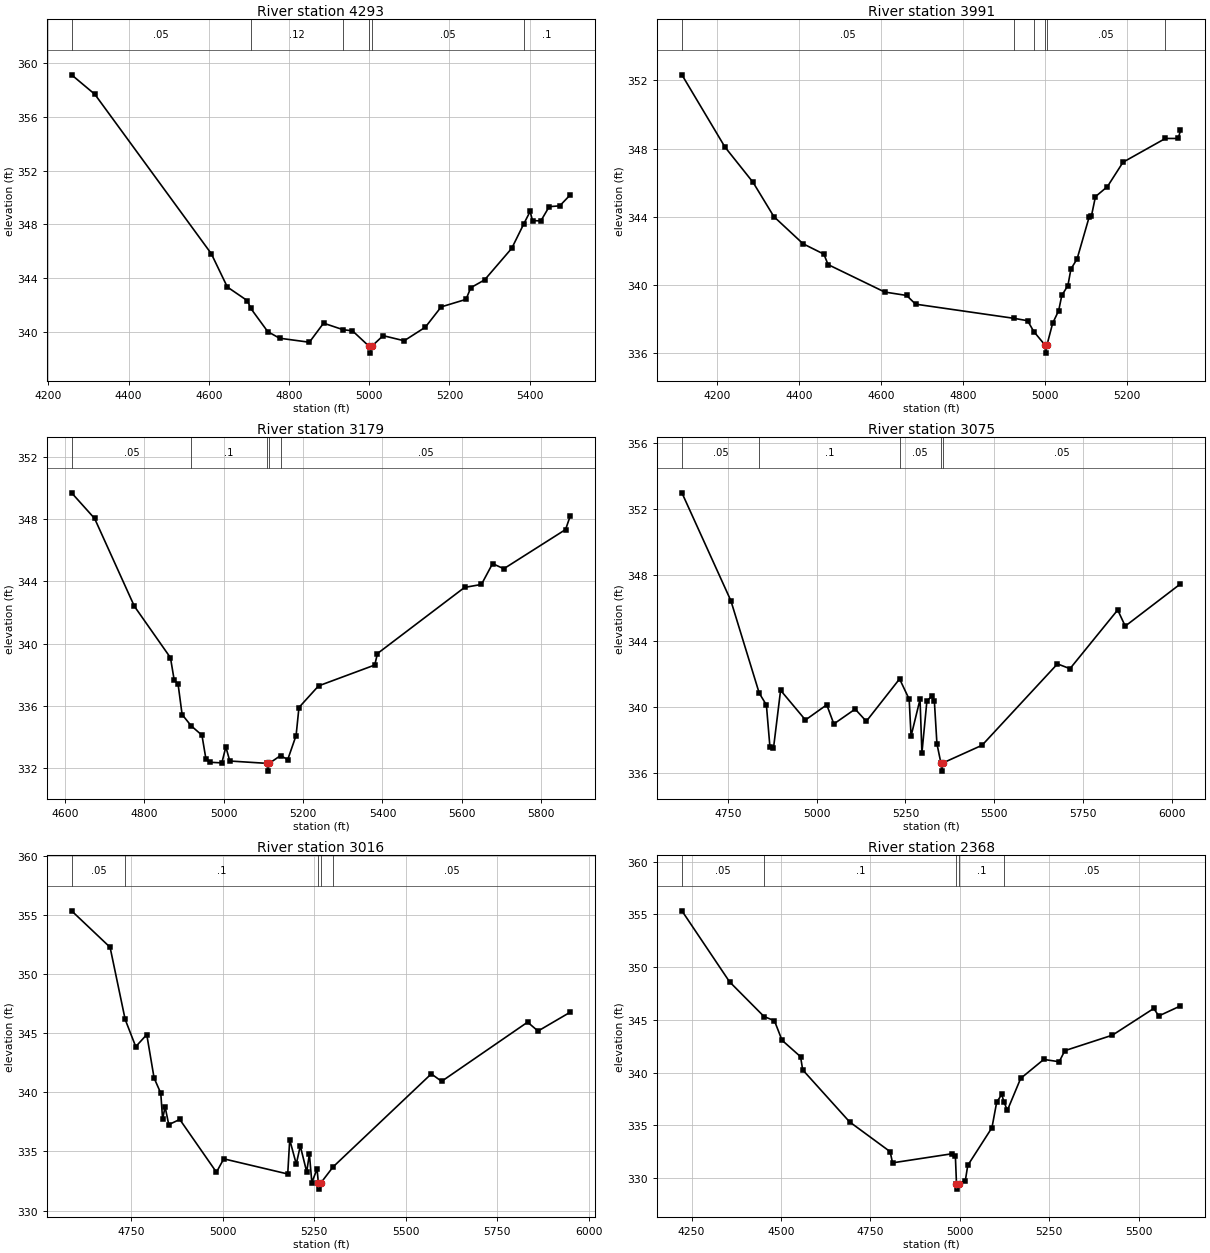
Type RM Length L Ch R = 1 ,4293    ,302,302,302
BEGIN DESCRIPTION:
Mapping XS 7ca75363
END DESCRIPTION:
XS GIS Cut Line= 5
      2292037.87     13425438.96      2292010.09     13425973.66
      2291940.65     13426112.55      2291968.42      13426244.5
      2292079.54      13426647.3
#Sta/Elev= 30
  4257.7  359.12  4315.7  357.67  4606.1  345.81  4646.1  343.33  4696.2  342.31
  4704.3  341.75  4746.9  340.01  4776.3  339.52  4850.7  339.22  4886.1  340.64
  4935.1  340.15  4958.2  340.07  4999.9  338.91  5002.7  338.41  5005.9  338.91
  5034.6  339.71  5087.1  339.33  5139.9  340.34  5179.4  341.85  5241.3  342.41
  5253.3  343.28  5287.7  343.86  5355.4  346.21  5385.6  348.04  5401.2  348.95
  5407.3  348.27    5428  348.25  5448.8  349.31  5475.1  349.37  5501.1  350.18
#Mann= 6 ,-1 , 0
  4257.7     .05       0  4704.3     .12       0  4935.1     .05       0
  4999.9     .03       0  5005.9     .05       0  5385.6      .1       0
Bank Sta=4999.9,5005.9
XS Rating Curve= 0 ,0
Exp/Cntr=0.3,0.1

Type RM Length L Ch R = 1 ,3991    ,812,812,812
BEGIN DESCRIPTION:
UNT030 IN SUCR 6.0
END DESCRIPTION:
XS GIS Cut Line= 3
      2291780.93     13425536.13      2291662.87     13426188.94
      2291912.77      13426681.8
#Sta/Elev= 30
  4114.1  352.32    4219  348.09  4287.6  346.02  4338.4  344.01  4409.5  342.42
  4460.4  341.81  4470.5   341.2  4608.7  339.59  4662.2  339.39  4683.9  338.88
  4923.8  338.05  4957.1  337.91  4972.5  337.27  4998.7  336.51  5001.4  336.01
  5004.7  336.51  5018.3  337.76    5033   338.5  5040.6  339.39  5055.5  339.97
  5062.9  340.94  5077.9  341.53  5107.4  343.99    5113  344.06  5122.7  345.18
  5151.9  345.77    5190   347.2  5293.2  348.59  5324.5  348.59  5330.1  349.06
#Mann= 6 ,-1 , 0
  4114.1     .05       0  4923.8     .12       0  4972.5     .05       0
  4998.7     .03       0  5004.7     .05       0  5293.2      .1       0
Bank Sta=4998.7,5004.7
XS Rating Curve= 0 ,0
Exp/Cntr=0.3,0.1

Type RM Length L Ch R = 1 ,3179    ,104,104,104
BEGIN DESCRIPTION:
Mapping XS d46b6401
END DESCRIPTION:
XS GIS Cut Line= 3
      2291107.31     13425688.99      2291079.54     13426154.22
      2291648.49     13426702.36
#Sta/Elev= 30
  4616.8  349.69  4674.8  348.04  4774.9   342.4  4865.9  339.09  4875.1  337.68
  4885.1  337.39  4895.2  335.44  4918.1  334.71  4945.2  334.11  4955.3  332.57
  4965.3  332.37  4995.3  332.33  5005.4  333.35  5015.4  332.45  5108.7   332.3
  5111.4   331.8  5114.7   332.3  5143.3   332.8  5161.3  332.54  5182.4  334.09
  5189.6  335.89    5239  337.28  5380.5  338.62  5387.4  339.36  5606.9  343.61
  5649.3   343.8  5677.4  345.14  5705.7  344.81  5861.3  347.33  5872.9  348.19
#Mann= 5 ,-1 , 0
  4616.8     .05       0  4918.1      .1       0  5108.7     .07       0
  5114.7      .1       0  5143.3     .05       0
Bank Sta=5108.7,5114.7
XS Rating Curve= 0 ,0
Exp/Cntr=0.3,0.1

Type RM Length L Ch R = 1 ,3075    ,59,59,59
BEGIN DESCRIPTION:
UNT030 IN SUCR 5.0
END DESCRIPTION:
XS GIS Cut Line= 5
      2290982.31     13425688.96      2290982.31     13426202.83
      2291010.09     13426286.16      2291086.48     13426258.39
       2291592.9     13426771.74
#Sta/Elev= 30
  4620.6  352.96  4758.5  346.42  4838.3  340.82  4858.5   340.1  4868.5  337.55
  4878.5  337.48  4898.5  340.99  4968.5  339.19  5028.5  340.11  5048.5  338.95
  5108.5  339.85  5139.9  339.11  5233.6  341.68  5260.6  340.45  5265.9  338.21
  5291.2  340.44  5296.5  337.19  5310.5  340.33  5324.6  340.65  5331.6  340.32
  5338.8  337.75  5349.9  336.59  5352.6  336.09  5355.9  336.59    5466  337.66
  5678.2  342.59  5713.5   342.3  5847.9  345.86  5869.1  344.88  6024.7  347.44
#Mann= 5 ,-1 , 0
  4620.6     .05       0  4838.3      .1       0  5233.6     .05       0
  5349.9     .07       0  5355.9     .05       0
Bank Sta=5349.9,5355.9
XS Rating Curve= 0 ,0
Exp/Cntr=0.3,0.1

Type RM Length L Ch R = 1 ,3016    ,648,648,648
BEGIN DESCRIPTION:
Mapping XS d419360f
END DESCRIPTION:
XS GIS Cut Line= 4
      2290912.87     13425681.97       2290933.7     13426202.83
      2290982.31     13426313.94      2291523.33     13426785.59
#Sta/Elev= 30
  4588.2  355.33  4693.2  352.25  4734.3  346.16  4763.2  343.85  4793.3  344.87
  4813.3   341.2  4831.5  339.92  4836.5  337.73  4843.3  338.76  4853.3  337.26
  4883.3   337.7  4983.4  333.24  5003.4  334.37  5177.9  333.09  5183.3  335.99
  5201.2  333.93  5212.2  335.46  5229.6  333.27    5237  334.77  5243.7  332.37
  5257.9  333.51  5261.6  332.31  5264.3  331.81  5267.6  332.31  5301.7  333.69
  5569.6  341.55  5597.8  340.92  5832.3  345.92  5860.8  345.17  5948.5  346.76
#Mann= 5 ,-1 , 0
  4588.2     .05       0  4734.3      .1       0  5261.6     .07       0
  5267.6      .1       0  5301.7     .05       0
Bank Sta=5261.6,5267.6
XS Rating Curve= 0 ,0
Exp/Cntr=0.3,0.1

Type RM Length L Ch R = 1 ,2368    ,481,481,481
BEGIN DESCRIPTION:
UNT030 IN SUCR 4.0
END DESCRIPTION:
XS GIS Cut Line= 4
      2290454.56     13425925.09      2290704.54     13426327.83
      2290822.59       13426432.      2291482.35     13426813.96
#Sta/Elev= 30
  4223.1  355.33  4356.4   348.6  4452.8  345.31  4481.7  344.92  4502.9  343.07
  4554.7  341.51  4560.8  340.26  4691.9  335.33  4805.2  332.51  4811.9  331.45
  4977.9  332.31  4987.6  332.09  4990.7  329.46  4993.4  328.96  4996.7  329.46
  5015.2  329.73  5022.2  331.21  5089.8  334.78  5103.1   337.2  5117.1  337.93
  5123.7   337.2  5132.9  336.42  5170.1  339.45  5234.7  341.25  5277.8  341.03
  5293.6  342.08  5426.7  343.55  5542.2  346.08  5556.2  345.37  5616.9  346.32
#Mann= 5 ,-1 , 0
  4223.1     .05       0  4452.8      .1       0  4990.7     .07       0
  4996.7      .1       0  5123.7     .05       0
Bank Sta=4990.7,4996.7
XS Rating Curve= 0 ,0
Exp/Cntr=0.3,0.1

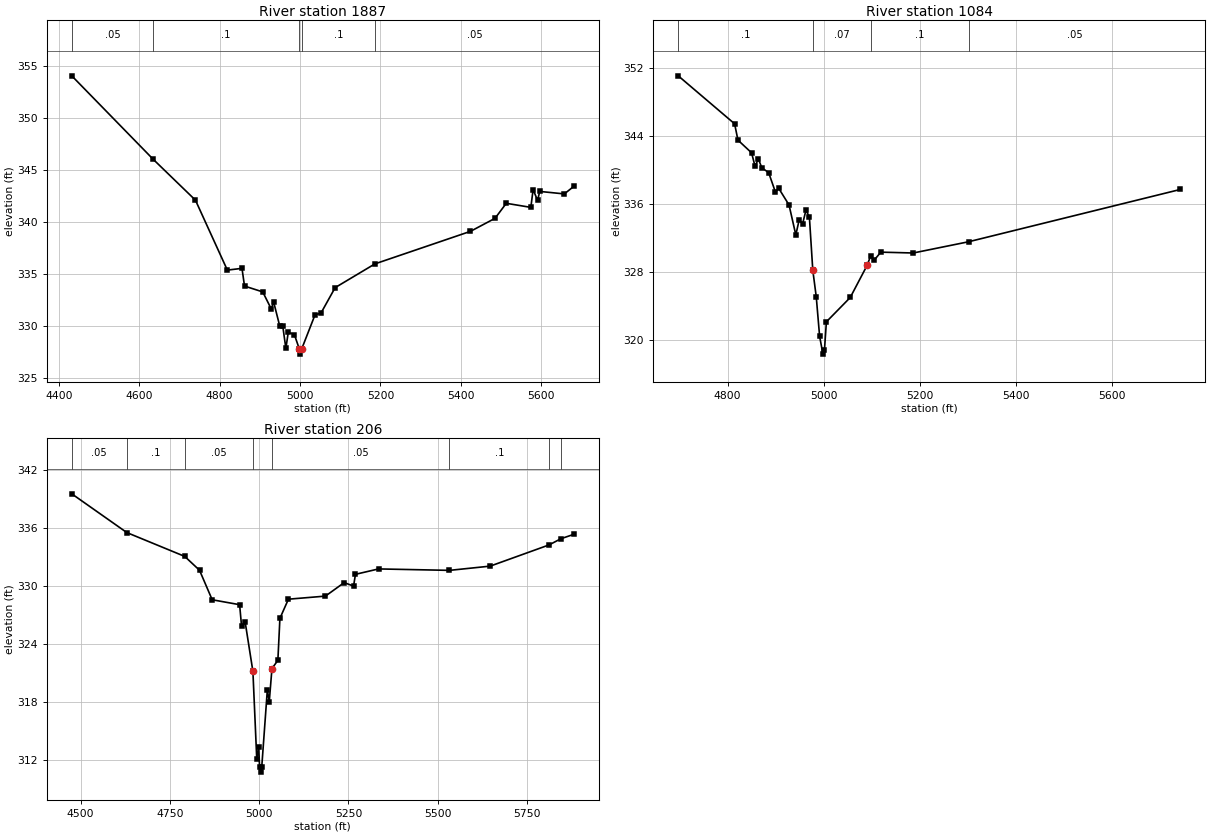
Type RM Length L Ch R = 1 ,1887    ,803,803,803
BEGIN DESCRIPTION:
UNT030 IN SUCR 3.0
END DESCRIPTION:
XS GIS Cut Line= 4
      2290176.75     13426154.21      2290489.26     13426293.11
       2290746.2     13426695.89      2291128.12     13426890.31
#Sta/Elev= 30
  4432.5  354.01  4634.2  346.03    4740  342.08  4819.3  335.37  4855.7  335.54
    4862  333.84  4907.3  333.28  4928.4  331.65  4934.4  332.31  4949.6     330
  4956.9  330.05  4964.8  327.86  4970.8  329.41    4986  329.18  4998.2  327.81
    5001  327.31  5004.2  327.81  5037.6  331.11  5051.7  331.22  5087.3  333.69
  5186.3  335.97  5423.8  339.09  5484.9  340.34  5512.8  341.78  5573.9  341.39
  5579.5   343.1  5590.5  342.07  5596.1  342.92  5657.2  342.68  5680.8  343.41
#Mann= 5 ,-1 , 0
  4432.5     .05       0  4634.2      .1       0  4998.2     .07       0
  5004.2      .1       0  5186.3     .05       0
Bank Sta=4998.2,5004.2
XS Rating Curve= 0 ,0
Exp/Cntr=0.3,0.1

Type RM Length L Ch R = 1 ,1084    ,878,878,878
BEGIN DESCRIPTION:
UNT030 IN SUCR 2.0
END DESCRIPTION:
XS GIS Cut Line= 3
      2289850.39     13426508.41      2290197.59     13426848.66
      2290744.46     13426959.42
#Sta/Elev= 30
  4697.5   351.1  4814.7  345.46  4821.7  343.54    4850  342.05  4857.2  340.47
  4864.2  341.32  4871.3  340.29  4885.5  339.72  4899.6  337.43  4906.6  337.86
  4927.9  335.92    4942   332.4    4949  334.16  4956.2  333.71  4963.2  335.33
  4970.3  334.45  4977.3  328.25  4984.5  325.13  4991.5  320.48  4998.4  318.38
  5001.6  318.88  5005.6  322.18  5055.2  325.04  5090.5  328.84  5097.6  329.92
  5104.6   329.4  5118.8  330.37  5186.2  330.27  5301.2  331.59  5741.6  337.74
#Mann= 4 ,-1 , 0
  4697.5      .1       0  4977.3     .07       0  5097.6      .1       0
  5301.2     .05       0
Bank Sta=4977.3,5090.5
XS Rating Curve= 0 ,0
Exp/Cntr=0.3,0.1

Type RM Length L Ch R = 1 ,206     ,0,0,0
BEGIN DESCRIPTION:
UNT030 IN SUCR 1.0
END DESCRIPTION:
XS GIS Cut Line= 4
      2289426.73      13426876.4      2289669.81     13427195.89
      2289892.04     13427286.16      2290621.17     13427057.01
#Sta/Elev= 30
  4475.3  339.58  4629.5  335.56  4791.5  333.09    4833  331.65  4868.4  328.59
  4945.2  328.08  4950.6  325.87  4960.8  326.26  4982.4  321.16  4993.2  312.05
  4998.7  313.31  5001.1  311.21  5003.9  310.71  5007.1  311.21  5022.8  319.24
  5028.2  318.02 5035.71  321.45  5052.3  322.31    5058  326.66  5081.8  328.65
  5185.5  328.97  5237.9  330.37  5264.2  330.01  5269.5  331.23  5334.3  331.79
  5532.7  331.64  5646.7  332.08  5811.5  334.28  5844.6  334.92  5880.9  335.38
#Mann= 8 ,-1 , 0
  4475.3     .05       0  4629.5      .1       0  4791.5     .05       0
  4982.4     .03       0  5036.4     .05       0  5532.7      .1       0
  5811.5     .05       0  5844.6      .1       0
Bank Sta=4982.4,5035.71
XS Rating Curve= 0 ,0
Exp/Cntr=0.3,0.1

Chan Stop Cuts=-1
Use User Specified Reach Order=0
Composite Channel Slope=5