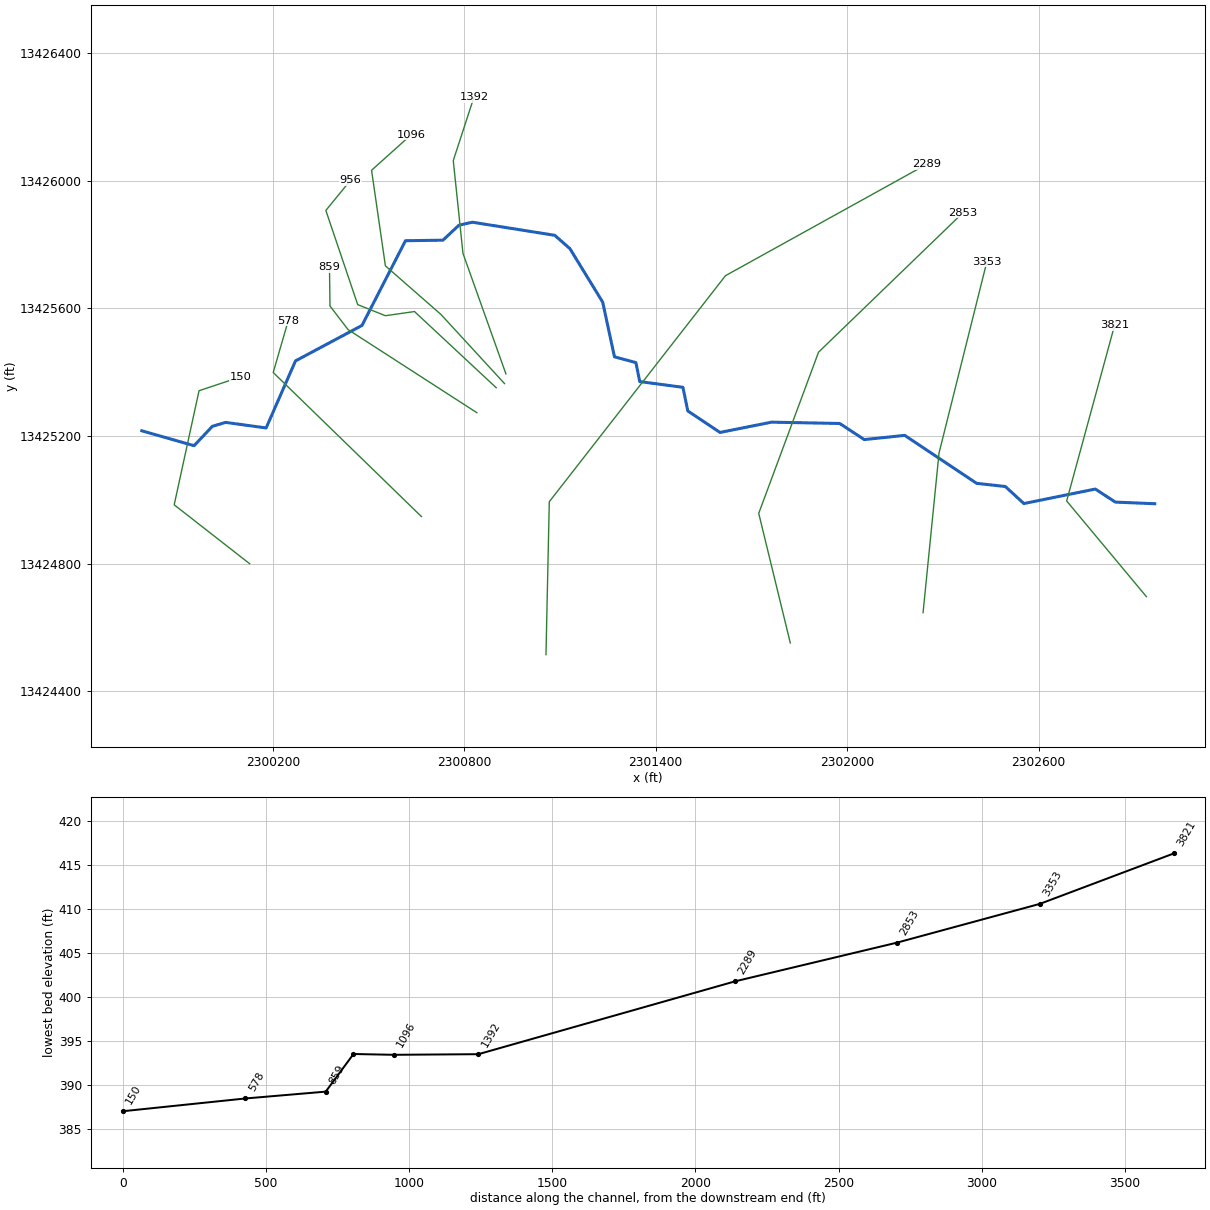
--- UNT031 IN SUCR.prj (project) ---

Proj Title=UNT031 IN SUCR Base Level Engineering
Current Plan=p01
Default Exp/Contr=0.3,0.1
English Units
Geom File=g01
Flow File=f01
Plan File=p01
Y Axis Title=Elevation
X Axis Title(PF)=Main Channel Distance
X Axis Title(XS)=Station
BEGIN DESCRIPTION:
UNT031 IN SUCR
END DESCRIPTION:
DSS Export Rating Curves= 0
DSS Export Rating Curve Sorted= 0
DSS Export Volume Flow Curves= 0
DXF OffsetX= 0
DXF OffsetY= 0
DXF ScaleX= 1
DXF ScaleY= 10

--- UNT031 IN SUCR.p01 (plan) ---

Plan Title=Multiple Run
Short Identifier=Multiple
Geom File=g01
Flow File=f01
Subcritical Flow
K Sum by GR= 0
Std Step Tol= 0.01
Critical Tol= 0.01
Num of Std Step Trials= 20
Max Error Tol= 0.3
Flow Tol Ratio= 0.001
Split Flow NTrial= 30
Split Flow Tol= 0.02
Split Flow Ratio= 0.02
Log Output Level= 0
Friction Slope Method= 1
Unsteady Friction Slope Method= 2
Unsteady Bridges Friction Slope Method= 1
Parabolic Critical Depth
Global Vel Dist=  1 , 1 , 1
Global Log Level= 0
CheckData=True
Encroach Param= -1, 0, 0, 0
BEGIN DESCRIPTION:
Multiple Run
END DESCRIPTION:

--- UNT031 IN SUCR.f01 (steady flow) ---

Flow Title=Multiple
Number of Profiles=7
Profile Names=10-year,25-year,50-year,1pct_min,100-year,1pct_plu,500-year
River Rch & RM= UNT031 IN SUCR,Reach-1,3821
     469     656     811     734     993    1342    1492
Boundary for River Rch & Prof#=UNT031 IN SUCR,Reach-1,1
Up Type=0
Dn Type=3
Dn Slope=0.005
Boundary for River Rch & Prof#=UNT031 IN SUCR,Reach-1,2
Up Type=0
Dn Type=3
Dn Slope=0.005
Boundary for River Rch & Prof#=UNT031 IN SUCR,Reach-1,3
Up Type=0
Dn Type=3
Dn Slope=0.005
Boundary for River Rch & Prof#=UNT031 IN SUCR,Reach-1,4
Up Type=0
Dn Type=3
Dn Slope=0.005
Boundary for River Rch & Prof#=UNT031 IN SUCR,Reach-1,5
Up Type=0
Dn Type=3
Dn Slope=0.005
Boundary for River Rch & Prof#=UNT031 IN SUCR,Reach-1,6
Up Type=0
Dn Type=3
Dn Slope=0.005
Boundary for River Rch & Prof#=UNT031 IN SUCR,Reach-1,7
Up Type=0
Dn Type=3
Dn Slope=0.005

--- UNT031 IN SUCR.g01 (geometry) ---

Geom Title=Existing Conditions
Program Version=4.10

River Reach=UNT031 IN SUCR  ,Reach-1
Reach XY= 30
       2302963.8     13424988.21       2302840.3     13424993.31
      2302777.51     13425034.24      2302553.64     13424988.77
      2302495.55     13425042.19      2302405.31     13425052.19
      2302180.41     13425202.41      2302053.64     13425189.21
      2301976.63     13425239.67      2301763.27     13425243.84
      2301601.46     13425211.66      2301500.48     13425278.91
      2301485.26     13425352.98      2301349.89     13425370.96
      2301337.89     13425430.47      2301270.75     13425448.53
      2301233.76     13425619.99      2301131.11     13425787.53
      2301083.66     13425829.34      2300825.47     13425870.39
       2300783.3     13425860.95       2300733.3     13425814.07
      2300615.83     13425812.38       2300479.5     13425546.86
      2300271.17     13425435.75      2300179.16     13425225.68
      2300052.42     13425243.04      2300010.75     13425230.89
      2299953.46     13425170.12      2299789.62     13425216.78

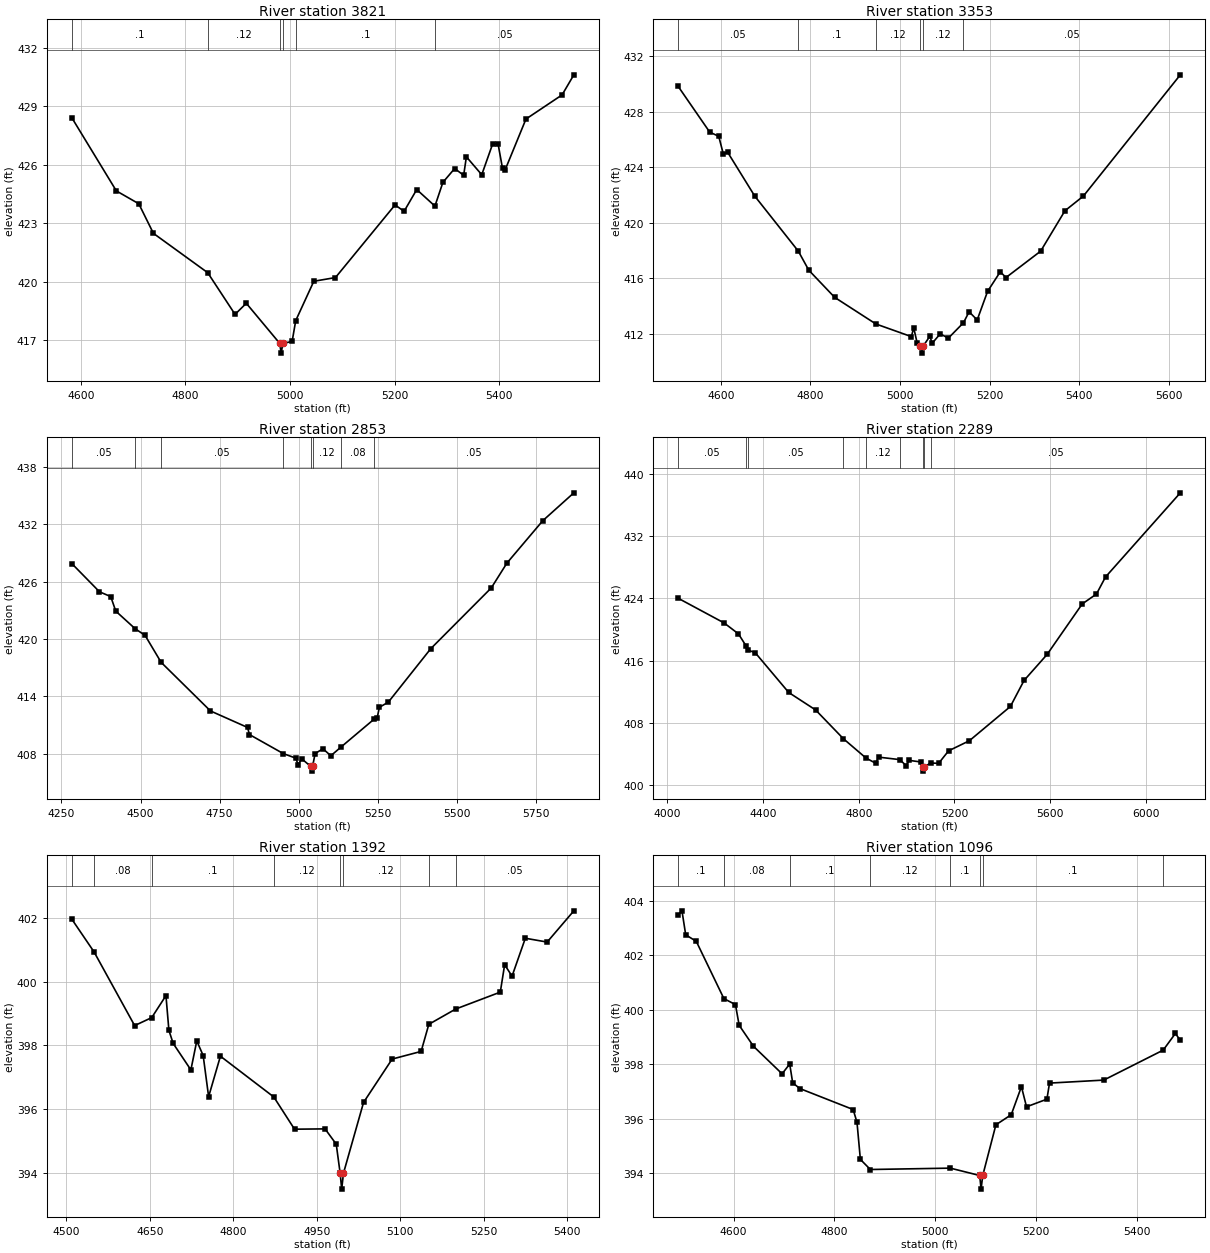
Type RM Length L Ch R = 1 ,3821    ,468,468,468
BEGIN DESCRIPTION:
UNT031 IN SUCR 5.0
END DESCRIPTION:
XS GIS Cut Line= 3
      2302937.71     13424696.86      2302687.72     13424996.85
      2302837.72     13425546.86
#Sta/Elev= 30
  4582.5  428.42  4667.8  424.66  4710.7     424  4738.7  422.48  4842.6  420.46
  4894.9  418.32  4916.4  418.89  4980.4  416.83  4983.1  416.33  4986.4  416.83
  5004.1  416.93    5011     418  5045.6  420.02    5087  420.21    5201  423.94
  5218.3  423.61  5242.5  424.73  5277.3  423.88  5292.6   425.1  5315.1  425.81
  5332.3  425.46  5337.5  426.41  5366.9  425.49  5387.6  427.06    5398  427.09
  5406.6  425.82  5411.8  425.75  5451.5  428.35  5520.6  429.59  5543.1  430.62
#Mann= 6 ,-1 , 0
  4582.5      .1       0  4842.6     .12       0  4980.4     .07       0
  4986.4     .12       0    5011      .1       0  5277.3     .05       0
Bank Sta=4980.4,4986.4
XS Rating Curve= 0 ,0
Exp/Cntr=0.3,0.1

Type RM Length L Ch R = 1 ,3353    ,500,500,500
BEGIN DESCRIPTION:
UNT031 IN SUCR 4.0
END DESCRIPTION:
XS GIS Cut Line= 3
      2302237.72     13424646.87      2302287.72     13425146.85
      2302437.71     13425746.81
#Sta/Elev= 30
  4504.9  429.81  4575.2  426.52  4595.3  426.22  4605.4  424.96  4615.4  425.06
  4675.7  421.91    4773  417.94  4796.3  416.57  4854.1  414.61  4946.2  412.69
  5025.4  411.78  5030.6  412.42  5038.3  411.32  5045.6  411.09  5048.4  410.59
  5051.6  411.09  5066.7  411.81  5071.8   411.3  5089.8  411.98  5107.9  411.67
  5141.7  412.78  5154.3  413.57  5172.3  412.98  5195.5  415.04  5223.8  416.45
  5236.7  416.04    5314  417.94  5368.2  420.85  5409.4  421.91  5625.8  430.65
#Mann= 6 ,-1 , 0
  4504.9     .05       0    4773      .1       0  4946.2     .12       0
  5045.6     .07       0  5051.6     .12       0  5141.7     .05       0
Bank Sta=5045.6,5051.6
XS Rating Curve= 0 ,0
Exp/Cntr=0.3,0.1

Type RM Length L Ch R = 1 ,2853    ,564,564,564
BEGIN DESCRIPTION:
UNT031 IN SUCR 3.0
END DESCRIPTION:
XS GIS Cut Line= 4
      2301821.72     13424551.79      2301722.76     13424958.04
      2301910.26     13425463.25      2302363.05     13425900.42
#Sta/Elev= 30
  4282.7   427.9  4370.3  424.94  4405.8  424.44  4421.7  422.92  4482.8  421.08
  4514.3  420.38    4565  417.56  4720.9  412.47  4838.2  410.74    4844     410
  4951.4     408  4990.5  407.53  4998.2  406.82  5008.9  407.47  5037.6  406.67
  5040.3  406.17  5043.6  406.67  5051.6  408.01  5076.3  408.51  5101.3  407.78
  5132.3  408.66  5238.7  411.63  5247.6  411.74  5254.6  412.85  5282.9  413.39
  5417.1  418.99  5608.3  425.35  5657.7  427.95  5770.9  432.38  5869.1   435.3
#Mann= 8 ,-1 , 0
  4282.7     .05       0  4482.8      .1       0    4565     .05       0
  4951.4     .12       0  5037.6     .07       0  5043.6     .12       0
  5132.3     .08       0  5238.7     .05       0
Bank Sta=5037.6,5043.6
XS Rating Curve= 0 ,0
Exp/Cntr=0.3,0.1

Type RM Length L Ch R = 1 ,2289    ,897,897,897
BEGIN DESCRIPTION:
UNT031 IN SUCR 2.0
END DESCRIPTION:
XS GIS Cut Line= 4
       2301056.1     13424515.33      2301066.51      13424994.5
       2301618.6     13425702.83      2302248.78     13426051.77
#Sta/Elev= 30
    4046  424.02  4237.6  420.85  4297.6  419.44  4329.8  417.87  4337.9  417.35
  4367.6  417.02  4507.6   411.9    4620  409.65    4736  405.95  4830.2  403.47
  4870.6   402.8  4883.3  403.58    4972  403.26  4997.4   402.5  5011.8  403.16
  5061.5  402.95  5066.7  402.28  5069.4  401.78  5072.7  402.28    5100  402.83
  5133.9  402.78  5175.5  404.39  5262.3  405.69  5433.8   410.1  5490.9  413.45
  5587.3   416.8  5733.8  423.29  5793.4  424.57  5831.2  426.76  6143.7  437.59
#Mann= 9 ,-1 , 0
    4046     .05       0  4329.8      .1       0  4337.9     .05       0
    4736      .1       0  4830.2     .12       0    4972     .08       0
  5066.7     .07       0  5072.7     .08       0    5100     .05       0
Bank Sta=5066.7,5072.7
XS Rating Curve= 0 ,0
Exp/Cntr=0.3,0.1

Type RM Length L Ch R = 1 ,1392    ,296,296,296
BEGIN DESCRIPTION:
Mapping XS afdb7de0
END DESCRIPTION:
XS GIS Cut Line= 4
      2300930.52     13425395.14      2300795.99     13425772.71
       2300765.6     13426063.51      2300830.49      13426262.5
#Sta/Elev= 30
  4509.7  401.96  4549.8  400.93  4622.7  398.62  4653.4  398.87    4679  399.56
  4684.3  398.47    4692  398.06  4723.8  397.23  4734.4  398.14  4745.9  397.68
  4755.7  396.39  4776.9  397.66  4872.9  396.38  4910.1  395.37    4965  395.38
  4985.1   394.9  4992.1  393.99  4994.9  393.49  4998.1  393.99  5034.2  396.21
  5085.6  397.57  5137.7  397.81  5151.5  398.66  5199.9  399.14    5280  399.67
  5287.8  400.53  5301.1  400.17    5325  401.36  5364.2  401.24  5412.2  402.22
#Mann= 8 ,-1 , 0
  4509.7      .1       0  4549.8     .08       0  4653.4      .1       0
  4872.9     .12       0  4992.1     .07       0  4998.1     .12       0
  5151.5      .1       0  5199.9     .05       0
Bank Sta=4992.1,4998.1
XS Rating Curve= 0 ,0
Exp/Cntr=0.3,0.1

Type RM Length L Ch R = 1 ,1096    ,140,140,140
BEGIN DESCRIPTION:
Mapping XS 6be3dcc2
END DESCRIPTION:
XS GIS Cut Line= 5
      2300926.18     13425364.74      2300726.54     13425581.74
      2300552.93     13425733.65      2300509.53     13426033.13
      2300634.05     13426144.76
#Sta/Elev= 30
  4490.4  403.49  4497.8  403.63  4505.2  402.75  4526.2  402.51  4580.9  400.41
  4603.8  400.19  4611.2  399.43  4639.6  398.66  4696.3  397.65  4711.4  398.01
  4717.3  397.32  4731.5  397.11  4837.2  396.34  4844.8  395.87  4851.5  394.51
  4871.3  394.14  5029.8  394.19  5088.1  393.92  5090.8  393.42  5094.1  393.92
  5120.2  395.78  5150.6  396.15  5170.8  397.18  5180.9  396.44  5221.3  396.72
  5226.5  397.31    5334  397.42  5451.9  398.52    5476  399.13  5485.8  398.88
#Mann= 8 ,-1 , 0
  4490.4      .1       0  4580.9     .08       0  4711.4      .1       0
  4871.3     .12       0  5029.8      .1       0  5088.1     .07       0
  5094.1      .1       0  5451.9     .05       0
Bank Sta=5088.1,5094.1
XS Rating Curve= 0 ,0
Exp/Cntr=0.3,0.1

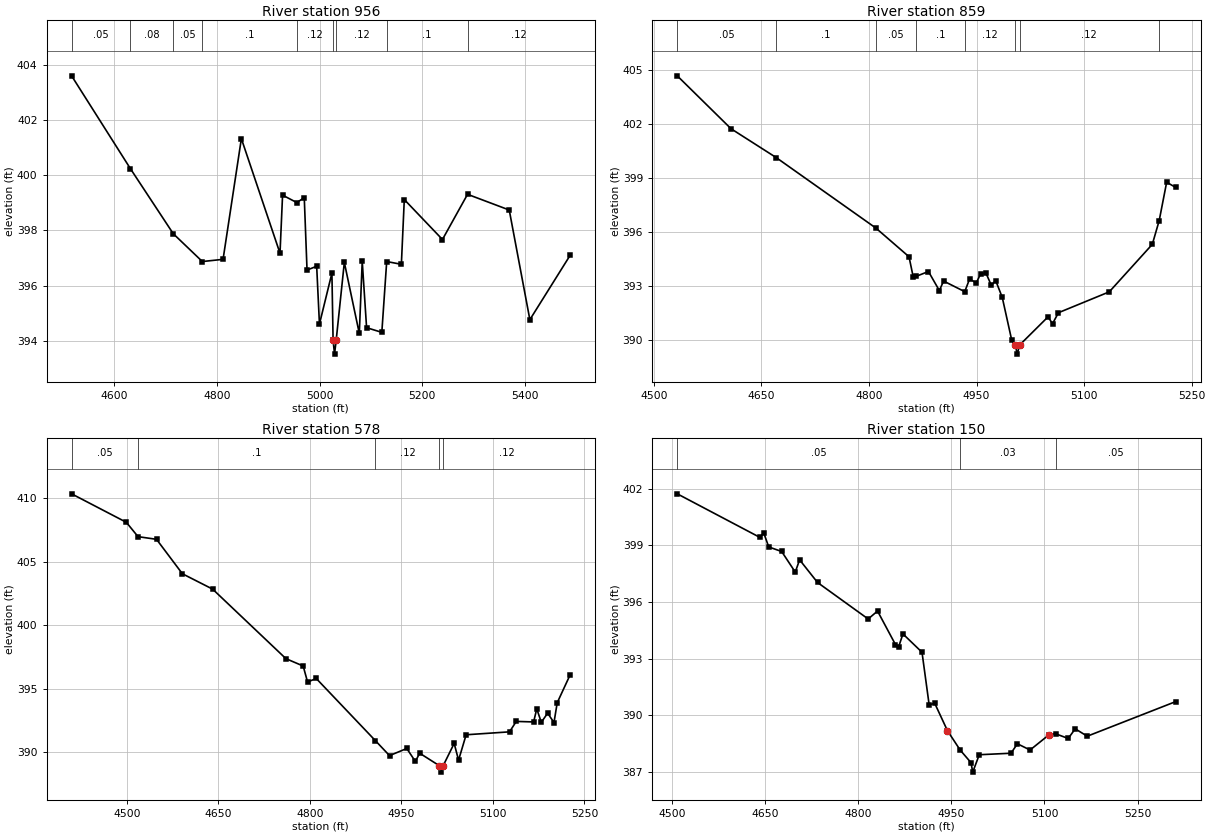
Type RM Length L Ch R = 1 ,956     ,97,97,97
BEGIN DESCRIPTION:
Mapping XS a286e705
END DESCRIPTION:
XS GIS Cut Line= 6
      2300900.12     13425351.74      2300644.08     13425590.42
      2300552.93      13425577.4      2300466.12     13425612.12
       2300366.3     13425907.26      2300443.24      13426001.3
#Sta/Elev= 30
  4516.6  403.61  4631.3  400.24  4714.8  397.88  4771.5  396.87  4811.9  396.95
  4847.6  401.33  4922.9  397.17  4927.9  399.28  4955.7  399.01  4970.2  399.19
  4975.6  396.56  4994.4   396.7  4999.8   394.6  5024.1  396.45  5026.4  394.01
  5029.2  393.51  5032.4  394.01  5048.3  396.84  5077.5  394.26  5083.2  396.88
  5091.7  394.47  5121.4   394.3  5130.9  396.87  5159.5  396.77  5165.2  399.12
  5239.6  397.67  5288.5  399.31  5369.8  398.74    5410  394.76  5488.3  397.09
#Mann= 9 ,-1 , 0
  4516.6     .05       0  4631.3     .08       0  4714.8     .05       0
  4771.5      .1       0  4955.7     .12       0  5026.4     .07       0
  5032.4     .12       0  5130.9      .1       0  5288.5     .12       0
Bank Sta=5026.4,5032.4
XS Rating Curve= 0 ,0
Exp/Cntr=0.3,0.1

Type RM Length L Ch R = 1 ,859     ,281,281,281
BEGIN DESCRIPTION:
Mapping XS 5215a306
END DESCRIPTION:
XS GIS Cut Line= 4
       2300839.4     13425273.57      2300435.74       13425534.
      2300379.32     13425607.78      2300377.69     13425729.41
#Sta/Elev= 30
  4532.8  404.69  4607.8  401.75  4670.7  400.15  4809.8  396.23  4855.9  394.64
  4861.9  393.49  4865.8  393.55    4883  393.82  4898.2  392.76  4904.1  393.29
  4933.6   392.7  4940.4  393.41  4949.6  393.18  4955.6  393.68  4963.2  393.73
  4970.7  393.05  4976.7  393.32  4985.9  392.38  4998.9  390.04    5004  389.73
  5006.8  389.23    5010  389.73  5049.7   391.3    5056  390.92  5064.2  391.53
  5135.1  392.69  5195.1  395.33  5204.7  396.65  5215.1  398.78  5227.7  398.49
#Mann= 8 ,-1 , 0
  4532.8     .05       0  4670.7      .1       0  4809.8     .05       0
  4865.8      .1       0  4933.6     .12       0    5004     .07       0
    5010     .12       0  5204.7      .1       0
Bank Sta=5004,5010
XS Rating Curve= 0 ,0
Exp/Cntr=0.3,0.1

Type RM Length L Ch R = 1 ,578     ,428,428,428
BEGIN DESCRIPTION:
Mapping XS b771ba6c
END DESCRIPTION:
XS GIS Cut Line= 3
      2300665.78     13424948.06      2300201.37     13425399.45
      2300248.52     13425562.11
#Sta/Elev= 30
  4409.4  410.35  4499.1  408.11  4518.3  406.98  4548.6  406.77    4591  404.06
  4640.6  402.85  4760.7  397.38    4789   396.8  4796.2  395.54  4810.4  395.82
  4907.5  390.92  4930.5  389.75  4958.8  390.31  4972.9  389.29  4979.9  389.94
  5012.4  388.95  5015.1  388.45  5018.4  388.95  5036.5  390.71  5043.7  389.39
  5056.1  391.39  5127.2  391.62  5138.3  392.44  5166.7   392.4  5171.9  393.43
  5179.3  392.37  5189.7  393.09  5200.1  392.35  5205.4  393.91  5226.4  396.09
#Mann= 5 ,-1 , 0
  4409.4     .05       0  4518.3      .1       0  4907.5     .12       0
  5012.4     .07       0  5018.4     .12       0
Bank Sta=5012.4,5018.4
XS Rating Curve= 0 ,0
Exp/Cntr=0.3,0.1

Type RM Length L Ch R = 1 ,150     ,0,0,0
BEGIN DESCRIPTION:
UNT031 IN SUCR 1.0
END DESCRIPTION:
XS GIS Cut Line= 4
      2300127.53     13424800.26      2299891.09      13424984.8
      2299968.94     13425342.34      2300098.67     13425385.59
#Sta/Elev= 30
  4508.7  401.72  4641.5  399.42    4648  399.65    4656  398.91  4676.8  398.67
  4698.7  397.58  4705.7  398.23  4734.6  397.03  4816.1   395.1  4831.2  395.52
    4860  393.75  4865.2  393.63  4872.1  394.31  4902.8  393.34  4914.3  390.56
  4923.3  390.64  4943.8  389.19  4964.2  388.17  4981.7   387.5  4984.5     387
    4995  387.92  5046.1     388  5056.4   388.5  5076.8  388.17  5107.5  388.98
  5117.8  389.03  5138.2  388.78  5149.5  389.29  5168.9   388.9  5311.3  390.73
#Mann= 3 ,-1 , 0
  4508.7     .05       0  4964.2     .03       0  5117.8     .05       0
Bank Sta=4943.8,5107.5
XS Rating Curve= 0 ,0
Exp/Cntr=0.3,0.1

Chan Stop Cuts=-1
Use User Specified Reach Order=0
Composite Channel Slope=5