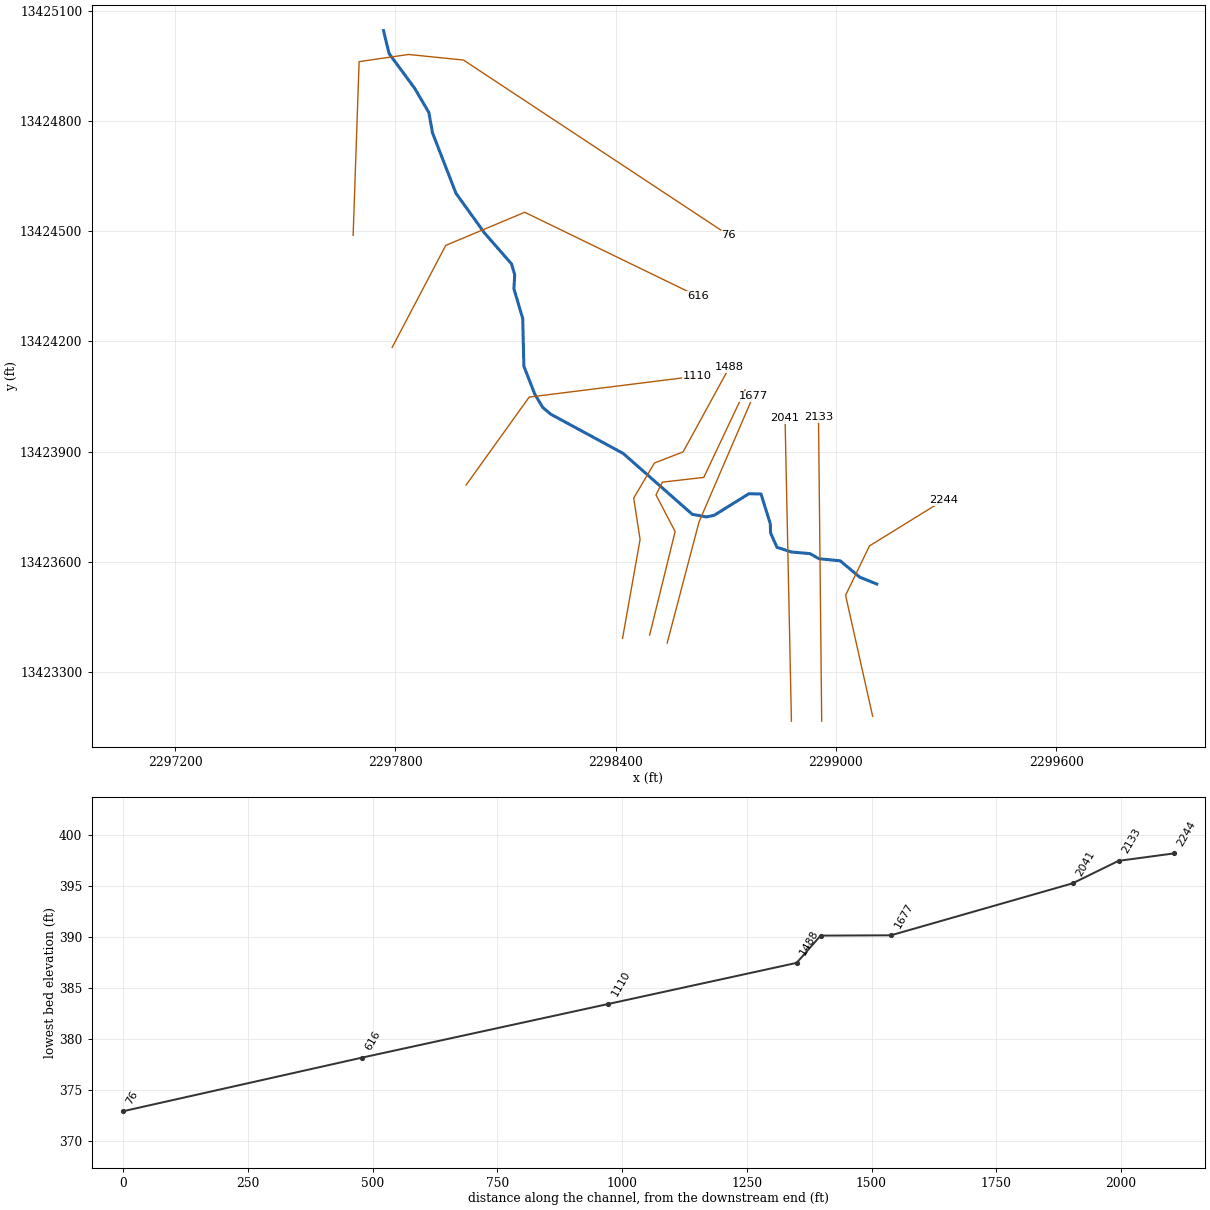
--- UNT032 IN SUCR.prj (project) ---

Proj Title=UNT032 IN SUCR Base Level Engineering
Current Plan=p01
Default Exp/Contr=0.3,0.1
English Units
Geom File=g01
Flow File=f01
Plan File=p01
Y Axis Title=Elevation
X Axis Title(PF)=Main Channel Distance
X Axis Title(XS)=Station
BEGIN DESCRIPTION:
UNT032 IN SUCR
END DESCRIPTION:
DSS Export Rating Curves= 0
DSS Export Rating Curve Sorted= 0
DSS Export Volume Flow Curves= 0
DXF OffsetX= 0
DXF OffsetY= 0
DXF ScaleX= 1
DXF ScaleY= 10

--- UNT032 IN SUCR.p01 (plan) ---

Plan Title=Multiple Run
Short Identifier=Multiple
Geom File=g01
Flow File=f01
Subcritical Flow
K Sum by GR= 0
Std Step Tol= 0.01
Critical Tol= 0.01
Num of Std Step Trials= 20
Max Error Tol= 0.3
Flow Tol Ratio= 0.001
Split Flow NTrial= 30
Split Flow Tol= 0.02
Split Flow Ratio= 0.02
Log Output Level= 0
Friction Slope Method= 1
Unsteady Friction Slope Method= 2
Unsteady Bridges Friction Slope Method= 1
Parabolic Critical Depth
Global Vel Dist=  1 , 1 , 1
Global Log Level= 0
CheckData=True
Encroach Param= -1, 0, 0, 0
BEGIN DESCRIPTION:
Multiple Run
END DESCRIPTION:

--- UNT032 IN SUCR.f01 (steady flow) ---

Flow Title=Multiple
Number of Profiles=7
Profile Names=10-year,25-year,50-year,1pct_min,100-year,1pct_plu,500-year
River Rch & RM= UNT032 IN SUCR,Reach-1,2244
     290     395     479     427     577     781     839
River Rch & RM= UNT032 IN SUCR,Reach-1,2133
     316     431     525     469     634     857     925
Boundary for River Rch & Prof#=UNT032 IN SUCR,Reach-1,1
Up Type=0
Dn Type=3
Dn Slope=0.005
Boundary for River Rch & Prof#=UNT032 IN SUCR,Reach-1,2
Up Type=0
Dn Type=3
Dn Slope=0.005
Boundary for River Rch & Prof#=UNT032 IN SUCR,Reach-1,3
Up Type=0
Dn Type=3
Dn Slope=0.005
Boundary for River Rch & Prof#=UNT032 IN SUCR,Reach-1,4
Up Type=0
Dn Type=3
Dn Slope=0.005
Boundary for River Rch & Prof#=UNT032 IN SUCR,Reach-1,5
Up Type=0
Dn Type=3
Dn Slope=0.005
Boundary for River Rch & Prof#=UNT032 IN SUCR,Reach-1,6
Up Type=0
Dn Type=3
Dn Slope=0.005
Boundary for River Rch & Prof#=UNT032 IN SUCR,Reach-1,7
Up Type=0
Dn Type=3
Dn Slope=0.005

--- UNT032 IN SUCR.g01 (geometry) ---

Geom Title=Existing Conditions
Program Version=4.10

River Reach=UNT032 IN SUCR  ,Reach-1
Reach XY= 30
       2299111.5     13423538.95      2299065.07     13423557.79
       2299011.9     13423602.28      2298954.16     13423607.92
      2298929.51     13423621.81      2298878.82     13423626.32
      2298839.58     13423639.17      2298822.18     13423678.35
      2298821.53     13423703.06      2298796.18     13423784.31
      2298763.19       13423785.      2298668.05     13423725.98
      2298646.87     13423721.81      2298608.81     13423729.01
      2298420.64     13423894.84      2298222.98     13424001.88
      2298201.21     13424020.42      2298179.41     13424057.39
      2298150.08     13424132.66      2298147.01     13424262.07
      2298122.94     13424343.62      2298125.19     13424381.47
      2298116.44     13424411.23      2298042.89     13424495.24
      2297965.12     13424603.54      2297901.13     13424768.26
      2297891.24      13424823.6      2297852.67     13424889.48
      2297782.85     13424984.26      2297767.72     13425046.85

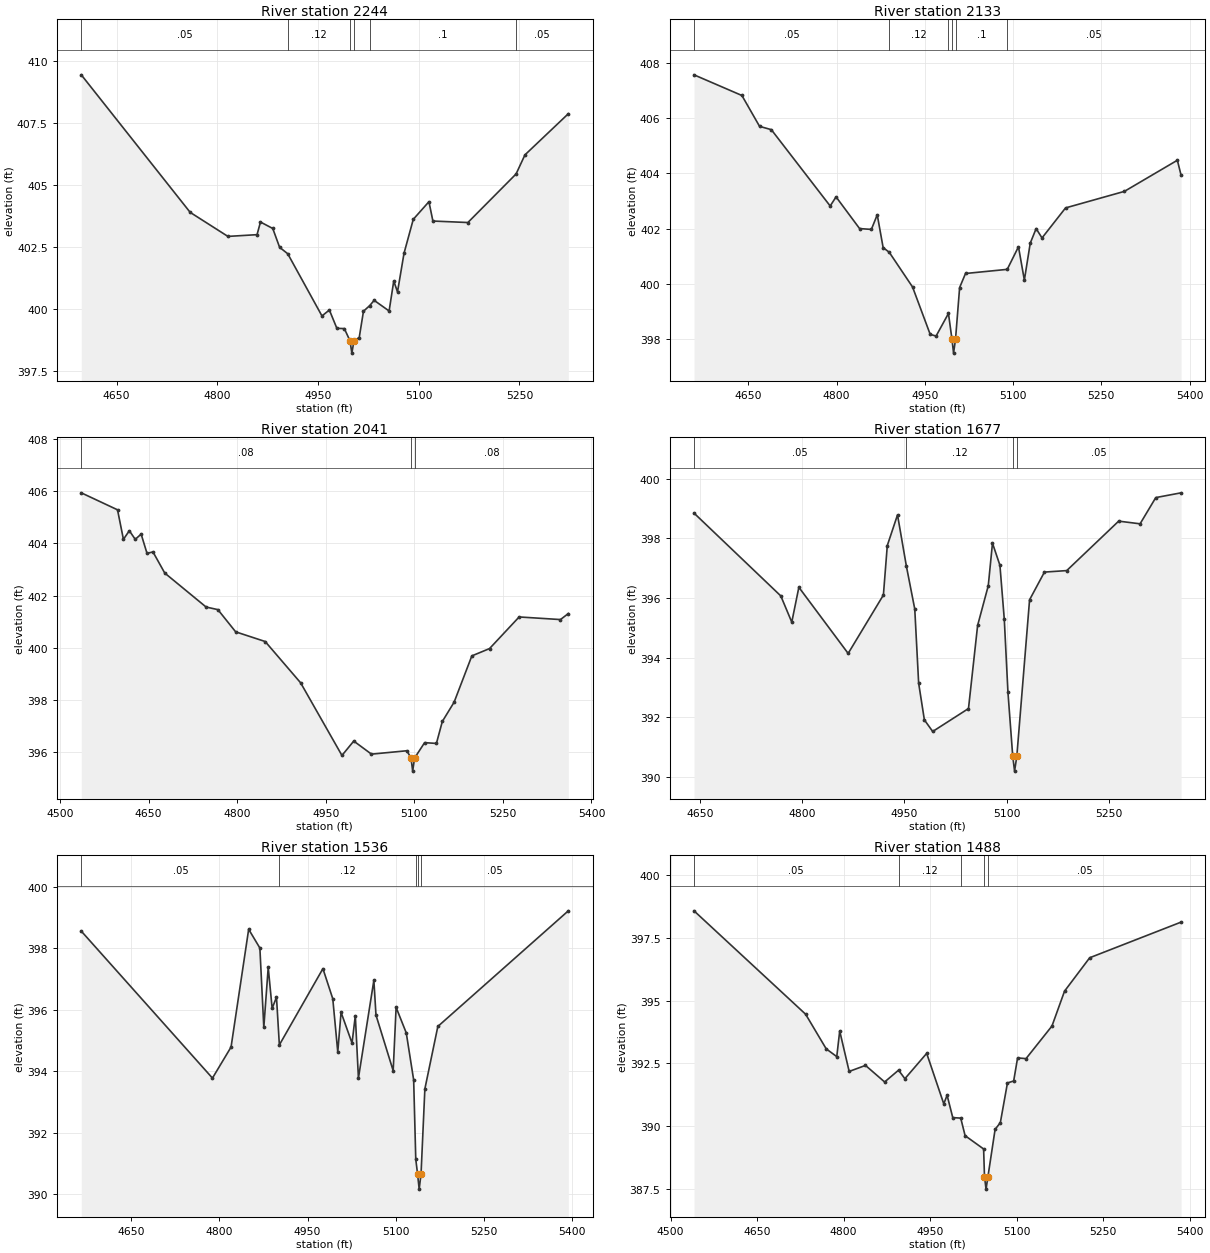
Type RM Length L Ch R = 1 ,2244    ,111,111,111
BEGIN DESCRIPTION:
UNT032 IN SUCR 3.0
END DESCRIPTION:
XS GIS Cut Line= 4
      2299100.36     13423178.57      2299026.58     13423508.39
      2299091.69     13423642.93       2299294.2     13423767.89
#Sta/Elev= 30
  4597.5  409.44  4759.7  403.89  4815.9  402.92  4859.3  402.99  4864.4   403.5
  4882.7  403.24  4892.9  402.48    4905  402.22    4956  399.71    4967  399.95
  4978.2  399.21  4989.3   399.2  4997.7  398.71  5000.5  398.21  5003.7  398.71
  5011.5  398.84  5017.8   399.9  5027.2  400.13  5033.7  400.34    5056  399.91
  5062.9  401.12  5068.5  400.68  5078.2  402.24    5092  403.61  5115.3  404.32
  5121.2  403.54  5173.3  403.48  5245.1  405.44  5258.3  406.21  5322.9  407.87
#Mann= 6 ,-1 , 0
  4597.5     .05       0    4905     .12       0  4997.7     .07       0
  5003.7     .12       0  5027.2      .1       0  5245.1     .05       0
Bank Sta=4997.7,5003.7
XS Rating Curve= 0 ,0
Exp/Cntr=0.3,0.1

Type RM Length L Ch R = 1 ,2133    ,92,92,92
BEGIN DESCRIPTION:
Mapping XS c8a85d3d
END DESCRIPTION:
XS GIS Cut Line= 2
      2298961.48     13423165.48      2298952.81     13423993.14
#Sta/Elev= 30
  4557.8  407.58  4639.2  406.83  4669.2  405.71  4689.2  405.59  4789.2  402.82
  4799.2  403.15  4839.2     402  4859.2  401.97  4869.2   402.5  4879.2  401.31
  4889.6  401.14  4929.2  399.88  4959.2  398.16  4969.2   398.1  4990.2  398.92
  4996.2  397.98  4998.9  397.48  5002.2  397.98  5009.2  399.86  5019.2  400.37
  5090.1  400.52  5109.2  401.34  5119.2  400.13  5129.2  401.47  5139.2     402
  5149.2  401.66  5189.2  402.75  5289.2  403.35  5379.2  404.48  5385.5  403.94
#Mann= 6 ,-1 , 0
  4557.8     .05       0  4889.6     .12       0  4990.2      .1       0
  4996.2     .07       0  5002.2      .1       0  5090.1     .05       0
Bank Sta=4996.2,5002.2
XS Rating Curve= 0 ,0
Exp/Cntr=0.3,0.1

Type RM Length L Ch R = 1 ,2041    ,364,364,364
BEGIN DESCRIPTION:
Mapping XS 35fb21c9
END DESCRIPTION:
XS GIS Cut Line= 2
      2298879.02     13423165.46      2298861.65     13423990.18
#Sta/Elev= 30
  4535.9  405.93  4597.3  405.28  4607.3  404.15  4617.3  404.48  4627.3  404.15
  4637.3  404.35  4647.3  403.61  4657.3  403.67  4677.3  402.86  4747.3  401.56
  4767.3  401.46  4797.4  400.61  4847.4  400.24  4907.4  398.66  4977.4  395.88
  4997.4  396.43  5027.4  395.93  5087.4  396.06  5094.4  395.78  5097.2  395.28
  5100.4  395.78  5117.4  396.37  5137.4  396.34  5147.4  397.18  5167.4  397.92
  5197.4  399.69  5227.4  399.97  5277.5  401.18  5347.5  401.08  5360.8  401.31
#Mann= 3 ,-1 , 0
  4535.9     .08       0  5094.4     .07       0  5100.4     .08       0
Bank Sta=5094.4,5100.4
XS Rating Curve= 0 ,0
Exp/Cntr=0.3,0.1

Type RM Length L Ch R = 1 ,1677    ,141,141,141
BEGIN DESCRIPTION:
Mapping XS c7a2a057
END DESCRIPTION:
XS GIS Cut Line= 3
      2298540.47     13423378.16      2298627.28     13423708.04
      2298774.85     13424050.93
#Sta/Elev= 30
  4641.3  398.85  4768.6  396.07  4784.7  395.19  4795.1  396.36  4867.4  394.14
  4919.1   396.1  4924.8  397.76  4939.8  398.79  4952.8  397.07  4965.1  395.63
  4970.8  393.14  4979.2  391.91  4991.4  391.52  5043.9  392.29  5057.3  395.08
  5072.9  396.41  5079.1  397.84    5090   397.1  5096.4  395.29  5101.8  392.83
  5108.8  390.69  5111.5  390.19  5114.8  390.69  5133.5  395.94  5155.3  396.87
    5188  396.92  5264.2  398.58  5295.6  398.49  5318.6  399.37  5355.7  399.53
#Mann= 4 ,-1 , 0
  4641.3     .05       0  4952.8     .12       0  5108.8     .07       0
  5114.8     .05       0
Bank Sta=5108.8,5114.8
XS Rating Curve= 0 ,0
Exp/Cntr=0.3,0.1

Type RM Length L Ch R = 1 ,1536    ,48,48,48
BEGIN DESCRIPTION:
UNT032 IN SUCR 2.0
END DESCRIPTION:
XS GIS Cut Line= 6
      2298492.73     13423399.87      2298562.17       13423682.
      2298510.09     13423781.82      2298527.45     13423816.54
       2298640.3     13423829.57      2298752.92     13424067.79
#Sta/Elev= 30
  4564.5  398.55    4788  393.77  4819.7  394.78  4849.7  398.61  4868.8     398
  4875.5  395.42    4883  397.37  4889.7  396.04  4897.1   396.4    4902  394.85
  4976.2  397.33    4993  396.35  5001.5  394.62  5007.1  395.91  5025.8  394.91
  5031.4   395.8  5036.7  393.77    5063  396.95  5066.6  395.82  5095.9  394.01
  5100.9  396.07  5118.2  395.24  5130.8  393.71  5134.4  391.13  5137.4  390.66
  5140.2  390.16  5143.4  390.66  5149.9  393.42    5172  395.45  5394.3  399.21
#Mann= 5 ,-1 , 0
  4564.5     .05       0    4902     .12       0  5134.4     .05       0
  5137.4     .07       0  5143.4     .05       0
Bank Sta=5137.4,5143.4
XS Rating Curve= 0 ,0
Exp/Cntr=0.3,0.1

Type RM Length L Ch R = 1 ,1488    ,378,378,378
BEGIN DESCRIPTION:
Mapping XS b7451654
END DESCRIPTION:
XS GIS Cut Line= 6
      2298418.94     13423391.19      2298466.69     13423660.29
      2298449.33     13423773.14      2298505.75     13423868.63
      2298583.88     13423899.01      2298709.73     13424129.01
#Sta/Elev= 30
  4540.6  398.58  4734.1  394.46  4769.8  393.08  4788.1  392.77  4793.2  393.79
  4809.6  392.18  4837.9  392.42  4871.1  391.76  4895.2  392.23  4906.2  391.89
    4944   392.9  4973.6  390.89  4979.4  391.23  4989.2  390.34    5003  390.32
  5010.6  389.62  5042.7  389.09  5044.2  387.99  5046.9  387.49  5050.2  387.99
  5062.6  389.87  5071.7  390.14    5084  391.72  5094.8   391.8  5101.6  392.72
  5116.2  392.69  5161.2  393.99    5183  395.38  5226.6  396.71    5385  398.13
#Mann= 5 ,-1 , 0
  4540.6     .05       0  4895.2     .12       0    5003     .05       0
  5044.2     .07       0  5050.2     .05       0
Bank Sta=5044.2,5050.2
XS Rating Curve= 0 ,0
Exp/Cntr=0.3,0.1

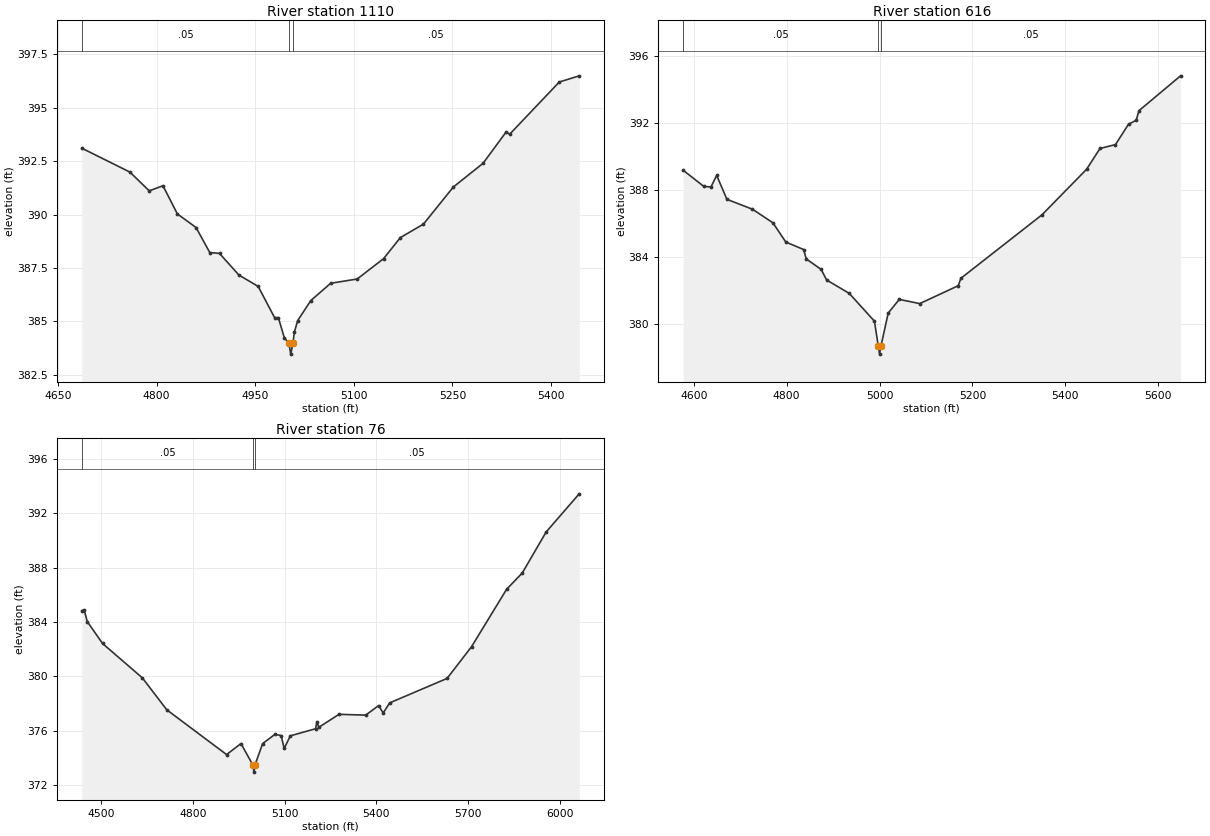
Type RM Length L Ch R = 1 ,1110    ,494,494,494
BEGIN DESCRIPTION:
Mapping XS faea66fc
END DESCRIPTION:
XS GIS Cut Line= 3
      2297992.72     13423808.71      2298164.61     13424048.32
      2298622.86      13424105.6
#Sta/Elev= 30
  4686.2  393.11  4759.4  391.99  4788.8  391.11  4809.7  391.35  4831.6  390.03
  4860.1  389.39  4880.9  388.22  4895.7  388.18  4925.1  387.17  4954.6  386.63
  4979.5  385.17  4985.2  385.17  4994.3  384.23  5001.4  383.96  5004.1  383.46
  5007.4  383.96  5009.5  384.48  5014.6  385.03  5034.6  385.97  5064.8  386.78
  5105.2  386.98  5145.5  387.94  5170.8  388.92  5205.9  389.55  5251.4  391.29
  5296.6   392.4    5332  393.88    5337  393.76  5412.6  396.21  5442.9   396.5
#Mann= 3 ,-1 , 0
  4686.2     .05       0  5001.4    .035       0  5007.4     .05       0
Bank Sta=5001.4,5007.4
XS Rating Curve= 0 ,0
Exp/Cntr=0.3,0.1

Type RM Length L Ch R = 1 ,616     ,478,478,478
BEGIN DESCRIPTION:
Mapping XS ea5e9cb9
END DESCRIPTION:
XS GIS Cut Line= 4
      2297791.33     13424183.71      2297937.17     13424461.51
      2298152.45     13424551.79      2298623.69      13424323.1
#Sta/Elev= 30
  4577.1  389.19  4621.7  388.22  4637.1  388.19  4649.3  388.88  4671.4  387.45
  4726.3  386.86  4770.4  386.05  4798.1   384.9  4836.5  384.45  4842.2  383.89
  4874.3  383.26  4886.1  382.63  4934.8  381.83    4989  380.17  4997.2   378.7
    5000   378.2  5003.2   378.7  5018.6  380.65  5042.4  381.47  5086.6  381.22
  5169.5  382.29  5175.1  382.73    5350  386.53  5445.9  389.25  5474.7  390.49
    5508  390.72  5536.1  391.94  5552.5  392.17  5558.7  392.75  5648.1  394.83
#Mann= 3 ,-1 , 0
  4577.1     .05       0  4997.2    .035       0  5003.2     .05       0
Bank Sta=4997.2,5003.2
XS Rating Curve= 0 ,0
Exp/Cntr=0.3,0.1

Type RM Length L Ch R = 1 ,76      ,0,0,0
BEGIN DESCRIPTION:
UNT032 IN SUCR 1.0
END DESCRIPTION:
XS GIS Cut Line= 5
      2297684.97     13424489.11      2297701.24     13424962.19
      2297835.79     13424981.72      2297985.53     13424966.53
      2298708.01     13424489.29
#Sta/Elev= 30
  4437.3  384.83  4445.1  384.89  4455.1  384.03  4505.1  382.42  4635.2  379.89
  4715.2  377.54  4910.5  374.25  4957.6  375.06    4997  373.46  4999.8  372.96
    5003  373.46  5028.4  375.06  5068.7  375.74  5088.8  375.65  5098.8   374.7
  5118.9  375.63  5201.4  376.15  5205.7  376.67  5211.7  376.25  5277.9  377.21
  5365.2  377.15  5407.3  377.85  5422.4  377.31  5443.5  378.05  5631.2  379.85
  5711.4  382.19  5825.7   386.4  5876.9   387.6  5955.1  390.62    6063  393.42
#Mann= 3 ,-1 , 0
  4437.3     .05       0    4997     .03       0    5003     .05       0
Bank Sta=4997,5003
XS Rating Curve= 0 ,0
Exp/Cntr=0.3,0.1

Chan Stop Cuts=-1
Use User Specified Reach Order=0
Composite Channel Slope=5