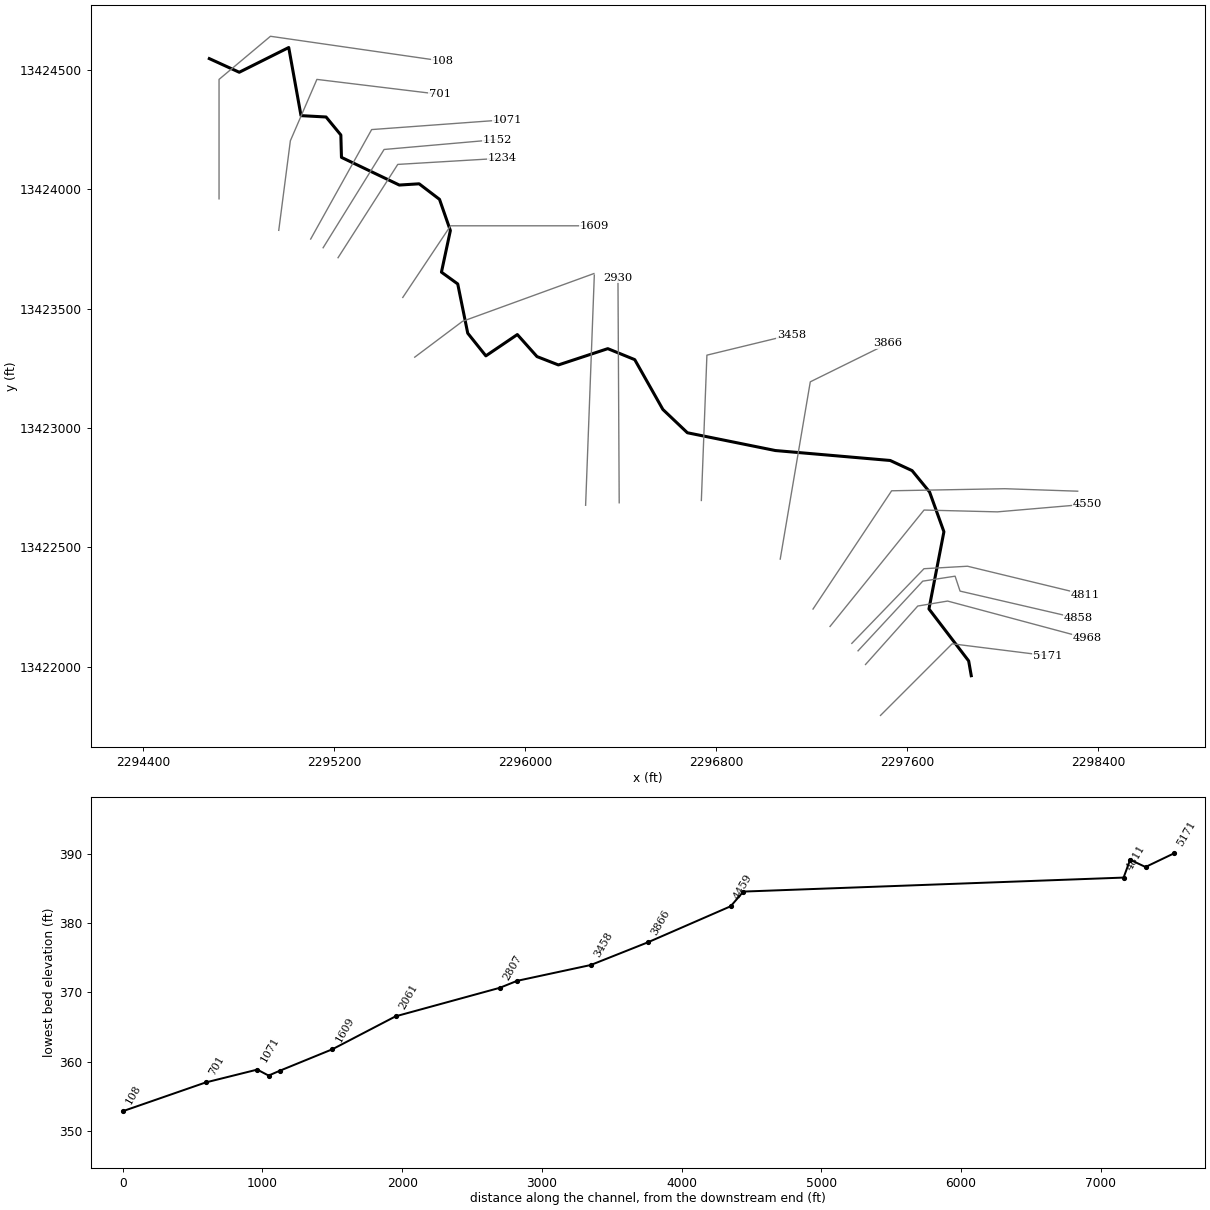
--- UNT033 IN SUCR.prj (project) ---

Proj Title=UNT033 IN SUCR Base Level Engineering
Current Plan=p01
Default Exp/Contr=0.3,0.1
English Units
Geom File=g01
Flow File=f01
Plan File=p01
Y Axis Title=Elevation
X Axis Title(PF)=Main Channel Distance
X Axis Title(XS)=Station
BEGIN DESCRIPTION:
UNT033 IN SUCR
END DESCRIPTION:
DSS Export Rating Curves= 0
DSS Export Rating Curve Sorted= 0
DSS Export Volume Flow Curves= 0
DXF OffsetX= 0
DXF OffsetY= 0
DXF ScaleX= 1
DXF ScaleY= 10

--- UNT033 IN SUCR.p01 (plan) ---

Plan Title=Multiple Run
Short Identifier=Multiple
Geom File=g01
Flow File=f01
Subcritical Flow
K Sum by GR= 0
Std Step Tol= 0.01
Critical Tol= 0.01
Num of Std Step Trials= 20
Max Error Tol= 0.3
Flow Tol Ratio= 0.001
Split Flow NTrial= 30
Split Flow Tol= 0.02
Split Flow Ratio= 0.02
Log Output Level= 0
Friction Slope Method= 1
Unsteady Friction Slope Method= 2
Unsteady Bridges Friction Slope Method= 1
Parabolic Critical Depth
Global Vel Dist=  1 , 1 , 1
Global Log Level= 0
CheckData=True
Encroach Param= -1, 0, 0, 0
BEGIN DESCRIPTION:
Multiple Run
END DESCRIPTION:

--- UNT033 IN SUCR.f01 (steady flow) ---

Flow Title=Multiple
Program Version=4.10
Number of Profiles= 7
Profile Names=10-year,25-year,50-year,1pct_min,100-year,1pct_plu,500-year
River Rch & RM=UNT033 IN SUCR,Reach-1         ,5171
     145     186     217     187     252     341     340
River Rch & RM=UNT033 IN SUCR,Reach-1         ,4858
     419     578     709     636     860    1163    1269
Boundary for River Rch & Prof#=UNT033 IN SUCR,Reach-1         , 1
Up Type= 0
Dn Type= 3
Dn Slope=0.005
Boundary for River Rch & Prof#=UNT033 IN SUCR,Reach-1         , 2
Up Type= 0
Dn Type= 3
Dn Slope=0.005
Boundary for River Rch & Prof#=UNT033 IN SUCR,Reach-1         , 3
Up Type= 0
Dn Type= 3
Dn Slope=0.005
Boundary for River Rch & Prof#=UNT033 IN SUCR,Reach-1         , 4
Up Type= 0
Dn Type= 3
Dn Slope=0.005
Boundary for River Rch & Prof#=UNT033 IN SUCR,Reach-1         , 5
Up Type= 0
Dn Type= 3
Dn Slope=0.005
Boundary for River Rch & Prof#=UNT033 IN SUCR,Reach-1         , 6
Up Type= 0
Dn Type= 3
Dn Slope=0.005
Boundary for River Rch & Prof#=UNT033 IN SUCR,Reach-1         , 7
Up Type= 0
Dn Type= 3
Dn Slope=0.005
DSS Import GetInterval= 0
DSS Import GetPeak= 0
DSS Import FillOption= 0

--- UNT033 IN SUCR.g01 (geometry) ---

Geom Title=Existing Conditions
Program Version=4.10

River Reach=UNT033 IN SUCR  ,Reach-1
Reach XY= 30
      2297867.73     13421963.19      2297856.88     13422025.04
      2297690.65      13422242.7      2297753.24     13422566.01
      2297693.26     13422732.35      2297619.94     13422821.91
      2297528.33      13422864.3      2297047.42     13422905.96
      2296679.19      13422980.4      2296576.62     13423077.89
      2296458.84      13423286.5      2296345.99      13423332.5
      2296139.24     13423264.32      2296049.56     13423299.29
      2295967.29     13423391.55      2295835.49      13423302.3
      2295759.61     13423397.21      2295717.75     13423603.41
      2295649.57     13423652.75       2295686.9     13423826.97
      2295641.46     13423957.59      2295556.22     13424022.64
      2295473.17     13424017.44      2295230.98     13424133.33
      2295228.38     13424227.08       2295166.5     13424302.37
      2295061.58     13424308.07      2295010.18     13424593.26
      2294803.03     13424489.67      2294677.72     13424546.85

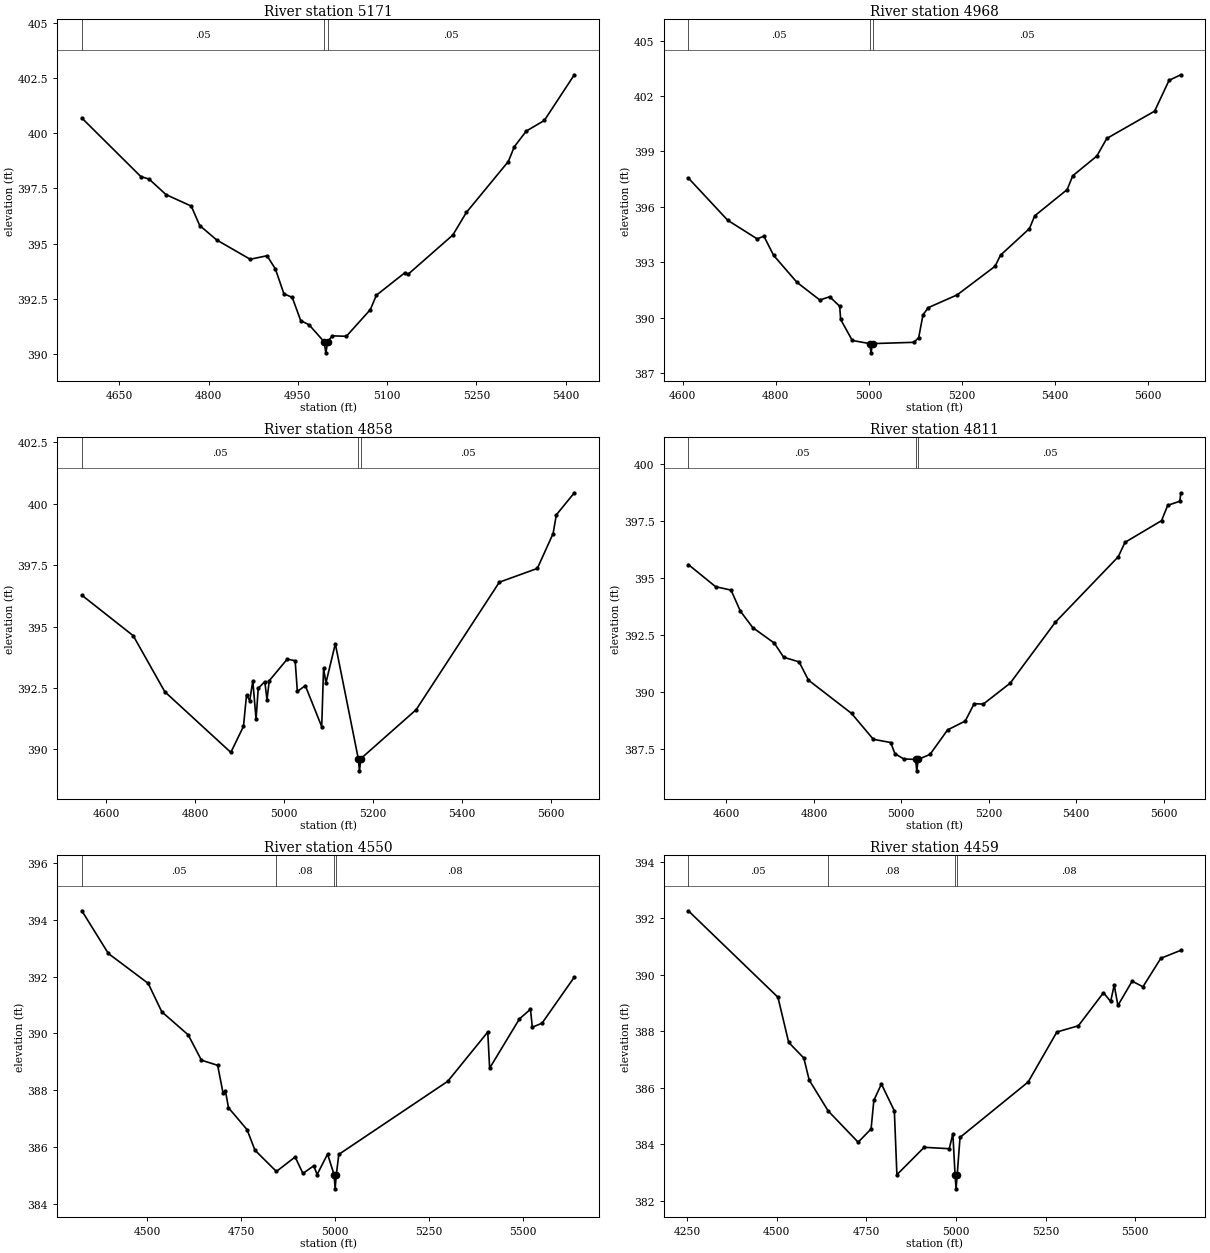
Type RM Length L Ch R = 1 ,5171    ,203,203,203
BEGIN DESCRIPTION:
UNT033 IN SUCR 11.0
END DESCRIPTION:
XS GIS Cut Line= 3
      2297487.73     13421796.87      2297787.72     13422096.85
      2298187.76     13422046.85
#Sta/Elev= 30
  4587.1  400.69  4686.1  398.04  4700.2  397.92  4728.5  397.22  4770.9   396.7
  4785.1  395.82  4813.4  395.17  4869.9  394.29  4898.2  394.45  4912.3  393.85
  4926.5  392.73  4940.6  392.56  4954.8  391.51  4968.9  391.32  4994.2  390.55
    4997  390.05  5000.2  390.55  5007.8  390.82  5031.5   390.8  5071.8  392.01
  5081.9  392.66  5129.8  393.68  5134.8   393.6  5210.4  395.39  5233.1  396.41
  5303.6  398.72  5313.7  399.39  5333.8   400.1  5364.1  400.58  5414.5  402.65
#Mann= 3 ,-1 , 0
  4587.1     .05       0  4994.2    .035       0  5000.2     .05       0
Bank Sta=4994.2,5000.2
XS Rating Curve= 0 ,0
Exp/Cntr=0.3,0.1

Type RM Length L Ch R = 1 ,4968    ,110,110,110
BEGIN DESCRIPTION:
Mapping XS fae7da1c
END DESCRIPTION:
XS GIS Cut Line= 4
      2297425.01     13422010.11      2297643.77     13422254.91
      2297768.77     13422275.75      2298352.08      13422119.5
#Sta/Elev= 30
    4612  397.56  4696.7  395.27  4760.2  394.26  4774.5  394.41  4795.4  393.37
  4845.5  391.91  4894.8  390.95  4916.1  391.13  4937.5  390.61  4939.5   389.9
  4964.6  388.76  5002.1  388.59  5004.9  388.09  5008.1  388.59    5097  388.66
  5107.3  388.91  5116.6  390.15  5128.1  390.54  5190.2  391.23  5271.6  392.78
  5283.3  393.38  5345.5  394.82  5356.8  395.51  5426.5  396.93  5438.6  397.68
  5490.4  398.75  5511.7   399.7  5614.6  401.18  5645.7  402.85  5670.9  403.15
#Mann= 3 ,-1 , 0
    4612     .05       0  5002.1    .035       0  5008.1     .05       0
Bank Sta=5002.1,5008.1
XS Rating Curve= 0 ,0
Exp/Cntr=0.3,0.1

Type RM Length L Ch R = 1 ,4858    ,47,47,47
BEGIN DESCRIPTION:
UNT033 IN SUCR 10.0
END DESCRIPTION:
XS GIS Cut Line= 5
      2297393.77     13422067.41      2297664.61     13422359.08
      2297800.02     13422379.91      2297820.86     13422317.41
      2298314.18     13422203.17
#Sta/Elev= 30
    4545  396.28  4660.6  394.63  4731.5  392.35    4880  389.88  4908.4  390.94
  4915.2  392.21  4922.5  391.99  4929.4  392.79  4936.7  391.23  4941.6  392.49
  4956.3  392.76  4961.3  392.03  4966.4   392.8  5006.9  393.68  5024.6  393.61
  5029.6  392.36  5047.4   392.6  5084.3  390.93  5088.5  393.31  5093.8  392.71
  5114.9   394.3  5166.5  389.63  5169.2  389.13  5172.5  389.63  5296.7  391.62
  5483.7  396.81  5569.1  397.37  5604.6  398.79  5611.8  399.55  5652.3  400.45
#Mann= 3 ,-1 , 0
    4545     .05       0  5166.5    .035       0  5172.5     .05       0
Bank Sta=5166.5,5172.5
XS Rating Curve= 0 ,0
Exp/Cntr=0.3,0.1

Type RM Length L Ch R = 1 ,4811    ,2721,2721,2721
BEGIN DESCRIPTION:
Mapping XS 1669b1e3
END DESCRIPTION:
XS GIS Cut Line= 4
       2297367.7     13422098.64      2297669.81     13422411.16
      2297852.11     13422421.58      2298346.75     13422301.82
#Sta/Elev= 30
  4512.8  395.59  4575.2  394.62  4610.5  394.47  4631.8  393.55  4660.1  392.83
  4709.5  392.15  4730.9  391.53  4766.1  391.33  4787.5  390.53  4886.3  389.07
  4935.9  387.94  4975.4   387.8  4985.4  387.31  5005.5  387.08  5032.5  387.06
  5035.3  386.56  5038.5  387.06  5065.6  387.28  5105.6  388.35  5146.1  388.74
  5166.5   389.5  5187.3  389.48    5249   390.4  5351.9  393.06    5496  395.93
  5511.4  396.56    5595  397.51  5609.1  398.18  5636.9  398.36    5639  398.73
#Mann= 3 ,-1 , 0
  4512.8     .05       0  5032.5    .035       0  5038.5     .05       0
Bank Sta=5032.5,5038.5
XS Rating Curve= 0 ,0
Exp/Cntr=0.3,0.1

Type RM Length L Ch R = 1 ,4550    ,91,91,91
BEGIN DESCRIPTION:
UNT033 IN SUCR 9.1
END DESCRIPTION:
XS GIS Cut Line= 4
      2297276.42     13422169.44      2297669.98     13422656.78
      2297977.06     13422649.18       2298353.4     13422681.46
#Sta/Elev= 30
  4325.4  394.31  4395.9  392.81    4502  391.76  4538.3  390.76  4608.6  389.95
  4643.8  389.06    4687  388.88  4701.4   387.9  4707.8  387.98  4715.8  387.39
  4765.3  386.62  4786.2   385.9  4843.4  385.15  4893.3  385.66  4914.1  385.08
  4942.9  385.35  4951.8  385.04  4979.6  385.76    4997  385.04  4999.8  384.54
    5003  385.04  5009.6  385.75  5299.8  388.32  5406.2  390.05  5411.2  388.78
  5490.5  390.51  5519.9  390.85  5524.9  390.22  5550.7  390.36  5636.7  391.98
#Mann= 4 ,-1 , 0
  4325.4     .05       0  4843.4     .08       0    4997     .07       0
    5003     .08       0
Bank Sta=4997,5003
XS Rating Curve= 0 ,0
Exp/Cntr=0.3,0.1

Type RM Length L Ch R = 1 ,4459    ,593,593,593
BEGIN DESCRIPTION:
UNT033 IN SUCR 9.0
END DESCRIPTION:
XS GIS Cut Line= 4
      2297205.22     13422242.34      2297534.35     13422737.43
      2298008.31     13422746.11      2298313.28     13422735.72
#Sta/Elev= 30
    4253  392.26    4503   389.2    4533   387.6  4575.1  387.05  4590.2  386.27
  4642.9  385.18  4726.7  384.07  4762.8  384.54  4770.5  385.55  4791.6  386.13
  4827.7  385.18  4834.8  382.92  4910.9  383.89  4980.9  383.84  4990.9  384.37
    4997  382.92  4999.8  382.42    5003  382.92  5010.9  384.24  5200.9   386.2
    5281  387.97    5341  388.19    5411  389.36    5431  389.05    5441  389.63
  5451.3  388.91  5491.1  389.77  5521.1  389.57  5571.1  390.58  5626.7  390.86
#Mann= 4 ,-1 , 0
    4253     .05       0  4642.9     .08       0    4997     .07       0
    5003     .08       0
Bank Sta=4997,5003
XS Rating Curve= 0 ,0
Exp/Cntr=0.3,0.1

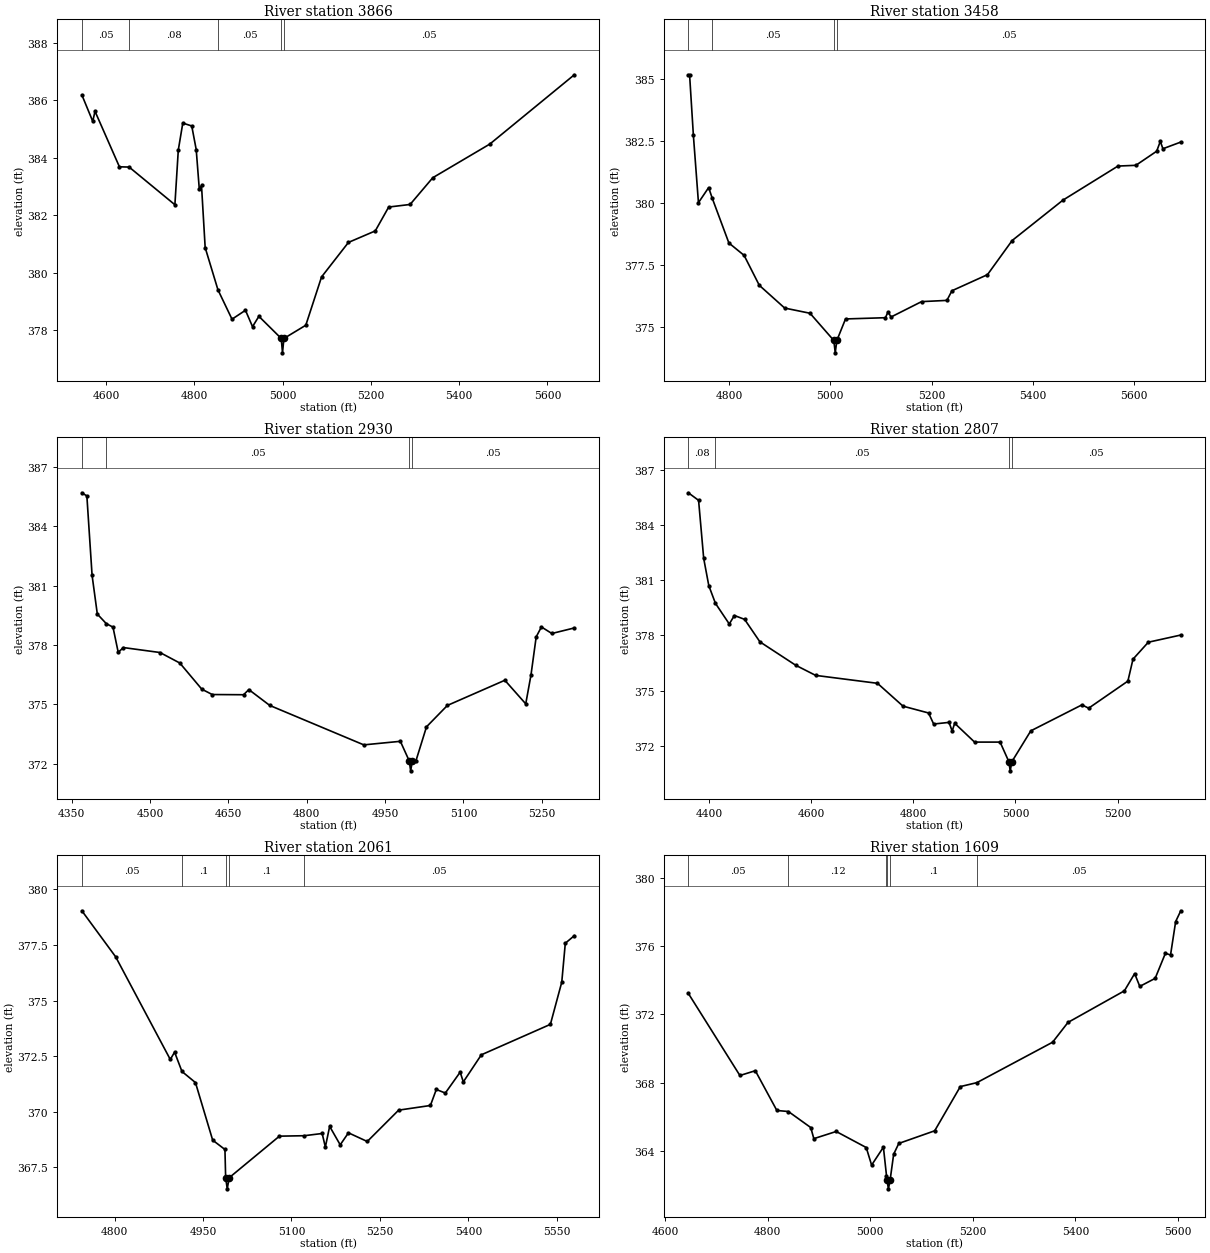
Type RM Length L Ch R = 1 ,3866    ,408,408,408
BEGIN DESCRIPTION:
UNT033 IN SUCR 8.0
END DESCRIPTION:
XS GIS Cut Line= 3
      2297067.91     13422451.41      2297193.78      13423193.6
      2297519.33      13423354.2
#Sta/Elev= 30
  4545.2  386.18  4569.9  385.26    4575  385.61  4630.3  383.68  4652.4  383.67
    4756  382.36  4763.7  384.26  4773.9   385.2  4794.2   385.1  4804.3  384.28
  4811.3   382.9  4816.3  383.03  4824.6  380.87  4853.6   379.4  4885.4  378.38
  4915.9  378.69  4931.9  378.12  4946.3  378.48    4997  377.71  4999.8  377.21
    5003  377.71  5052.6  378.17  5088.3  379.85  5149.2  381.05    5210  381.45
  5240.4  382.28  5288.9  382.37  5340.3   383.3  5469.5  384.47    5661  386.88
#Mann= 5 ,-1 , 0
  4545.2     .05       0  4652.4     .08       0  4853.6     .05       0
    4997    .035       0    5003     .05       0
Bank Sta=4997,5003
XS Rating Curve= 0 ,0
Exp/Cntr=0.3,0.1

Type RM Length L Ch R = 1 ,3458    ,528,528,528
BEGIN DESCRIPTION:
UNT033 IN SUCR 7.0
END DESCRIPTION:
XS GIS Cut Line= 3
      2296737.72     13422696.83      2296760.96     13423305.27
      2297113.94     13423390.92
#Sta/Elev= 30
  4719.9  385.18  4722.4  385.18  4729.9  382.73  4739.9  380.01    4760  380.62
  4767.3  380.18    4800  378.38    4830  377.88    4860  376.67  4910.1  375.75
  4960.1  375.54  5007.1  374.44  5009.9  373.94  5013.1  374.44  5030.2  375.31
    5109  375.36    5114  375.59  5120.2  375.39  5180.3  376.01  5230.3  376.06
  5240.3  376.45  5310.4   377.1  5359.1  378.48  5459.2  380.11    5568  381.49
  5603.3  381.52  5644.4  382.09  5651.6  382.49  5656.7  382.19    5692  382.46
#Mann= 4 ,-1 , 0
  4719.9     .08       0  4767.3     .05       0  5007.1    .035       0
  5013.1     .05       0
Bank Sta=5007.1,5013.1
XS Rating Curve= 0 ,0
Exp/Cntr=0.3,0.1

Type RM Length L Ch R = 1 ,2930    ,123,123,123
BEGIN DESCRIPTION:
UNT033 IN SUCR 6.0
END DESCRIPTION:
XS GIS Cut Line= 2
      2296393.77     13422687.21      2296388.56      13423629.9
#Sta/Elev= 30
  4369.6  385.68  4379.2  385.52  4389.2  381.51  4399.2  379.56  4416.3  379.08
  4429.2   378.9  4439.2  377.63  4449.2  377.87  4519.2  377.62  4557.1  377.09
  4599.2  375.77  4619.2   375.5  4679.2  375.49  4689.2  375.75  4729.3  374.95
  4909.3  372.96  4979.3  373.14  4996.3  372.15    4999  371.65  5002.3  372.15
  5009.3  372.17  5029.3  373.87  5069.3  374.95  5179.3  376.22  5219.3  375.03
  5229.3  376.48  5239.3  378.41  5249.3  378.91  5269.3  378.58  5312.3  378.86
#Mann= 4 ,-1 , 0
  4369.6     .08       0  4416.3     .05       0  4996.3    .035       0
  5002.3     .05       0
Bank Sta=4996.3,5002.3
XS Rating Curve= 0 ,0
Exp/Cntr=0.3,0.1

Type RM Length L Ch R = 1 ,2807    ,746,746,746
BEGIN DESCRIPTION:
UNT033 IN SUCR 5.0
END DESCRIPTION:
XS GIS Cut Line= 2
      2296253.15     13422676.75      2296289.61     13423640.36
#Sta/Elev= 30
  4359.6  385.74  4379.7  385.33  4389.7  382.18  4399.7   380.7  4412.7  379.74
  4439.8  378.62  4449.8  379.08  4469.8  378.87  4499.8  377.65  4569.9  376.38
  4608.9  375.83    4730   375.4    4780  374.16    4830  373.79    4840  373.19
  4870.1  373.28  4876.2  372.81  4881.2  373.23  4920.1  372.21  4970.1  372.21
  4987.2  371.15  4989.9  370.65  4993.2  371.15  5030.2  372.82  5130.3  374.23
  5143.5  374.05  5220.3  375.52  5230.3  376.71  5260.3  377.63  5323.9  378.02
#Mann= 4 ,-1 , 0
  4359.6     .08       0  4412.7     .05       0  4987.2    .035       0
  4993.2     .05       0
Bank Sta=4987.2,4993.2
XS Rating Curve= 0 ,0
Exp/Cntr=0.3,0.1

Type RM Length L Ch R = 1 ,2061    ,452,452,452
BEGIN DESCRIPTION:
UNT033 IN SUCR 4.0
END DESCRIPTION:
XS GIS Cut Line= 3
      2295537.71     13423296.84      2295737.72     13423446.85
      2296287.77     13423646.87
#Sta/Elev= 30
  4744.5  379.04  4801.8  376.97  4894.5  372.35  4901.8  372.68  4914.3  371.81
  4937.2  371.31  4966.4  368.72  4987.2   368.3  4988.4  367.03  4991.1  366.53
  4994.4  367.03  5079.6   368.9  5121.7  368.92  5152.1  369.02  5157.5  368.41
  5164.8  369.34  5182.7  368.51  5196.7  369.05  5228.6  368.66  5281.8  370.07
  5335.7  370.28  5345.7     371    5361  370.84  5386.2  371.78  5391.5  371.34
  5422.1  372.56  5539.2  373.93  5558.5  375.83  5564.5  377.58  5579.8  377.92
#Mann= 5 ,-1 , 0
  4744.5     .05       0  4914.3      .1       0  4988.4     .07       0
  4994.4      .1       0  5121.7     .05       0
Bank Sta=4988.4,4994.4
XS Rating Curve= 0 ,0
Exp/Cntr=0.3,0.1

Type RM Length L Ch R = 1 ,1609    ,375,375,375
BEGIN DESCRIPTION:
UNT033 IN SUCR 3.0
END DESCRIPTION:
XS GIS Cut Line= 3
      2295487.74     13423546.89      2295687.72     13423846.85
      2296287.71     13423846.85
#Sta/Elev= 30
  4645.1  373.23  4745.7  368.42  4775.8   368.7  4817.8  366.37  4840.3  366.31
  4883.9  365.37  4889.9  364.72  4933.5  365.14  4992.1   364.2  5002.6  363.17
  5025.6  364.22  5031.6  362.56  5032.6  362.28  5035.4  361.78  5038.6  362.28
  5045.6  363.81  5055.6  364.44  5125.6  365.18  5175.6  367.77  5207.8     368
  5355.6  370.37  5385.6  371.53  5495.6  373.38  5515.6  374.39  5525.6  373.64
  5555.6  374.11  5575.6  375.58  5585.6  375.48  5595.6  377.44  5605.6  378.07
#Mann= 6 ,-1 , 0
  4645.1     .05       0  4840.3     .12       0  5031.6      .1       0
  5032.6     .07       0  5038.6      .1       0  5207.8     .05       0
Bank Sta=5032.6,5038.6
XS Rating Curve= 0 ,0
Exp/Cntr=0.3,0.1

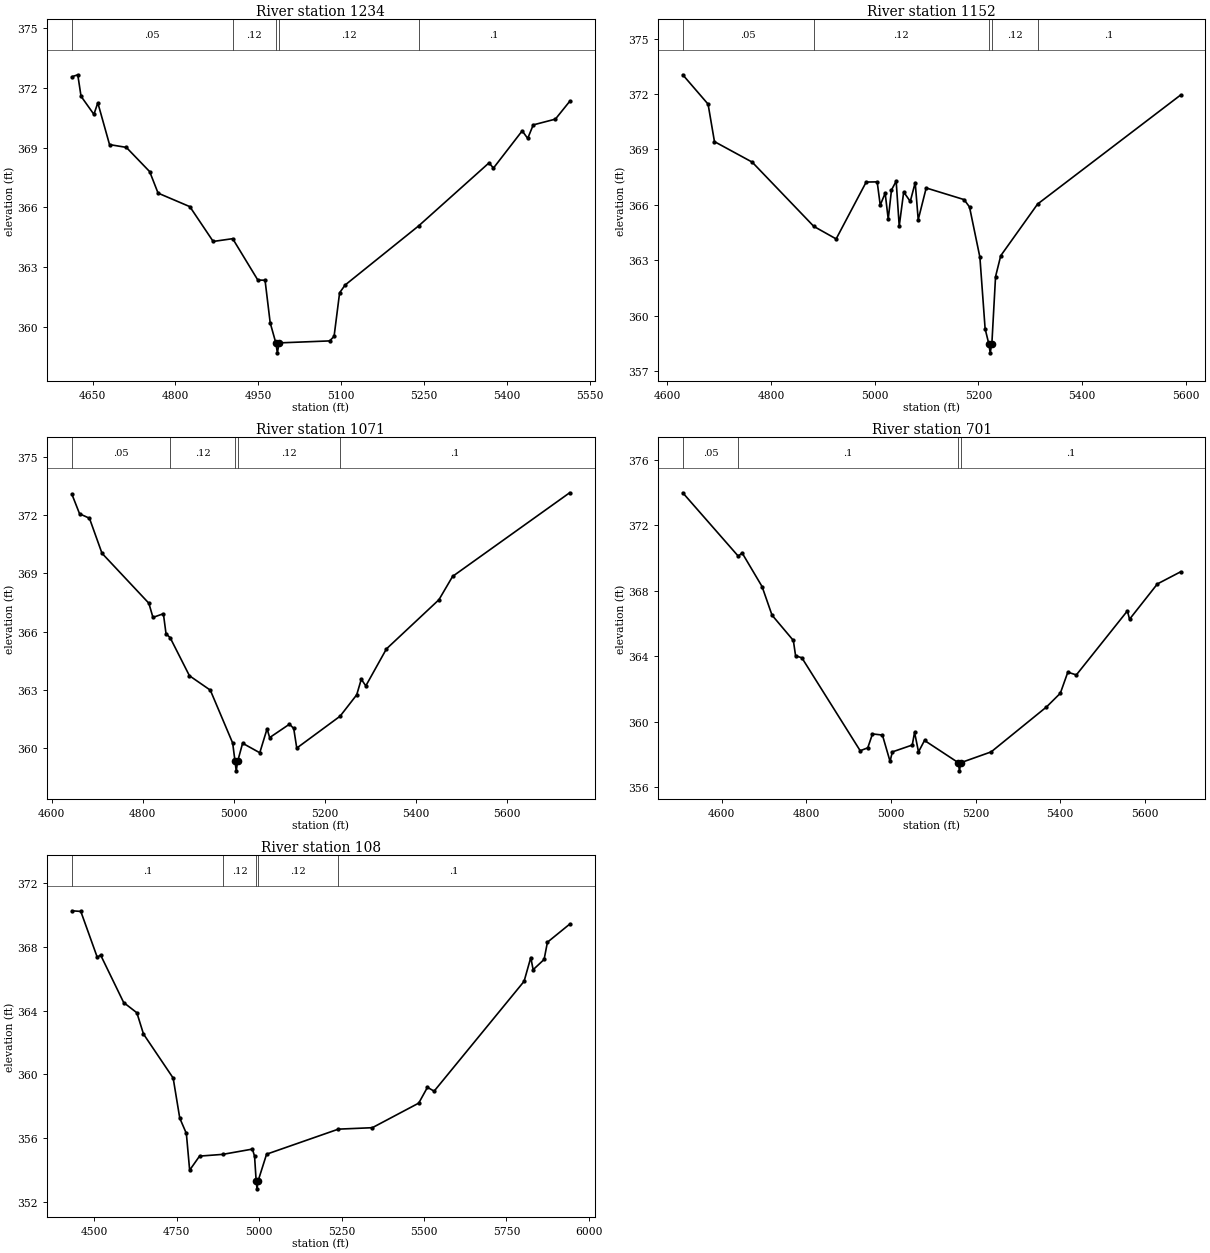
Type RM Length L Ch R = 1 ,1234    ,82,82,82
BEGIN DESCRIPTION:
Mapping XS 424a6952
END DESCRIPTION:
XS GIS Cut Line= 3
       2295216.7     13423713.26      2295466.69     13424103.87
      2295903.46     13424129.87
#Sta/Elev= 30
  4612.5  372.57  4623.2  372.67  4629.1  371.59  4652.4  370.68  4659.5  371.26
  4680.7  369.16  4711.1  369.02  4753.4   367.8  4768.6  366.72  4826.1  366.04
  4868.4  364.29  4903.7  364.43  4949.2  362.35  4962.3  362.34  4971.6   360.2
  4981.8  359.19  4984.6  358.69  4987.8  359.19  5079.3  359.29  5087.3  359.52
  5097.3  361.71  5107.3   362.1  5240.3  365.07  5367.8  368.24  5375.9  367.98
  5427.9  369.85  5437.9  369.47  5447.9  370.15    5488  370.44  5513.8  371.33
#Mann= 5 ,-1 , 0
  4612.5     .05       0  4903.7     .12       0  4981.8     .07       0
  4987.8     .12       0  5240.3      .1       0
Bank Sta=4981.8,4987.8
XS Rating Curve= 0 ,0
Exp/Cntr=0.3,0.1

Type RM Length L Ch R = 1 ,1152    ,81,81,81
BEGIN DESCRIPTION:
UNT033 IN SUCR 2.0
END DESCRIPTION:
XS GIS Cut Line= 3
      2295154.19     13423754.91       2295409.4     13424166.37
      2295882.99     13424208.01
#Sta/Elev= 30
  4630.1  373.04  4678.9  371.45  4691.2  369.42  4763.9  368.31  4882.7  364.83
  4925.8  364.15  4983.7  367.23  5004.9  367.24  5010.8  365.98  5020.3  366.63
  5026.2  365.22  5032.5   366.8  5041.5  367.28  5047.4  364.84    5056  366.69
  5068.7  366.18  5078.2   367.2    5084  365.19  5099.4  366.91  5172.4  366.28
  5182.9  365.88  5202.9  363.16    5213  359.28    5220  358.48  5222.8  357.98
    5226  358.48  5233.1  362.11  5243.1  363.24  5314.2  366.04  5589.7  371.94
#Mann= 5 ,-1 , 0
  4630.1     .05       0  4882.7     .12       0    5220     .07       0
    5226     .12       0  5314.2      .1       0
Bank Sta=5220,5226
XS Rating Curve= 0 ,0
Exp/Cntr=0.3,0.1

Type RM Length L Ch R = 1 ,1071    ,370,370,370
BEGIN DESCRIPTION:
Mapping XS 158f0984
END DESCRIPTION:
XS GIS Cut Line= 3
       2295102.1     13423791.37      2295357.31      13424249.7
      2295923.89     13424291.29
#Sta/Elev= 30
  4644.3  373.07  4661.2  372.06  4682.9  371.83  4710.4  370.03  4813.3  367.46
  4822.3  366.73  4845.2  366.92    4851  365.89    4860  365.69  4902.4  363.73
  4948.2  362.99  4997.3  360.27  5002.4  359.34  5005.1  358.84  5008.4  359.34
  5019.1  360.26  5056.8  359.77  5072.8     361  5078.5  360.55    5122  361.24
  5131.3  361.02    5138  360.01  5233.1  361.65  5269.6  362.75  5279.6  363.55
  5289.6  363.21  5334.8  365.11  5450.1  367.64  5480.1  368.84    5737  373.14
#Mann= 5 ,-1 , 0
  4644.3     .05       0    4860     .12       0  5002.4     .07       0
  5008.4     .12       0  5233.1      .1       0
Bank Sta=5002.4,5008.4
XS Rating Curve= 0 ,0
Exp/Cntr=0.3,0.1

Type RM Length L Ch R = 1 ,701     ,593,593,593
BEGIN DESCRIPTION:
Mapping XS 610a5f5a
END DESCRIPTION:
XS GIS Cut Line= 4
      2294968.43     13423827.84      2295017.04     13424202.83
      2295128.15     13424459.77      2295641.99     13424397.28
#Sta/Elev= 30
  4508.3     374  4639.4  370.12  4648.5  370.32  4695.6  368.26  4719.1  366.51
  4769.5  364.96  4774.8  364.02  4789.6   363.9  4927.4  358.21  4945.3  358.39
  4956.4  359.24  4979.9  359.17  4997.9  357.56  5003.4  358.14  5050.4  358.56
  5055.8  359.34  5065.1  358.14  5079.3  358.84  5159.1  357.48  5161.8  356.98
  5165.1  357.48  5236.7  358.14  5367.4  360.89  5400.1  361.73  5417.8  363.02
  5437.9  362.85  5558.5  366.77  5563.6  366.26  5629.3  368.42    5684  369.16
#Mann= 4 ,-1 , 0
  4508.3     .05       0  4639.4      .1       0  5159.1     .07       0
  5165.1      .1       0
Bank Sta=5159.1,5165.1
XS Rating Curve= 0 ,0
Exp/Cntr=0.3,0.1

Type RM Length L Ch R = 1 ,108     ,0,0,0
BEGIN DESCRIPTION:
UNT033 IN SUCR 1.0
END DESCRIPTION:
XS GIS Cut Line= 4
      2294718.42     13423959.76      2294718.42     13424459.77
       2294933.7     13424640.33      2295654.36     13424536.39
#Sta/Elev= 30
  4432.5  370.25  4459.6  370.21  4509.6  367.33  4519.6  367.48  4589.6   364.5
  4629.6  363.86  4649.6  362.53  4739.6  359.77  4759.6  357.26  4779.6   356.3
  4789.6     354  4819.6  354.88    4890  354.99  4979.9  355.32  4986.4  354.87
  4991.2  353.33  4993.9  352.83  4997.2  353.33  5022.8     355  5240.5  356.57
  5343.4  356.66  5484.1   358.2  5510.5  359.19  5530.8  358.95  5803.5  365.83
  5823.8  367.32    5831  366.56  5864.2   367.2  5874.3  368.28  5941.6  369.41
#Mann= 5 ,-1 , 0
  4432.5      .1       0    4890     .12       0  4991.2     .07       0
  4997.2     .12       0  5240.5      .1       0
Bank Sta=4991.2,4997.2
XS Rating Curve= 0 ,0
Exp/Cntr=0.3,0.1

Chan Stop Cuts=-1
Use User Specified Reach Order=0
Composite Channel Slope=5