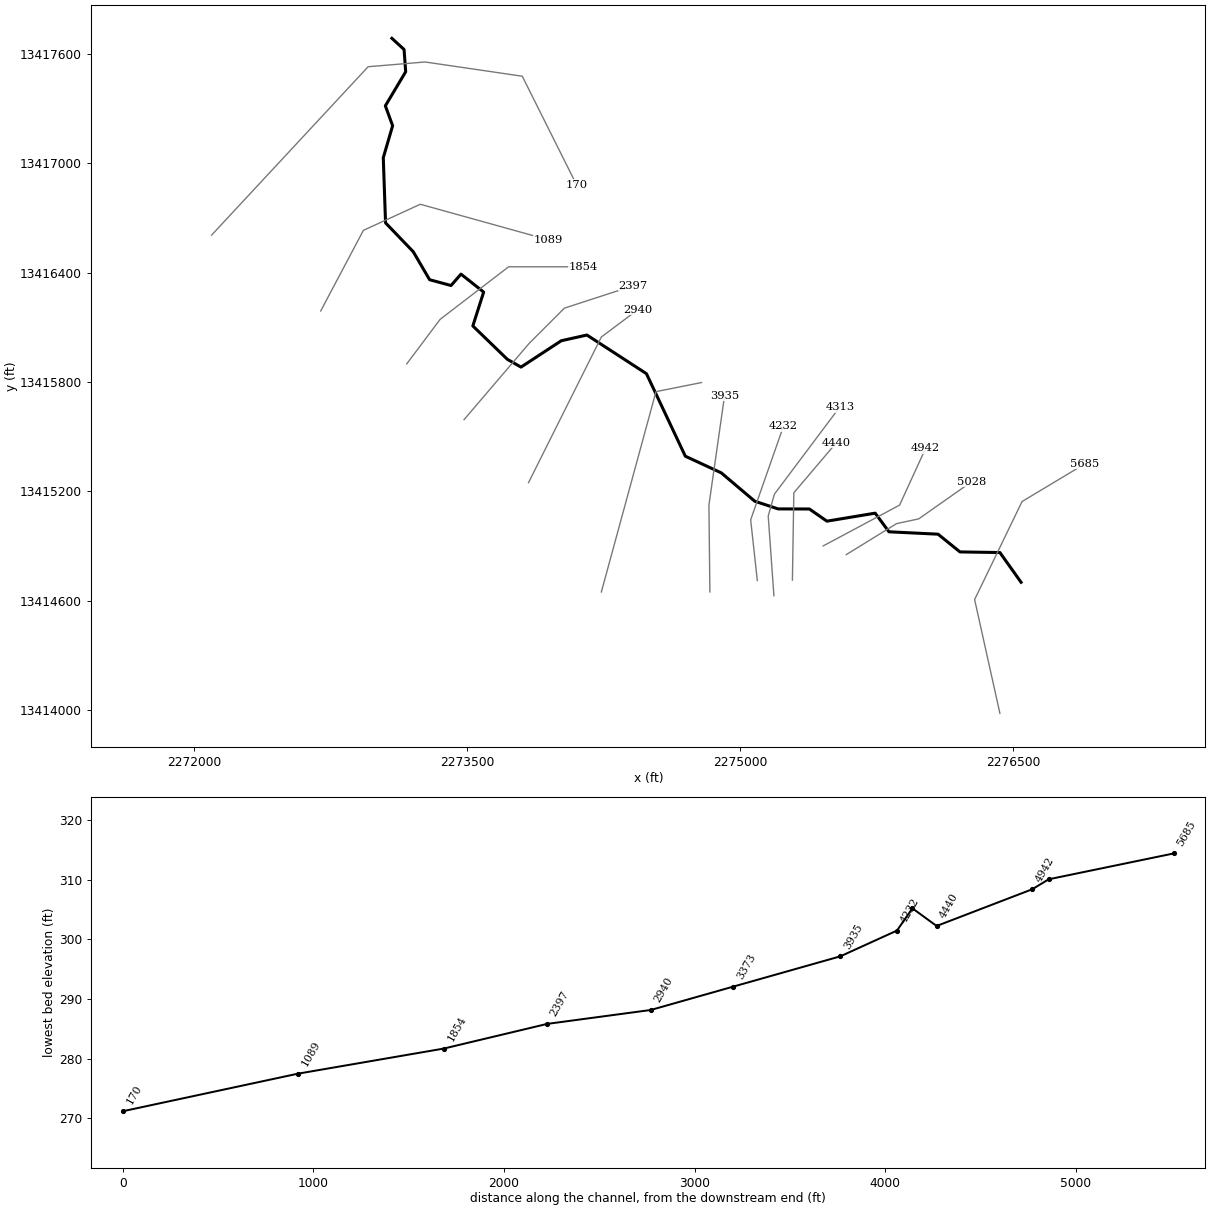
--- UNT034 IN SUCR.prj (project) ---

Proj Title=UNT034 IN SUCR Base Level Engineering
Current Plan=p01
Default Exp/Contr=0.3,0.1
English Units
Geom File=g01
Flow File=f01
Plan File=p01
Y Axis Title=Elevation
X Axis Title(PF)=Main Channel Distance
X Axis Title(XS)=Station
BEGIN DESCRIPTION:
UNT034 IN SUCR
END DESCRIPTION:
DSS Export Rating Curves= 0
DSS Export Rating Curve Sorted= 0
DSS Export Volume Flow Curves= 0
DXF OffsetX= 0
DXF OffsetY= 0
DXF ScaleX= 1
DXF ScaleY= 10

--- UNT034 IN SUCR.p01 (plan) ---

Plan Title=Multiple Run
Short Identifier=Multiple
Geom File=g01
Flow File=f01
Subcritical Flow
K Sum by GR= 0
Std Step Tol= 0.01
Critical Tol= 0.01
Num of Std Step Trials= 20
Max Error Tol= 0.3
Flow Tol Ratio= 0.001
Split Flow NTrial= 30
Split Flow Tol= 0.02
Split Flow Ratio= 0.02
Log Output Level= 0
Friction Slope Method= 1
Unsteady Friction Slope Method= 2
Unsteady Bridges Friction Slope Method= 1
Parabolic Critical Depth
Global Vel Dist=  1 , 1 , 1
Global Log Level= 0
CheckData=True
Encroach Param= -1, 0, 0, 0
BEGIN DESCRIPTION:
Multiple Run
END DESCRIPTION:

--- UNT034 IN SUCR.f01 (steady flow) ---

Flow Title=Multiple
Number of Profiles=7
Profile Names=10-year,25-year,50-year,1pct_min,100-year,1pct_plu,500-year
River Rch & RM= UNT034 IN SUCR,Reach-1,5685
     176     237     285     253     343     463     501
River Rch & RM= UNT034 IN SUCR,Reach-1,5028
     229     313     382     343     464     628     695
Boundary for River Rch & Prof#=UNT034 IN SUCR,Reach-1,1
Up Type=0
Dn Type=3
Dn Slope=0.005
Boundary for River Rch & Prof#=UNT034 IN SUCR,Reach-1,2
Up Type=0
Dn Type=3
Dn Slope=0.005
Boundary for River Rch & Prof#=UNT034 IN SUCR,Reach-1,3
Up Type=0
Dn Type=3
Dn Slope=0.005
Boundary for River Rch & Prof#=UNT034 IN SUCR,Reach-1,4
Up Type=0
Dn Type=3
Dn Slope=0.005
Boundary for River Rch & Prof#=UNT034 IN SUCR,Reach-1,5
Up Type=0
Dn Type=3
Dn Slope=0.005
Boundary for River Rch & Prof#=UNT034 IN SUCR,Reach-1,6
Up Type=0
Dn Type=3
Dn Slope=0.005
Boundary for River Rch & Prof#=UNT034 IN SUCR,Reach-1,7
Up Type=0
Dn Type=3
Dn Slope=0.005

--- UNT034 IN SUCR.g01 (geometry) ---

Geom Title=Existing Conditions
Program Version=4.10

River Reach=UNT034 IN SUCR  ,Reach-1
Reach XY= 30
      2276542.42     13414700.06      2276426.25     13414863.32
      2276206.76      13414866.8      2276086.59     13414964.14
      2275817.03     13414977.24      2275741.24      13415079.6
      2275476.31     13415035.59      2275379.99      13415102.5
      2275208.12     13415103.03      2275079.99     13415145.21
      2274896.14     13415300.94      2274698.85     13415392.35
      2274485.31     13415845.47      2274158.48     13416057.71
      2274017.86     13416026.46      2273796.59     13415881.59
      2273721.43     13415924.43      2273532.09     13416107.67
      2273591.51     13416293.65      2273466.97     13416392.18
      2273412.37     13416329.58      2273294.69     13416361.49
      2273204.87     13416515.11      2273052.76     13416673.54
      2273040.32     13417031.32      2273091.64     13417207.03
      2273051.68     13417316.32      2273163.29     13417503.33
      2273154.42     13417625.48      2273087.72     13417686.86

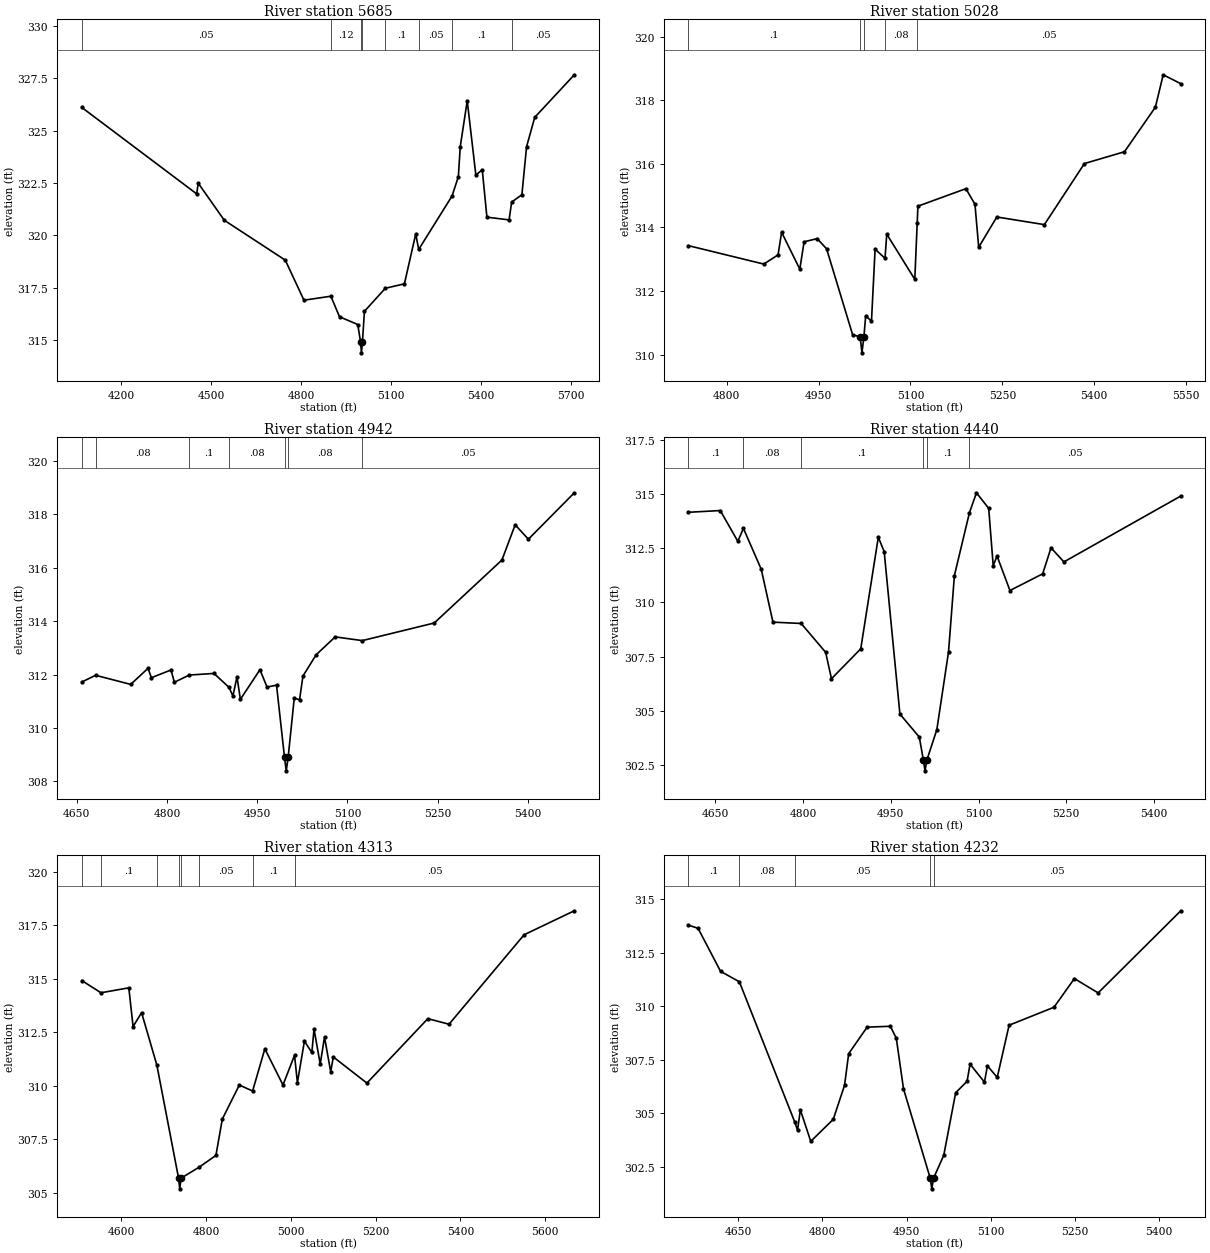
Type RM Length L Ch R = 1 ,5685    ,657,657,657
BEGIN DESCRIPTION:
UNT034 IN SUCR 10.0
END DESCRIPTION:
XS GIS Cut Line= 4
      2276426.23     13413980.21      2276287.35     13414605.17
      2276547.76     13415143.37      2276893.85     13415351.02
#Sta/Elev= 30
  4069.6   326.1  4452.4  321.98  4457.6  322.49  4544.6  320.72  4747.8  318.82
    4810  316.91  4899.7   317.1  4928.5  316.12  4989.4  315.75  4998.9   314.9
  5001.6   314.4  5004.9   314.9  5011.6  316.38  5081.3  317.48  5144.9  317.69
  5182.6  320.07  5192.5  319.33  5303.7  321.88  5324.7   322.8    5331  324.23
  5354.3  326.42    5383  322.88  5404.4  323.13  5419.9  320.87  5493.8  320.74
  5502.4  321.59  5536.5  321.94  5552.1  324.23  5579.3  325.63  5711.3  327.66
#Mann= 8 ,-1 , 0
  4069.6     .05       0  4899.7     .12       0  4998.9     .07       0
  5004.9     .12       0  5081.3      .1       0  5192.5     .05       0
  5303.7      .1       0  5502.4     .05       0
Bank Sta=4998.9,5004.9
XS Rating Curve= 0 ,0
Exp/Cntr=0.3,0.1

Type RM Length L Ch R = 1 ,5028    ,86,86,86
BEGIN DESCRIPTION:
UNT034 IN SUCR 9.0
END DESCRIPTION:
XS GIS Cut Line= 4
      2275582.82     13414852.07      2275858.85     13415022.19
      2275980.37     13415048.24      2276271.18     13415252.49
#Sta/Elev= 30
  4737.4  313.43  4860.6  312.85  4883.9  313.14  4889.7  313.85  4919.4  312.69
  4926.4  313.55  4947.7  313.65  4963.1  313.33  5005.6  310.63    5018  310.56
  5020.8  310.06    5024  310.56  5026.9  311.22  5036.4  311.06  5042.3  313.32
  5058.5  313.03  5061.3  313.79  5107.1  312.37    5111  314.13  5112.2  314.67
  5190.5  315.22  5205.3  314.73  5211.4  313.38    5241  314.33  5318.6  314.09
    5384  316.01  5449.3  316.38  5499.8  317.78  5512.6   318.8  5541.3  318.52
#Mann= 5 ,-1 , 0
  4737.4      .1       0    5018     .07       0    5024      .1       0
  5058.5     .08       0    5111     .05       0
Bank Sta=5018,5024
XS Rating Curve= 0 ,0
Exp/Cntr=0.3,0.1

Type RM Length L Ch R = 1 ,4942    ,502,502,502
BEGIN DESCRIPTION:
UNT034 IN SUCR 8.0
END DESCRIPTION:
XS GIS Cut Line= 3
      2275456.08      13414899.8      2275875.34     13415123.76
      2276018.57     13415436.27
#Sta/Elev= 30
  4658.3  311.72  4681.2  311.97  4739.5  311.63  4768.3  312.23    4774  311.88
  4806.6  312.17  4812.2  311.71  4837.1  311.98  4878.1  312.04  4902.9  311.52
  4909.6   311.2  4916.3  311.91    4922  311.07  4954.5  312.18  4966.3  311.53
  4982.1   311.6  4995.4  308.89  4998.2  308.39  5001.4  308.89  5011.6  311.12
  5020.4  311.05    5026  311.94    5048  312.74  5079.6  313.41  5124.7  313.27
  5244.4  313.93    5357  316.29    5379  317.61    5401  317.07  5477.4  318.81
#Mann= 7 ,-1 , 0
  4658.3      .1       0  4681.2     .08       0  4837.1      .1       0
  4902.9     .08       0  4995.4     .07       0  5001.4     .08       0
  5124.7     .05       0
Bank Sta=4995.4,5001.4
XS Rating Curve= 0 ,0
Exp/Cntr=0.3,0.1

Type RM Length L Ch R = 1 ,4440    ,127,127,127
BEGIN DESCRIPTION:
UNT034 IN SUCR 6.1
END DESCRIPTION:
XS GIS Cut Line= 3
       2275286.8     13414712.28      2275294.61     13415191.47
        2275529.     13415467.53
#Sta/Elev= 30
  4604.2  314.16  4658.8  314.24  4688.8  312.82  4698.3  313.42  4728.8  311.53
  4748.8  309.09    4797  309.03  4838.8   307.7  4848.8  306.48  4898.8  307.86
  4928.8  313.01  4938.8  312.35  4965.7  304.85  4998.8  303.79  5005.8  302.73
  5008.6  302.23  5011.8  302.73  5028.8  304.13  5048.8  307.72  5058.8  311.24
  5084.5  314.14  5096.5  315.06  5117.4  314.34  5125.1   311.7  5131.7  312.14
  5153.7  310.55  5209.6  311.32  5223.9  312.52  5245.9  311.87  5445.6  314.91
#Mann= 6 ,-1 , 0
  4604.2      .1       0  4698.3     .08       0    4797      .1       0
  5005.8     .07       0  5011.8      .1       0  5084.5     .05       0
Bank Sta=5005.8,5011.8
XS Rating Curve= 0 ,0
Exp/Cntr=0.3,0.1

Type RM Length L Ch R = 1 ,4313    ,81,81,81
BEGIN DESCRIPTION:
UNT034 IN SUCR 7.0
END DESCRIPTION:
XS GIS Cut Line= 4
      2275185.24     13414626.36      2275153.99     13415063.86
      2275187.84     13415183.65      2275546.88     13415662.37
#Sta/Elev= 30
  4507.2  314.92  4552.2  314.35    4618  314.58    4628  312.77  4648.1  313.42
  4684.2  310.96  4735.3  305.69    4738  305.19  4741.3  305.69  4782.9  306.19
  4823.4  306.75  4838.5  308.45  4878.6  310.04  4909.9  309.76  4938.8  311.73
  4981.6  310.04  5008.8  311.43  5015.6  310.15  5032.1  312.09  5049.6  311.56
  5054.8  312.65  5069.4  311.02  5079.5  312.28  5094.1  310.66  5100.3  311.35
  5179.5  310.13  5323.2  313.14  5373.2  312.88  5550.3  317.06  5668.7  318.18
#Mann= 8 ,-1 , 0
  4507.2     .05       0  4552.2      .1       0  4684.2     .08       0
  4735.3     .07       0  4741.3     .08       0  4782.9     .05       0
  4909.9      .1       0  5008.8     .05       0
Bank Sta=4735.3,4741.3
XS Rating Curve= 0 ,0
Exp/Cntr=0.3,0.1

Type RM Length L Ch R = 1 ,4232    ,297,297,297
BEGIN DESCRIPTION:
UNT034 IN SUCR 6.2
END DESCRIPTION:
XS GIS Cut Line= 3
      2275094.09     13414709.69      2275057.63     13415043.03
      2275237.32     13415556.04
#Sta/Elev= 30
  4560.6  313.79    4578  313.64  4618.1  311.63  4651.7  311.14  4750.6  304.58
  4755.5  304.21  4760.6  305.15  4779.1  303.68  4819.3  304.71  4839.4   306.3
  4846.8  307.78  4879.7  309.02  4921.2  309.06  4931.8   308.5  4944.6  306.14
  4992.3  301.96  4995.1  301.46  4998.3  301.96  5016.5  303.03  5037.7  305.95
  5058.1  306.49  5063.4  307.29  5089.1  306.45  5094.4  307.21  5111.9  306.67
  5133.1  309.11  5213.2  309.95  5249.6  311.29    5292  310.62  5439.5  314.46
#Mann= 5 ,-1 , 0
  4560.6      .1       0  4651.7     .08       0  4750.6     .05       0
  4992.3     .03       0  4998.3     .05       0
Bank Sta=4992.3,4998.3
XS Rating Curve= 0 ,0
Exp/Cntr=0.3,0.1

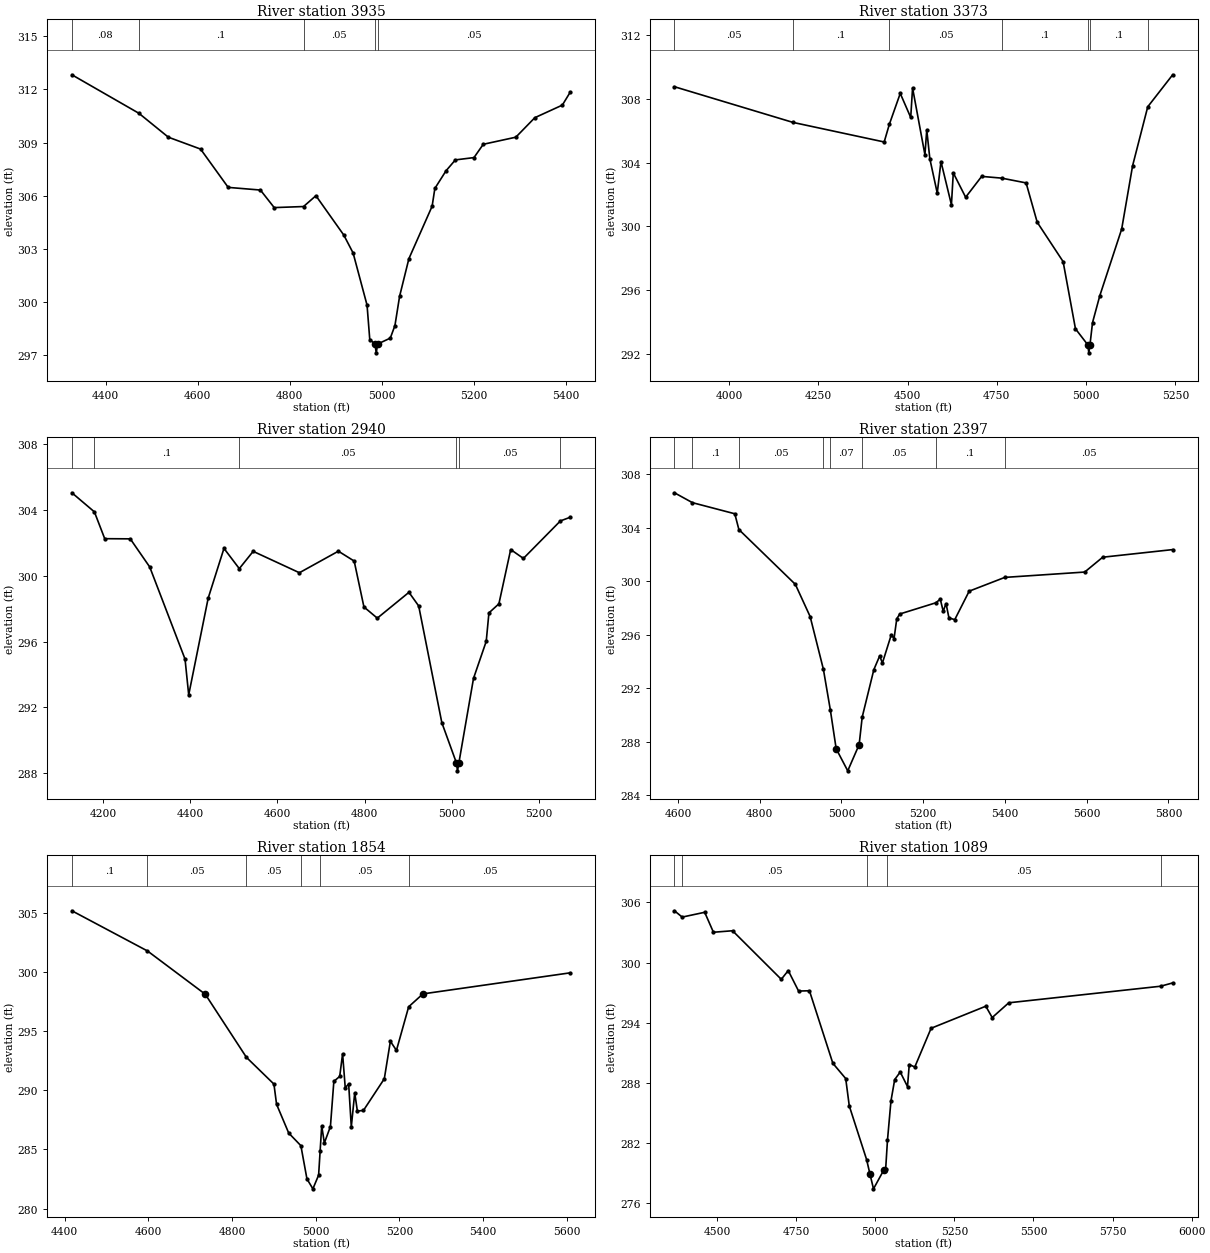
Type RM Length L Ch R = 1 ,3935    ,562,562,562
BEGIN DESCRIPTION:
UNT034 IN SUCR 6.0
END DESCRIPTION:
XS GIS Cut Line= 3
      2274833.67     13414647.24      2274828.46     13415123.76
      2274914.16     13415723.62
#Sta/Elev= 30
  4326.5  312.82    4472  310.65  4536.1   309.3  4606.1  308.63  4666.1  306.47
  4736.1  306.32  4766.1  305.33  4829.8  305.39  4856.7     306  4917.3  303.78
  4937.5  302.77  4967.8  299.83  4973.7  297.89    4985  297.64  4987.7  297.14
    4991  297.64  5018.3  297.97  5028.4  298.68  5038.5  300.33  5058.7  302.45
  5109.2  305.41  5115.1  306.41  5139.5  307.41  5159.7  308.02  5200.1  308.15
  5220.3   308.9    5291   309.3  5332.3   310.4  5392.1  311.11    5409  311.83
#Mann= 5 ,-1 , 0
  4326.5     .08       0    4472      .1       0  4829.8     .05       0
    4985     .03       0    4991     .05       0
Bank Sta=4985,4991
XS Rating Curve= 0 ,0
Exp/Cntr=0.3,0.1

Type RM Length L Ch R = 1 ,3373    ,433,433,433
BEGIN DESCRIPTION:
UNT034 IN SUCR 5.0
END DESCRIPTION:
XS GIS Cut Line= 3
      2274237.73     13414646.88      2274537.72     13415746.85
      2274787.72     13415796.86
#Sta/Elev= 30
  3847.2  308.77    4179  306.53  4434.5   305.3  4449.1  306.42  4479.5  308.35
  4508.8  306.84    4514  308.69  4548.6   304.5  4553.7  306.06  4562.4  304.24
  4583.1  302.09  4593.5  304.07  4622.8  301.36    4628  303.36  4662.6  301.83
  4707.5  303.14  4763.6  303.03  4831.9  302.73    4863  300.26  4935.5  297.79
  4970.1  293.57  5004.7  292.56  5007.5  292.06  5010.7  292.56  5017.9  293.96
  5038.3  295.65  5099.5  299.83  5130.1  303.81  5172.5  307.51  5242.3  309.52
#Mann= 7 ,-1 , 0
  3847.2     .05       0    4179      .1       0  4449.1     .05       0
  4763.6      .1       0  5004.7     .07       0  5010.7      .1       0
  5172.5     .05       0
Bank Sta=5004.7,5010.7
XS Rating Curve= 0 ,0
Exp/Cntr=0.3,0.1

Type RM Length L Ch R = 1 ,2940    ,543,543,543
BEGIN DESCRIPTION:
UNT034 IN SUCR 4.0
END DESCRIPTION:
XS GIS Cut Line= 3
      2273837.74      13415246.9      2274237.72     13416046.85
      2274437.74     13416196.87
#Sta/Elev= 30
  4127.8  305.04  4179.5  303.88  4203.2  302.25  4261.9  302.24  4306.6  300.53
  4387.7  294.93  4396.1  292.76  4440.8  298.63  4477.1  301.66  4512.3  300.43
  4544.2  301.48  4650.4  300.18  4739.9  301.49  4776.2  300.89  4798.6   298.1
  4829.3  297.42    4902  298.99  4924.4  298.16  4977.5  291.07  5010.8  288.64
  5013.5  288.14  5016.8  288.64  5050.3  293.76  5079.5  296.01  5085.7  297.74
  5108.6  298.29  5135.7  301.59  5164.9  301.05  5249.9  303.33  5272.2  303.55
#Mann= 6 ,-1 , 0
  4127.8     .05       0  4179.5      .1       0  4512.3     .05       0
  5010.8     .03       0  5016.8     .05       0  5249.9      .1       0
Bank Sta=5010.8,5016.8
XS Rating Curve= 0 ,0
Exp/Cntr=0.3,0.1

Type RM Length L Ch R = 1 ,2397    ,543,543,543
BEGIN DESCRIPTION:
UNT034 IN SUCR 3.0
END DESCRIPTION:
XS GIS Cut Line= 4
      2273483.76     13415593.13      2273842.22      13416012.8
      2274034.56     13416205.14      2274410.51     13416327.54
#Sta/Elev= 30
  4591.2  306.61  4635.3  305.87  4738.9  305.04  4748.9  303.86  4887.1  299.76
  4923.3  297.35  4955.7  293.41  4972.7  290.37    4987  287.46  5015.3  285.81
  5043.2  287.77  5050.7  289.83  5079.2  293.38  5093.5  294.41  5100.1  293.87
    5122     296  5128.6   295.7  5135.3  297.18  5142.5  297.54  5230.8  298.38
  5241.8  298.65  5248.9  297.75  5255.9  298.32    5263  297.25  5277.2  297.12
  5312.5  299.25  5399.6  300.28  5595.2  300.68  5639.3  301.79  5810.5  302.36
#Mann= 8 ,-1 , 0
  4591.2     .05       0  4635.3      .1       0  4748.9     .05       0
  4955.7      .1       0  4972.7     .07       0  5050.7     .05       0
  5230.8      .1       0  5399.6     .05       0
Bank Sta=4987,5043.2
XS Rating Curve= 0 ,0
Exp/Cntr=0.3,0.1

Type RM Length L Ch R = 1 ,1854    ,765,765,765
BEGIN DESCRIPTION:
UNT034 IN SUCR 2.0
END DESCRIPTION:
XS GIS Cut Line= 4
      2273169.05     13415899.15      2273352.64     13416143.94
      2273728.57     13416432.44      2274139.51     13416432.44
#Sta/Elev= 30
  4417.2  305.19  4597.9  301.79    4736  298.13  4834.4  292.79  4900.1  290.53
  4906.4  288.82  4935.4  286.39  4964.5  285.32    4979  282.51  4993.2  281.67
  5006.9  282.83 5010.43  284.83  5014.3  286.99  5020.6  285.55  5035.1  286.94
  5043.3  290.76  5057.3  291.18  5064.2  293.09  5070.5  290.23  5078.7  290.53
    5085  286.91  5093.2  289.79  5099.5  288.25    5114   288.3  5163.9  290.98
  5178.4  294.15  5192.9  293.38  5222.1  297.07  5256.2  298.16    5608  299.94
#Mann= 6 ,-1 , 0
  4417.2      .1       0  4597.9     .05       0  4834.4     .05       0
  4964.5     .03       0 5010.43     .05       0  5222.1     .05       0
Bank Sta=4736,5256.2
XS Rating Curve= 0 ,0
Exp/Cntr=0.3,0.1

Type RM Length L Ch R = 1 ,1089    ,919,919,919
BEGIN DESCRIPTION:
Mapping XS 9c18efad
END DESCRIPTION:
XS GIS Cut Line= 4
      2272696.72      13416189.8       2272931.1     13416632.52
       2273243.6     13416775.75      2273946.69     13416580.44
#Sta/Elev= 30
  4365.6  305.17  4390.1  304.54  4461.2  305.02  4488.8  303.03  4549.2  303.18
  4703.2  298.34  4725.2  299.21  4757.9  297.17  4792.2   297.2  4866.2  289.97
  4906.8  288.45  4918.1  285.72  4972.8  280.38 4983.75  278.89  4994.6  277.46
  5027.6  279.36  5033.1  279.45  5038.8  282.31  5049.8  286.22  5061.6  288.35
  5079.1   289.1  5102.1  287.65  5107.6  289.85  5125.1   289.6  5176.6  293.46
  5349.5  295.66  5369.7  294.53  5422.1     296  5901.6  297.65    5940  297.98
#Mann= 5 ,-1 , 0
  4365.6     .05       0  4390.1     .05       0  4972.8     .03       0
  5038.8     .05       0  5901.6     .05       0
Bank Sta=4983.75,5027.6
XS Rating Curve= 0 ,0
Exp/Cntr=0.3,0.1

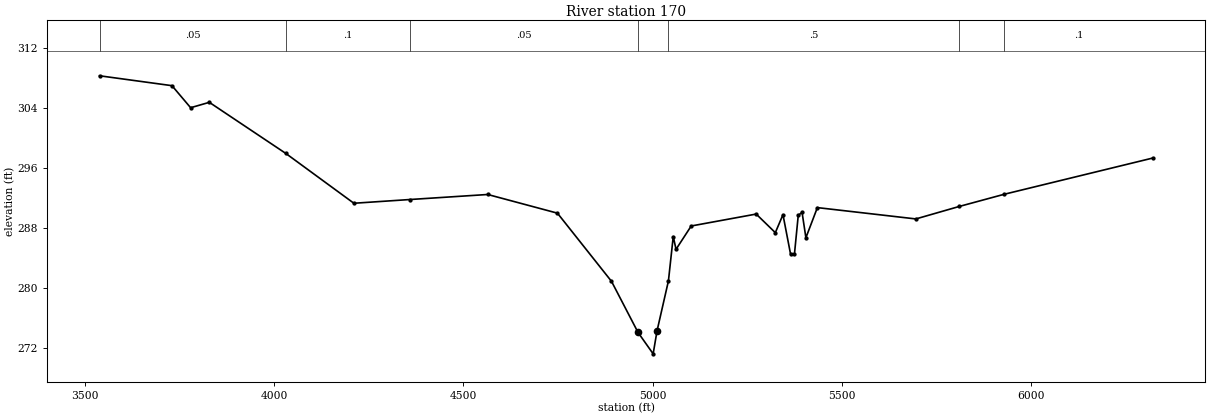
Type RM Length L Ch R = 1 ,170     ,0,0,0
BEGIN DESCRIPTION:
UNT034 IN SUCR 1.0
END DESCRIPTION:
XS GIS Cut Line= 5
      2272097.78     13416606.49      2272957.14     13417530.95
      2273269.64       13417557.      2273803.49     13417478.87
      2274102.36     13416881.14
#Sta/Elev= 30
  3538.5  308.24    3730  306.92  3779.3  303.98  3828.7   304.7    4031  297.88
  4210.8  291.24  4359.3  291.74  4564.5  292.41  4748.7  289.92  4891.6  280.83
  4961.8  274.01  5001.7  271.16    5012  274.23  5042.1  280.89  5054.8   286.8
  5062.2   285.1  5102.3  288.21    5274   289.8  5324.6  287.32  5344.8  289.72
    5365  284.42  5375.1  284.44  5385.2  289.64  5395.3  290.02  5405.4  286.64
  5435.7  290.66    5696  289.15  5810.4  290.81  5929.6  292.44  6322.1  297.27
#Mann= 7 ,-1 , 0
  3538.5     .05       0    4031      .1       0  4359.3     .05       0
  4961.8     .03       0  5042.1      .5       0  5810.4     .08       0
  5929.6      .1       0
Bank Sta=4961.8,5012
XS Rating Curve= 0 ,0
Exp/Cntr=0.3,0.1

Chan Stop Cuts=-1
Use User Specified Reach Order=0
Composite Channel Slope=5