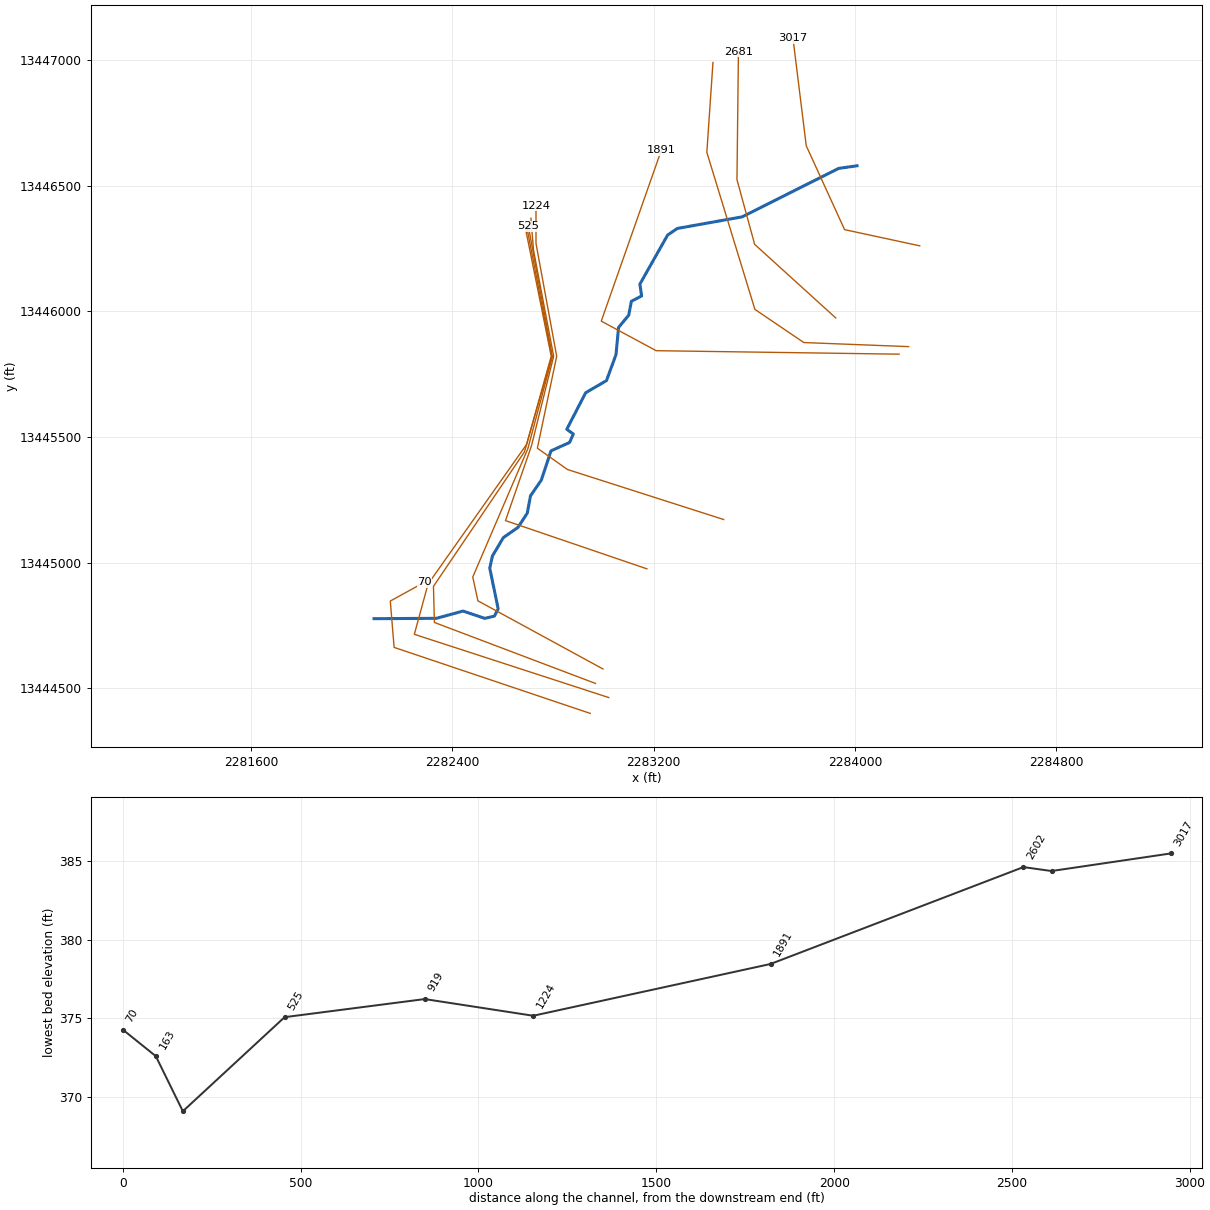
--- UNT036 IN SUCR.prj (project) ---

Proj Title=UNT036 IN SUCR Base Level Engineering
Current Plan=p01
Default Exp/Contr=0.3,0.1
English Units
Geom File=g01
Flow File=f01
Plan File=p01
Y Axis Title=Elevation
X Axis Title(PF)=Main Channel Distance
X Axis Title(XS)=Station
BEGIN DESCRIPTION:
UNT036 IN SUCR
END DESCRIPTION:
DSS Export Rating Curves= 0
DSS Export Rating Curve Sorted= 0
DSS Export Volume Flow Curves= 0
DXF OffsetX= 0
DXF OffsetY= 0
DXF ScaleX= 1
DXF ScaleY= 10

--- UNT036 IN SUCR.p01 (plan) ---

Plan Title=Multiple Run
Short Identifier=Multiple
Geom File=g01
Flow File=f01
Subcritical Flow
K Sum by GR= 0
Std Step Tol= 0.01
Critical Tol= 0.01
Num of Std Step Trials= 20
Max Error Tol= 0.3
Flow Tol Ratio= 0.001
Split Flow NTrial= 30
Split Flow Tol= 0.02
Split Flow Ratio= 0.02
Log Output Level= 0
Friction Slope Method= 1
Unsteady Friction Slope Method= 2
Unsteady Bridges Friction Slope Method= 1
Parabolic Critical Depth
Global Vel Dist=  1 , 1 , 1
Global Log Level= 0
CheckData=True
Encroach Param= -1, 0, 0, 0
BEGIN DESCRIPTION:
Multiple Run
END DESCRIPTION:

--- UNT036 IN SUCR.f01 (steady flow) ---

Flow Title=Multiple
Number of Profiles=7
Profile Names=10-year,25-year,50-year,1pct_min,100-year,1pct_plu,500-year
River Rch & RM= UNT036 IN SUCR,Reach-1,3017
     229     312     381     341     462     624     687
River Rch & RM= UNT036 IN SUCR,Reach-1,1891
     303     420     517     468     633     857     962
River Rch & RM= UNT036 IN SUCR,Reach-1,70
     652     931    1168    1074    1452    1964    2276
Boundary for River Rch & Prof#=UNT036 IN SUCR,Reach-1,1
Up Type=0
Dn Type=3
Dn Slope=0.005
Boundary for River Rch & Prof#=UNT036 IN SUCR,Reach-1,2
Up Type=0
Dn Type=3
Dn Slope=0.005
Boundary for River Rch & Prof#=UNT036 IN SUCR,Reach-1,3
Up Type=0
Dn Type=3
Dn Slope=0.005
Boundary for River Rch & Prof#=UNT036 IN SUCR,Reach-1,4
Up Type=0
Dn Type=3
Dn Slope=0.005
Boundary for River Rch & Prof#=UNT036 IN SUCR,Reach-1,5
Up Type=0
Dn Type=3
Dn Slope=0.005
Boundary for River Rch & Prof#=UNT036 IN SUCR,Reach-1,6
Up Type=0
Dn Type=3
Dn Slope=0.005
Boundary for River Rch & Prof#=UNT036 IN SUCR,Reach-1,7
Up Type=0
Dn Type=3
Dn Slope=0.005

--- UNT036 IN SUCR.g01 (geometry) ---

Geom Title=Existing Conditions
Program Version=4.10

River Reach=UNT036 IN SUCR  ,Reach-1
Reach XY= 30
      2284007.76      13446579.2      2283934.95     13446568.84
      2283551.36     13446375.94       2283293.7     13446329.75
      2283255.33     13446303.52      2283145.14     13446108.18
      2283152.07      13446061.1      2283111.34     13446039.91
      2283100.77     13445984.61      2283060.31     13445935.81
       2283050.3      13445827.8      2283012.36     13445724.12
      2282929.86     13445676.14       2282854.6     13445530.45
       2282880.7     13445511.79      2282865.63     13445477.95
      2282791.87     13445444.52      2282753.66     13445328.54
       2282710.6     13445265.66      2282697.72     13445196.85
      2282660.98     13445140.07      2282602.64     13445099.34
      2282559.17     13445026.16      2282548.67     13444977.44
      2282582.07     13444816.27      2282567.34      13444787.2
      2282528.84     13444777.83       2282442.6     13444807.09
      2282336.71     13444778.11      2282088.94     13444776.75

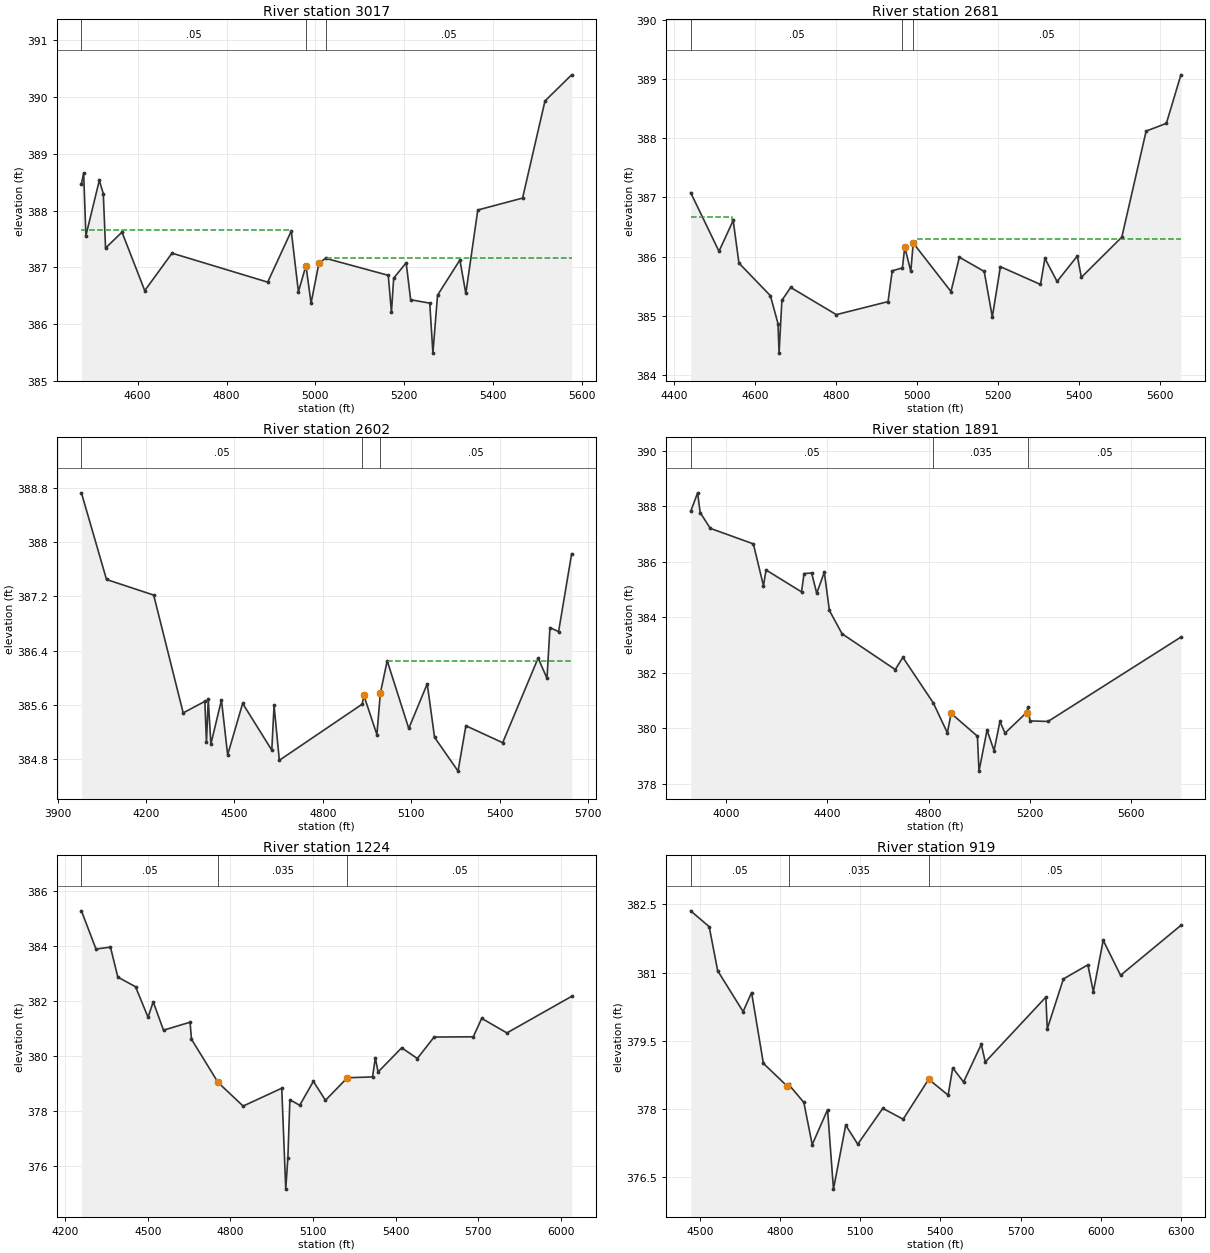
Type RM Length L Ch R = 1 ,3017    ,336,336,336
BEGIN DESCRIPTION:
UNT036 IN SUCR 2.0
END DESCRIPTION:
XS GIS Cut Line= 4
      2284256.99     13446260.66      2283958.35     13446325.08
      2283806.07      13446658.9      2283753.37     13447086.44
#Sta/Elev= 30
  4473.5  388.47  4478.5  388.66  4483.6  387.56  4513.7  388.53  4522.7   388.3
  4527.8  387.34  4564.8  387.62    4616  386.59  4677.4  387.25  4892.7  386.74
  4945.8  387.64  4961.8  386.57  4978.8  387.03  4990.3  386.37  5007.9  387.07
  5022.8  387.16    5164  386.86  5171.2  386.21  5176.2  386.81  5204.3  387.08
  5214.4  386.43  5257.4  386.37  5264.5  385.49  5274.9  386.51  5325.2  387.13
  5338.6  386.54  5365.5  388.01  5466.3  388.22  5516.7  389.93  5576.7  390.39
#Mann= 3 ,-1 , 0
  4473.5     .05       0  4978.8     .03       0  5022.8     .05       0
#XS Ineff= 2 , 0
       0 4945.08  387.65 5026.44       0  387.17
Permanent Ineff=
       T       T
Bank Sta=4978.8,5007.9
XS Rating Curve= 0 ,0
Exp/Cntr=0.3,0.1

Type RM Length L Ch R = 1 ,2681    ,79,79,79
BEGIN DESCRIPTION:
Mapping XS 8a2481
END DESCRIPTION:
XS GIS Cut Line= 4
      2283923.19      13445973.7      2283601.09     13446266.51
      2283530.82      13446524.2      2283536.66     13447032.76
#Sta/Elev= 30
  4441.8  387.08  4511.7  386.09  4546.8  386.61    4561  385.89  4638.7  385.34
  4657.4  384.87  4660.1  384.37  4667.1  385.26  4688.7  385.48  4801.6  385.02
  4929.3  385.24  4939.7  385.76 4964.75  385.81  4970.7  386.16  4985.6  385.75
  4991.5  386.23  5084.8  385.41  5105.5  385.99  5166.9  385.75  5186.9  384.98
  5206.9  385.83  5305.9  385.53  5316.9  385.97  5346.9  385.58  5396.9  386.01
  5406.9  385.65  5506.9  386.33  5566.9  388.12  5616.9  388.25  5652.8  389.07
#Mann= 3 ,-1 , 0
  4441.8     .05       0 4964.75    .035       0  4991.5     .05       0
#XS Ineff= 2 , 0
       0 4544.75  386.67 4997.97       0   386.3
Permanent Ineff=
       T       T
Bank Sta=4970.7,4991.5
XS Rating Curve= 0 ,0
Exp/Cntr=0.3,0.1

Type RM Length L Ch R = 1 ,2602    ,711,711,711
BEGIN DESCRIPTION:
Mapping XS 8a24810f
END DESCRIPTION:
XS GIS Cut Line= 5
      2284212.73     13445859.51      2283796.55     13445875.68
      2283602.11     13446007.62      2283411.13     13446632.62
      2283435.44     13446990.29
#Sta/Elev= 30
    3981  388.73  4066.1  387.45  4226.2  387.22  4326.3  385.48  4399.8  385.65
  4405.3  385.05  4411.4  385.68  4420.3  385.02  4456.2  385.67  4477.2  384.86
  4528.1  385.62    4627  384.93  4634.7  385.59  4652.6  384.78    4934  385.61
  4939.3  385.74 4983.65  385.16 4995.38  385.77  5018.6  386.25  5091.8  385.25
  5154.5  385.91  5179.3  385.12  5259.1  384.62  5285.6  385.29  5410.5  385.04
  5530.8  386.29  5560.9  385.99  5570.9  386.74  5600.2  386.68  5644.5  387.83
#Mann= 3 ,-1 , 0
    3981     .05       0    4934    .035       0 4995.38     .05       0
#XS Ineff= 2 , 0
       0 4935.59  385.62 5020.34       0  386.24
Permanent Ineff=
       T       T
Bank Sta=4939.3,4995.38
XS Rating Curve= 0 ,0
Exp/Cntr=0.3,0.1

Type RM Length L Ch R = 1 ,1891    ,667,667,667
BEGIN DESCRIPTION:
Mapping XS 07a5f3e1
END DESCRIPTION:
XS GIS Cut Line= 4
      2284175.03     13445829.44      2283209.78     13445843.33
      2282991.68     13445960.97       2283230.6     13446641.91
#Sta/Elev= 30
  3861.1  387.82  3888.4  388.49  3898.4  387.78  3938.4  387.21  4108.4  386.65
  4148.4  385.14  4158.4  385.71  4298.5  384.92  4308.5  385.58  4338.5   385.6
  4358.5  384.87  4388.5  385.63  4408.5  384.25  4458.5  383.41  4668.5  382.12
  4698.5  382.56  4818.5  380.92  4874.2  379.84  4888.9  380.54  4992.7  379.72
    4999  378.46  5030.8  379.94  5058.4   379.2  5081.6  380.25  5101.7  379.83
  5186.5  380.57  5191.8  380.76  5200.3  380.27  5271.3  380.25  5795.9  383.29
#Mann= 3 ,-1 , 0
  3861.1     .05       0  4818.5    .035       0  5191.8     .05       0
Bank Sta=4888.9,5186.5
XS Rating Curve= 0 ,0
Exp/Cntr=0.3,0.1

Type RM Length L Ch R = 1 ,1224    ,305,305,305
BEGIN DESCRIPTION:
Mapping XS 5fc9c2c3
END DESCRIPTION:
XS GIS Cut Line= 6
      2283478.08     13445171.34      2282857.31     13445370.46
      2282737.84     13445455.24      2282814.59      13445821.2
      2282732.42     13446270.14      2282732.42      13446420.5
#Sta/Elev= 30
  4258.8  385.29  4311.7   383.9  4364.2  383.97    4391  382.88  4455.2  382.53
  4500.7  381.42  4519.4  381.98  4556.8  380.95  4653.2  381.24  4658.4  380.62
  4754.8  379.05  4845.9  378.19  4986.1  378.84  5000.6  375.17  5008.3  376.31
  5015.6  378.42  5051.3  378.22  5100.9  379.09  5144.7   378.4  5224.2  379.22
  5315.6  379.25  5325.8  379.94  5335.9  379.43  5421.6  380.31  5478.2  379.92
  5539.2   380.7  5681.5  380.71    5712  381.38  5803.5  380.85  6038.5  382.18
#Mann= 3 , 0 , 0
  4258.8     .05       0  4754.8    .035       0  5224.2     .05       0
Bank Sta=4754.8,5224.2
XS Rating Curve= 0 ,0
Exp/Cntr=0.3,0.1

Type RM Length L Ch R = 1 ,919     ,394,394,394
BEGIN DESCRIPTION:
Mapping XS 5fc9c
END DESCRIPTION:
XS GIS Cut Line= 6
      2283173.16     13444975.08      2282611.27     13445167.06
      2282714.38     13445464.45      2282802.57      13445821.2
       2282722.4     13446244.09      2282712.37     13446370.37
#Sta/Elev= 30
  4466.2  382.36  4535.4  382.01  4567.1  381.04  4662.2  380.14  4693.9  380.56
    4738     379  4826.7   378.5    4832  378.54  4889.3  378.14  4920.6  377.21
    4978  377.98  5000.1  376.23  5045.9  377.64  5090.8  377.22  5184.6  378.01
  5260.7  377.77  5356.1  378.65  5428.9   378.3  5446.1   378.9  5486.6  378.59
  5552.9  379.42  5567.8  379.03  5794.5  380.46  5799.6  379.76    5860  380.86
  5951.4  381.17    5972  380.58  6008.8  381.71  6073.8  380.94  6299.4  382.04
#Mann= 3 ,-1 , 0
  4466.2     .05       0    4832    .035       0  5356.1     .05       0
Bank Sta=4826.7,5356.1
XS Rating Curve= 0 ,0
Exp/Cntr=0.3,0.1

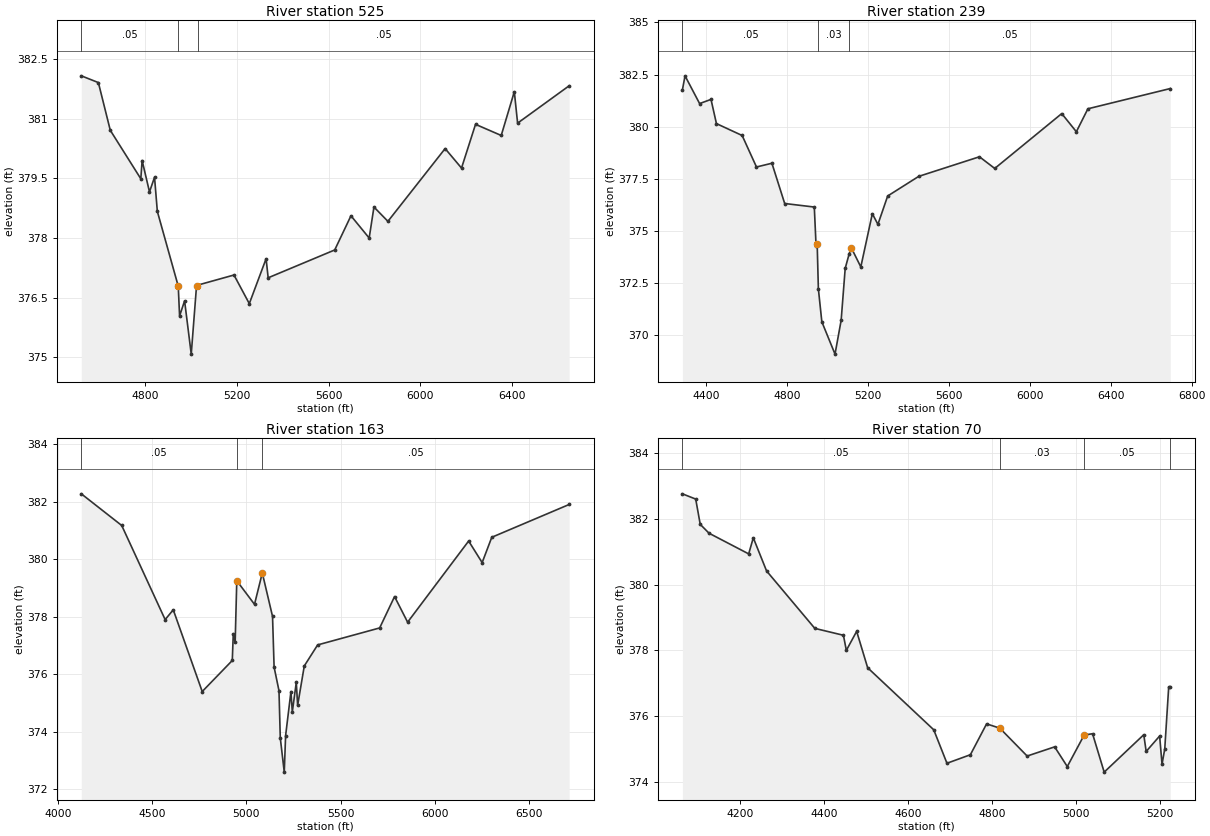
Type RM Length L Ch R = 1 ,525     ,286,286,286
BEGIN DESCRIPTION:
Mapping XS 5fc9c2c
END DESCRIPTION:
XS GIS Cut Line= 6
      2282998.59     13444576.54      2282501.65     13444847.79
      2282481.13     13444942.53      2282700.16     13445453.81
       2282797.6     13445819.37      2282702.07     13446338.41
#Sta/Elev= 30
  4522.3  382.08  4596.7  381.91  4648.6  380.71  4781.7  379.49  4787.4  379.95
  4819.5  379.16  4841.5  379.53  4853.7  378.67  4944.8  376.79  4950.7  376.04
  4972.5  376.42  5001.5  375.08  5024.6   376.8  5032.3  376.82  5187.8  377.07
  5254.6  376.35  5327.8  377.48  5336.8     377  5626.9   377.7  5697.7  378.56
  5777.1     378  5797.9  378.78  5858.8  378.42  6108.2  380.25  6179.6  379.76
  6240.7  380.86  6352.7  380.58  6409.8  381.68  6424.1  380.89  6648.9  381.83
#Mann= 3 ,-1 , 0
  4522.3     .05       0  4944.8    .035       0  5032.3     .05       0
Bank Sta=4944.8,5024.6
XS Rating Curve= 0 ,0
Exp/Cntr=0.3,0.1

Type RM Length L Ch R = 1 ,239     ,76,76,76
BEGIN DESCRIPTION:
Mapping XS aa7a5534
END DESCRIPTION:
XS GIS Cut Line= 6
      2282968.61     13444519.03      2282328.68      13444761.7
      2282325.08     13444905.52      2282686.54     13445440.64
      2282795.16     13445819.57      2282696.41     13446332.23
#Sta/Elev= 30
  4284.7  381.76  4297.7  382.44  4369.7  381.11    4426  381.31  4452.8  380.15
  4579.8  379.58  4650.6  378.07  4726.8  378.25  4789.9  376.32  4936.2  376.15
  4944.9   374.3  4950.4  374.38  4956.3  372.23  4973.4  370.65  5038.5   369.1
  5068.8  370.72  5088.8  373.21  5108.8  373.92  5118.8   374.2  5165.9  373.28
  5222.8  375.83  5250.4  375.32  5298.6  376.68  5451.8  377.62  5751.9  378.56
  5827.4     378  6158.3  380.63  6230.5  379.76  6287.5  380.86  6694.3  381.83
#Mann= 3 ,-1 , 0
  4284.7     .05       0  4956.3     .03       0  5108.8     .05       0
Bank Sta=4950.4,5118.8
XS Rating Curve= 0 ,0
Exp/Cntr=0.3,0.1

Type RM Length L Ch R = 1 ,163     ,93,93,93
BEGIN DESCRIPTION:
Mapping XS 5fc9c2
END DESCRIPTION:
XS GIS Cut Line= 6
      2283021.62     13444462.76      2282249.01     13444714.51
      2282303.51     13444914.51      2282694.92      13445470.1
      2282792.89     13445821.41       2282690.6     13446329.51
#Sta/Elev= 30
  4124.2  382.27  4338.6  381.17    4569   377.9  4612.1  378.24  4765.7   375.4
  4925.3  376.48  4930.5  377.41  4940.5  377.11  4949.1  379.25 5043.12  378.43
  5084.5  379.52  5138.8  378.01  5147.1  376.25    5173  375.43  5179.9  373.79
    5201   372.6  5208.2  373.87  5236.5   375.4  5243.7  374.69  5264.8  375.72
    5272  374.92  5307.3  376.29  5378.1  377.02  5707.2  377.61  5786.2   378.7
  5855.5  377.81  6179.3  380.63    6251  379.88    6302  380.76  6712.7   381.9
#Mann= 3 , 0 , 0
  4124.2     .05       0  4949.1     .03       0  5084.5     .05       0
#XS Ineff= 2 ,-1
 4457.63 4955.93  378.84 5083.05 6191.53  379.07
Permanent Ineff=
       T       T
Bank Sta=4949.1,5084.5
XS Rating Curve= 0 ,0
Exp/Cntr=0.3,0.1

Type RM Length L Ch R = 1 ,70      ,0,0,0
BEGIN DESCRIPTION:
UNT036 IN SUCR 1.0
END DESCRIPTION:
XS GIS Cut Line= 4
      2282947.75     13444399.85      2282168.71     13444662.43
      2282153.52     13444846.89      2282289.17     13444921.72
#Sta/Elev= 30
  4062.8  382.77  4094.5  382.61  4105.3  381.84  4126.2  381.57  4220.7  380.94
  4231.7  381.43  4263.3  380.42  4378.2  378.67  4446.4  378.46  4453.3     378
  4477.9  378.58  4504.1  377.47  4661.5  375.58    4693  374.56  4748.8  374.82
  4787.4  375.76  4818.9  375.63    4884  374.78  4949.5  375.06  4979.6  374.46
  5019.8  375.42  5039.8  375.46  5067.5  374.29  5161.8  375.43  5167.5  374.92
  5199.6  375.39  5205.3  374.53  5211.8     375  5221.2  376.89  5224.9  376.89
#Mann= 4 ,-1 , 0
  4062.8     .05       0  4818.9     .03       0  5019.8     .05       0
  5224.9      .1       0
Bank Sta=4818.9,5019.8
XS Rating Curve= 0 ,0
Exp/Cntr=0.3,0.1

Chan Stop Cuts=-1
Use User Specified Reach Order=0
Composite Channel Slope=5