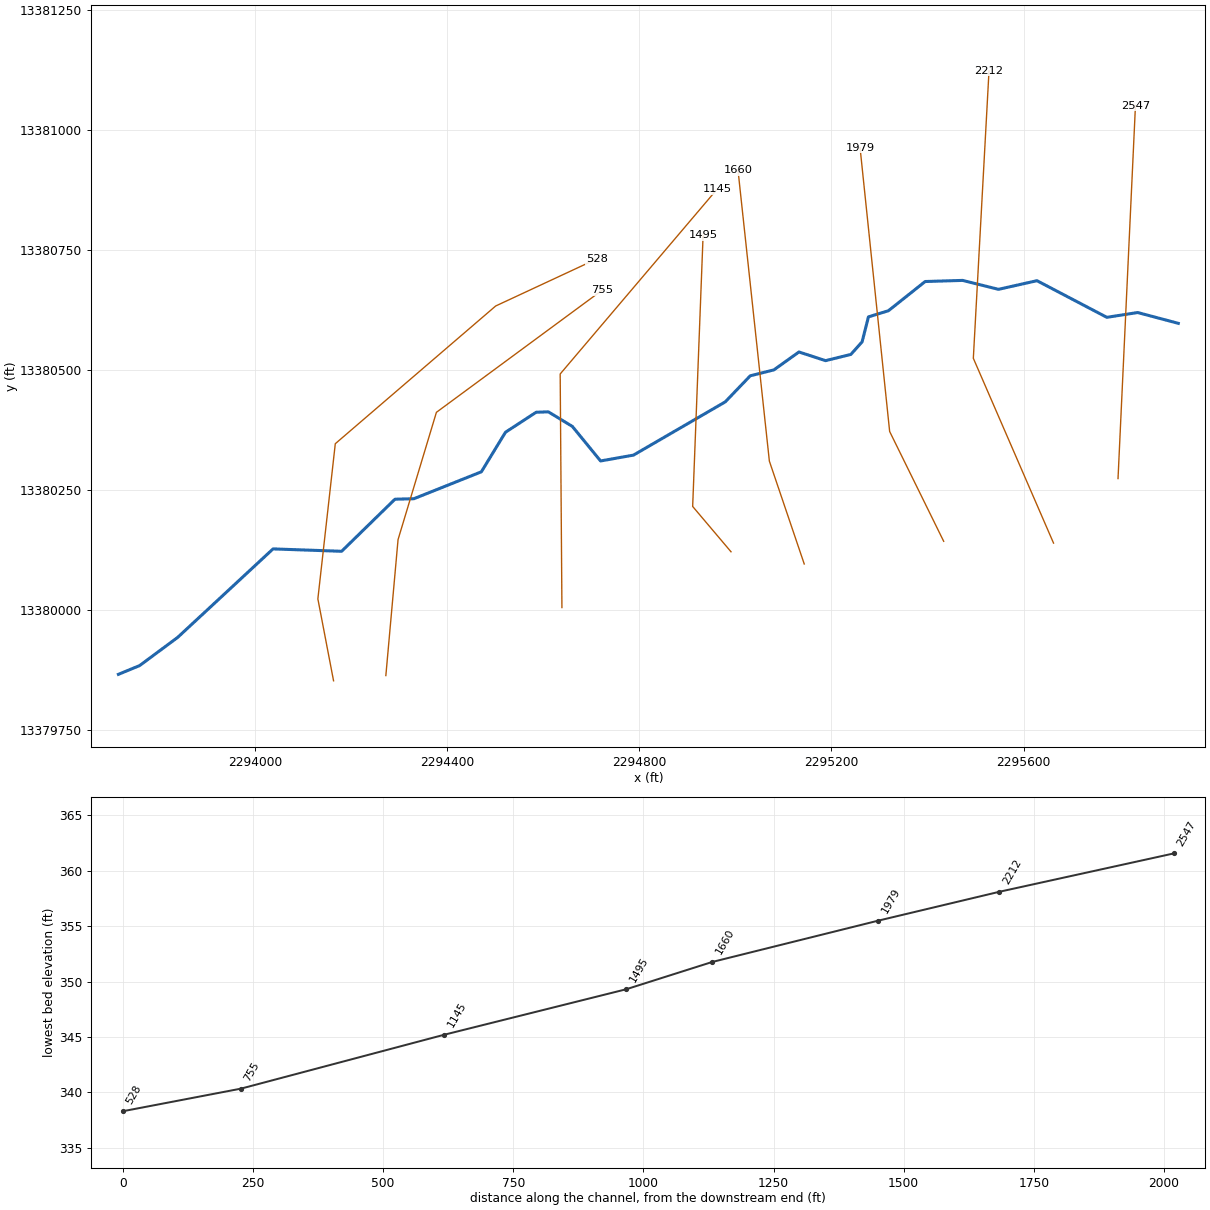
--- UNT0368 IN SUCR.prj (project) ---

Proj Title=UNT0368 IN SUCR Base Level Engineering
Current Plan=p01
Default Exp/Contr=0.3,0.1
English Units
Geom File=g01
Flow File=f01
Plan File=p01
BEGIN DESCRIPTION:
UNT0368 IN SUCR
END DESCRIPTION:

--- UNT0368 IN SUCR.p01 (plan) ---

Plan Title=Multiple Run
Short Identifier=Multiple
Geom File=g01
Flow File=f01
Subcritical Flow
K Sum by GR= 0
Std Step Tol= 0.01
Critical Tol= 0.01
Num of Std Step Trials= 20
Max Error Tol= 0.3
Flow Tol Ratio= 0.001
Split Flow NTrial= 30
Split Flow Tol= 0.02
Split Flow Ratio= 0.02
Log Output Level= 0
Friction Slope Method= 1
Unsteady Friction Slope Method= 2
Unsteady Bridges Friction Slope Method= 1
Parabolic Critical Depth
Global Vel Dist=  1 , 1 , 1
Global Log Level= 0
CheckData=True
Encroach Param= -1, 0, 0, 0
BEGIN DESCRIPTION:
Multiple Run
END DESCRIPTION:

--- UNT0368 IN SUCR.f01 (steady flow) ---

Flow Title=Multiple
Number of Profiles=7
Profile Names=10-year,25-year,50-year,1pct_min,100-year,1pct_plu,500-year
River Rch & RM= UNT0368 IN SUCR,Reach-1,2547
     238     320     386     342     462     625     662
Boundary for River Rch & Prof#=UNT0368 IN SUCR,Reach-1,1
Up Type=0
Dn Type=3
Dn Slope=0.005
Boundary for River Rch & Prof#=UNT0368 IN SUCR,Reach-1,2
Up Type=0
Dn Type=3
Dn Slope=0.005
Boundary for River Rch & Prof#=UNT0368 IN SUCR,Reach-1,3
Up Type=0
Dn Type=3
Dn Slope=0.005
Boundary for River Rch & Prof#=UNT0368 IN SUCR,Reach-1,4
Up Type=0
Dn Type=3
Dn Slope=0.005
Boundary for River Rch & Prof#=UNT0368 IN SUCR,Reach-1,5
Up Type=0
Dn Type=3
Dn Slope=0.005
Boundary for River Rch & Prof#=UNT0368 IN SUCR,Reach-1,6
Up Type=0
Dn Type=3
Dn Slope=0.005
Boundary for River Rch & Prof#=UNT0368 IN SUCR,Reach-1,7
Up Type=0
Dn Type=3
Dn Slope=0.005

--- UNT0368 IN SUCR.g01 (geometry) ---

Geom Title=Existing Conditions

River Reach=UNT0368 IN SUCR,Reach-1
Reach XY= 30
      2295922.09     13380596.85      2295837.47     13380619.35
      2295773.36     13380609.35      2295627.92     13380685.61
      2295547.71     13380667.65      2295473.05     13380686.23
      2295395.12     13380683.92      2295318.67     13380623.10
      2295277.03     13380610.31      2295263.80     13380558.31
      2295240.41     13380532.11      2295187.73     13380519.15
      2295132.37     13380537.21      2295080.14     13380499.92
      2295030.98     13380487.62      2294978.86     13380433.30
      2294787.84     13380322.49      2294719.34     13380310.32
      2294660.55     13380382.24      2294610.58     13380412.59
      2294585.24     13380411.74      2294521.33     13380370.08
      2294471.13     13380287.71      2294330.61     13380231.70
      2294291.26     13380230.70      2294180.23     13380122.25
      2294037.49     13380127.24      2293838.89     13379943.01
      2293759.81     13379884.38      2293715.53     13379866.08

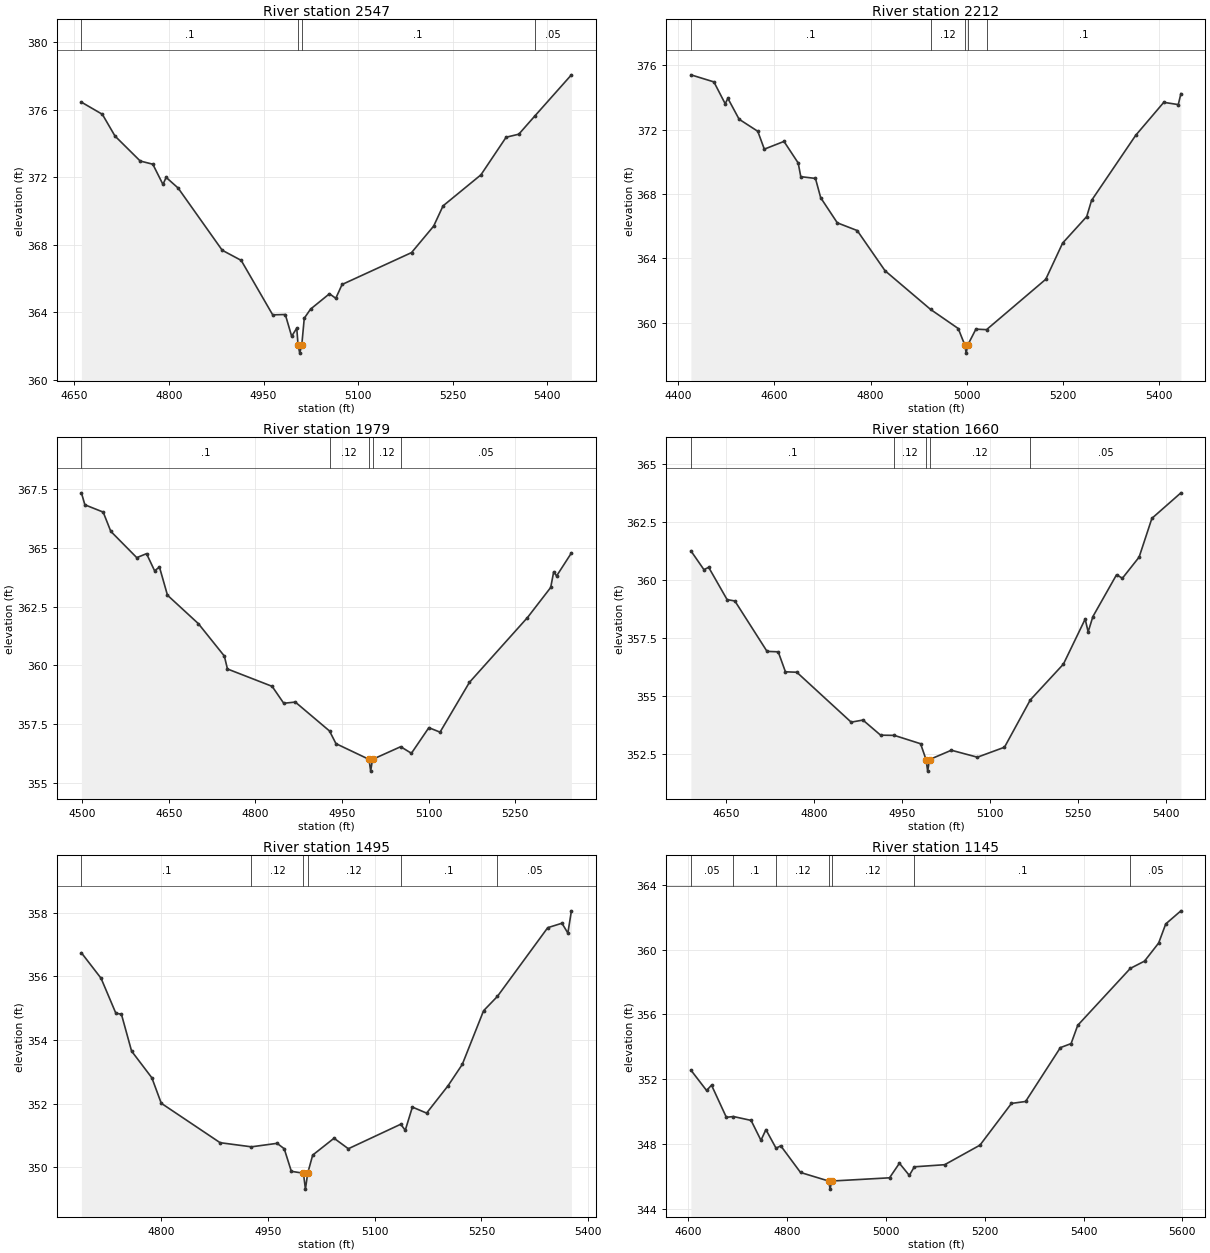
Type RM Length L Ch R = 1,2547,335,335,335
BEGIN DESCRIPTION:
UNT0368 IN SUCR 4.0
END DESCRIPTION:
XS GIS Cut Line= 2
      2295796.63     13380273.66      2295832.92     13381050.31
#Sta/Elev= 30
  4661.0  376.45  4694.2  375.73  4714.3  374.44  4754.3  372.96  4774.3  372.77
  4790.4  371.57  4795.4  371.99  4814.4  371.36  4884.4  367.67  4914.5  367.07
  4964.5  363.84  4984.5  363.86  4994.6  362.57  5002.7  363.05  5004.7  362.07
  5007.4  361.57  5010.7  362.07  5014.6  363.64  5024.6  364.18  5054.6  365.09
  5064.6  364.82  5074.6  365.64  5184.8  367.53  5219.9  369.10  5234.8  370.30
  5294.9  372.14  5334.9  374.37  5355.0  374.55  5380.2  375.62  5438.5  378.07
#Mann=4,-1,0
  4661.0     0.1       0  5004.7    0.07       0  5010.7     0.1       0
  5380.2    0.05       0
Bank Sta=5004.7,5010.7
Exp/Cntr=0.3,0.1

Type RM Length L Ch R = 1,2212,233,233,233
BEGIN DESCRIPTION:
Mapping XS a498293c
END DESCRIPTION:
XS GIS Cut Line= 3
      2295662.36     13380139.33      2295495.39     13380524.08
      2295528.03     13381122.37
#Sta/Elev= 30
  4426.6  375.41  4474.4  374.97  4497.9  373.61  4503.4  373.95  4526.8  372.65
  4565.6  371.90  4579.2  370.79  4620.1  371.27  4649.6  369.93  4655.0  369.08
  4685.5  368.97  4696.4  367.77  4730.9  366.21  4772.3  365.73  4830.2  363.23
  4924.7  360.83  4982.3  359.64  4996.0  358.61  4998.8  358.11  5002.0  358.61
  5019.0  359.60  5041.2  359.57  5164.2  362.70  5199.3  364.95  5249.4  366.60
  5259.4  367.60  5351.2  371.65  5409.6  373.70  5439.7  373.56  5445.2  374.24
#Mann=5,-1,0
  4426.6     0.1       0  4924.7    0.12       0  4996.0    0.07       0
  5002.0    0.12       0  5041.2     0.1       0
Bank Sta=4996,5002
Exp/Cntr=0.3,0.1

Type RM Length L Ch R = 1,1979,319,319,319
BEGIN DESCRIPTION:
UNT0368 IN SUCR 2.0
END DESCRIPTION:
XS GIS Cut Line= 3
      2295433.67     13380143.04      2295321.18     13380371.65
      2295259.56     13380962.56
#Sta/Elev= 30
  4498.7  367.35  4504.7  366.84  4536.4  366.53  4549.6  365.71  4594.6  364.59
  4611.5  364.76  4625.5  364.03  4633.9  364.19  4647.8  362.99  4701.3  361.78
  4746.3  360.40  4751.7  359.85  4829.1  359.11  4849.2  358.39  4869.3  358.44
  4928.5  357.21  4939.7  356.67  4997.0  356.00  4999.8  355.50  5003.0  356.00
  5051.8  356.54  5070.4  356.26  5100.6  357.35  5120.0  357.16  5170.9  359.28
  5271.5  362.04  5311.7  363.32  5316.9  363.99  5321.9  363.81  5347.6  364.79
#Mann=5,-1,0
  4498.7     0.1       0  4928.5    0.12       0  4997.0    0.07       0
  5003.0    0.12       0  5051.8    0.05       0
Bank Sta=4997,5003
Exp/Cntr=0.3,0.1

Type RM Length L Ch R = 1,1660,165,165,165
BEGIN DESCRIPTION:
Mapping XS 34ee0711
END DESCRIPTION:
XS GIS Cut Line= 3
      2295143.34     13380095.84      2295070.76     13380309.95
      2295005.43     13380916.06
#Sta/Elev= 30
  4590.1  361.26  4612.3  360.45  4620.4  360.55  4651.8  359.16  4665.1  359.10
  4719.9  356.93  4739.0  356.91  4751.3  356.05  4770.7  356.03  4863.4  353.88
  4883.5  353.97  4913.6  353.32  4937.0  353.31  4981.8  352.95  4991.1  352.27
  4993.9  351.77  4997.1  352.27  5034.3  352.67  5078.7  352.37  5124.9  352.80
  5169.0  354.84  5225.4  356.38  5262.5  358.32  5267.6  357.77  5275.7  358.43
  5316.0  360.23  5326.0  360.08  5354.5  360.99  5376.3  362.66  5425.8  363.76
#Mann=5,-1,0
  4590.1     0.1       0  4937.0    0.12       0  4991.1    0.07       0
  4997.1    0.12       0  5169.0    0.05       0
Bank Sta=4991.1,4997.1
Exp/Cntr=0.3,0.1

Type RM Length L Ch R = 1,1495,350,350,350
BEGIN DESCRIPTION:
UNT0368 IN SUCR 3.0
END DESCRIPTION:
XS GIS Cut Line= 3
      2294990.91     13380121.23      2294911.07     13380215.59
      2294932.78     13380780.17
#Sta/Elev= 30
  4687.8  356.74  4715.4  355.94  4736.2  354.84  4744.0  354.81  4758.3  353.65
  4786.8  352.81  4800.0  352.01  4882.7  350.77  4926.7  350.64  4962.8  350.75
  4972.8  350.58  4982.8  349.87  4999.8  349.81  5002.6  349.31  5005.8  349.81
  5012.8  350.38  5042.8  350.91  5062.9  350.58  5136.5  351.35  5142.9  351.16
  5152.9  351.89  5172.9  351.70  5203.0  352.56  5223.0  353.23  5253.0  354.92
  5272.4  355.37  5343.1  357.53  5363.1  357.67  5371.4  357.36  5376.4  358.06
#Mann=6,-1,0
  4687.8     0.1       0  4926.7    0.12       0  4999.8    0.07       0
  5005.8    0.12       0  5136.5     0.1       0  5272.4    0.05       0
Bank Sta=4999.8,5005.8
Exp/Cntr=0.3,0.1

Type RM Length L Ch R = 1,1145,390,390,390
BEGIN DESCRIPTION:
Mapping XS 4ecebc3c
END DESCRIPTION:
XS GIS Cut Line= 3
      2294638.87     13380005.12      2294635.24     13380491.42
      2294961.89     13380876.14
#Sta/Elev= 30
  4606.0  352.56  4637.7  351.30  4647.7  351.63  4677.7  349.64  4691.9  349.69
  4727.7  349.45  4747.7  348.22  4757.7  348.88  4778.2  347.73  4787.7  347.88
  4827.7  346.23  4884.7  345.70  4887.5  345.20  4890.7  345.70  5007.7  345.90
  5027.7  346.80  5047.7  346.05  5057.9  346.58  5119.2  346.71  5190.6  347.92
  5254.3  350.50  5282.9  350.62  5353.2  353.95  5374.9  354.20  5388.3  355.33
  5494.7  358.85  5523.4  359.30  5552.0  360.42  5566.3  361.60  5597.0  362.41
#Mann=7,-1,0
  4606.0    0.05       0  4691.9     0.1       0  4778.2    0.12       0
  4884.7    0.07       0  4890.7    0.12       0  5057.9     0.1       0
  5494.7    0.05       0
Bank Sta=4884.7,4890.7
Exp/Cntr=0.3,0.1

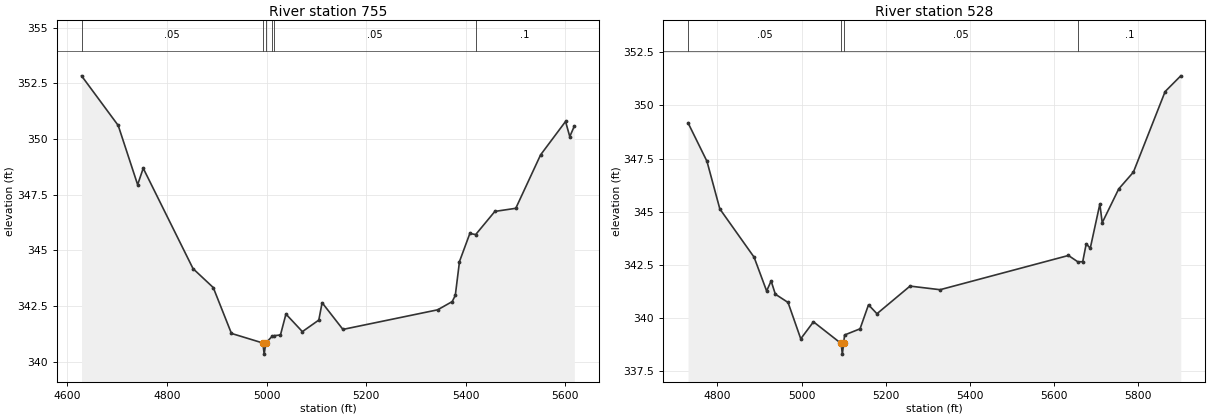
Type RM Length L Ch R = 1,755,227,227,227
BEGIN DESCRIPTION:
Mapping XS b15a4cf0
END DESCRIPTION:
XS GIS Cut Line= 4
      2294272.30     13379863.54      2294297.71     13380146.63
      2294377.55     13380411.57      2294722.33     13380665.62
#Sta/Elev= 30
  4628.7  352.84  4702.3  350.61  4741.3  347.95  4752.5  348.69  4852.5  344.18
  4893.1  343.33  4929.6  341.27  4992.6  340.84  4995.3  340.34  4998.6  340.84
  5011.3  341.14  5015.8  341.17  5028.0  341.20  5039.0  342.14  5072.0  341.35
  5105.0  341.87  5111.6  342.65  5153.4  341.45  5343.5  342.33  5372.8  342.70
  5379.0  342.98  5387.4  344.50  5408.2  345.76  5419.9  345.71  5458.4  346.75
  5500.4  346.89  5550.2  349.29  5600.3  350.79  5608.8  350.11  5617.9  350.58
#Mann=6,-1,0
  4628.7    0.05       0  4992.6    0.03       0  4998.6    0.05       0
  5011.3    0.12       0  5015.8    0.05       0  5419.9     0.1       0
Bank Sta=4992.6,4998.6
Exp/Cntr=0.3,0.1

Type RM Length L Ch R = 1,528,0,0,0
BEGIN DESCRIPTION:
UNT0368 IN SUCR 1.0
END DESCRIPTION:
XS GIS Cut Line= 5
      2294163.43     13379852.64      2294130.76     13380023.24
      2294167.05     13380346.25      2294500.95     13380632.96
      2294711.42     13380730.94
#Sta/Elev= 30
  4730.1  349.18  4775.1  347.37  4805.7  345.13  4887.1  342.86  4916.9  341.27
  4927.6  341.74  4937.6  341.12  4967.8  340.73  4998.0  339.02  5028.2  339.82
  5094.0  338.80  5096.8  338.30  5100.0  338.80  5102.1  339.20  5138.9  339.49
  5159.0  340.62  5179.1  340.20  5257.7  341.50  5329.1  341.33  5634.1  342.94
  5656.6  342.64  5668.1  342.65  5676.4  343.49  5686.0  343.28  5708.8  345.36
  5714.4  344.48  5753.6  346.07  5788.5  346.86  5863.9  350.65  5901.1  351.39
#Mann=4,-1,0
  4730.1    0.05       0  5094.0    0.03       0  5100.0    0.05       0
  5656.6     0.1       0
Bank Sta=5094,5100
Exp/Cntr=0.3,0.1

Chan Stop Cuts=-1