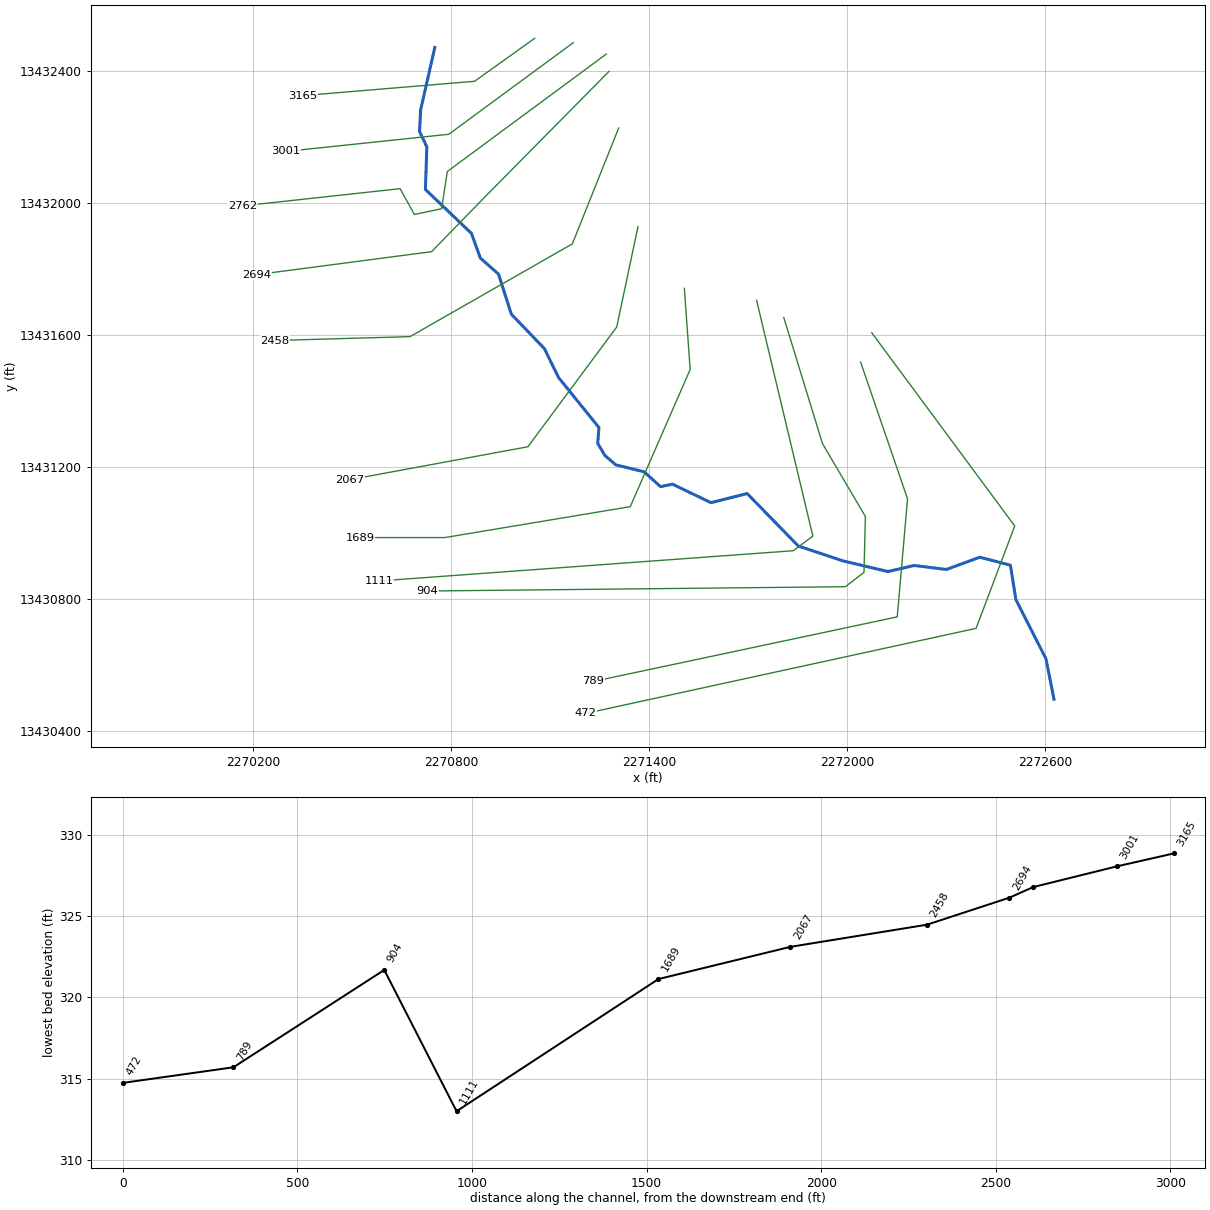
--- UNT037 IN SUCR.prj (project) ---

Proj Title=UNT037 IN SUCR Base Level Engineering
Current Plan=p01
Default Exp/Contr=0.3,0.1
English Units
Geom File=g01
Flow File=f01
Plan File=p01
Y Axis Title=Elevation
X Axis Title(PF)=Main Channel Distance
X Axis Title(XS)=Station
BEGIN DESCRIPTION:
UNT037 IN SUCR
END DESCRIPTION:
DSS Export Rating Curves= 0
DSS Export Rating Curve Sorted= 0
DSS Export Volume Flow Curves= 0
DXF OffsetX= 0
DXF OffsetY= 0
DXF ScaleX= 1
DXF ScaleY= 10

--- UNT037 IN SUCR.p01 (plan) ---

Plan Title=Multiple Run
Short Identifier=Multiple
Geom File=g01
Flow File=f01
Subcritical Flow
K Sum by GR= 0
Std Step Tol= 0.01
Critical Tol= 0.01
Num of Std Step Trials= 20
Max Error Tol= 0.3
Flow Tol Ratio= 0.001
Split Flow NTrial= 30
Split Flow Tol= 0.02
Split Flow Ratio= 0.02
Log Output Level= 0
Friction Slope Method= 1
Unsteady Friction Slope Method= 2
Unsteady Bridges Friction Slope Method= 1
Parabolic Critical Depth
Global Vel Dist=  1 , 1 , 1
Global Log Level= 0
CheckData=True
Encroach Param= -1, 0, 0, 0
BEGIN DESCRIPTION:
Multiple Run
END DESCRIPTION:

--- UNT037 IN SUCR.f01 (steady flow) ---

Flow Title=Multiple
Number of Profiles=7
Profile Names=10-year,25-year,50-year,1pct_min,100-year,1pct_plu,500-year
River Rch & RM= UNT037 IN SUCR,Reach-1,3165
     162     216     258     227     307     416     442
Boundary for River Rch & Prof#=UNT037 IN SUCR,Reach-1,1
Up Type=0
Dn Type=3
Dn Slope=0.005
Boundary for River Rch & Prof#=UNT037 IN SUCR,Reach-1,2
Up Type=0
Dn Type=3
Dn Slope=0.005
Boundary for River Rch & Prof#=UNT037 IN SUCR,Reach-1,3
Up Type=0
Dn Type=3
Dn Slope=0.005
Boundary for River Rch & Prof#=UNT037 IN SUCR,Reach-1,4
Up Type=0
Dn Type=3
Dn Slope=0.005
Boundary for River Rch & Prof#=UNT037 IN SUCR,Reach-1,5
Up Type=0
Dn Type=3
Dn Slope=0.005
Boundary for River Rch & Prof#=UNT037 IN SUCR,Reach-1,6
Up Type=0
Dn Type=3
Dn Slope=0.005
Boundary for River Rch & Prof#=UNT037 IN SUCR,Reach-1,7
Up Type=0
Dn Type=3
Dn Slope=0.005

--- UNT037 IN SUCR.g01 (geometry) ---

Geom Title=Existing Conditions
Program Version=4.10

River Reach=UNT037 IN SUCR  ,Reach-1
Reach XY= 30
      2270750.82     13432472.54      2270707.77     13432283.09
      2270704.49     13432217.68      2270726.59     13432171.09
      2270722.25     13432041.96      2270861.73     13431908.92
       2270888.9     13431833.82      2270943.83     13431785.37
      2270982.75     13431663.97      2271082.88     13431559.59
       2271126.2     13431471.31      2271248.35     13431320.14
       2271244.6     13431272.32      2271266.14      13431235.7
      2271299.74     13431206.95      2271385.16     13431186.12
      2271435.16     13431140.98      2271471.27     13431148.62
      2271587.93     13431092.37      2271697.66     13431120.14
      2271852.52     13430961.12      2271987.93     13430915.98
      2272124.32     13430883.71      2272203.91     13430902.09
      2272301.61     13430889.98      2272402.77     13430927.09
      2272495.63     13430902.97       2272512.3      13430798.4
      2272603.21     13430619.71      2272627.72     13430496.86

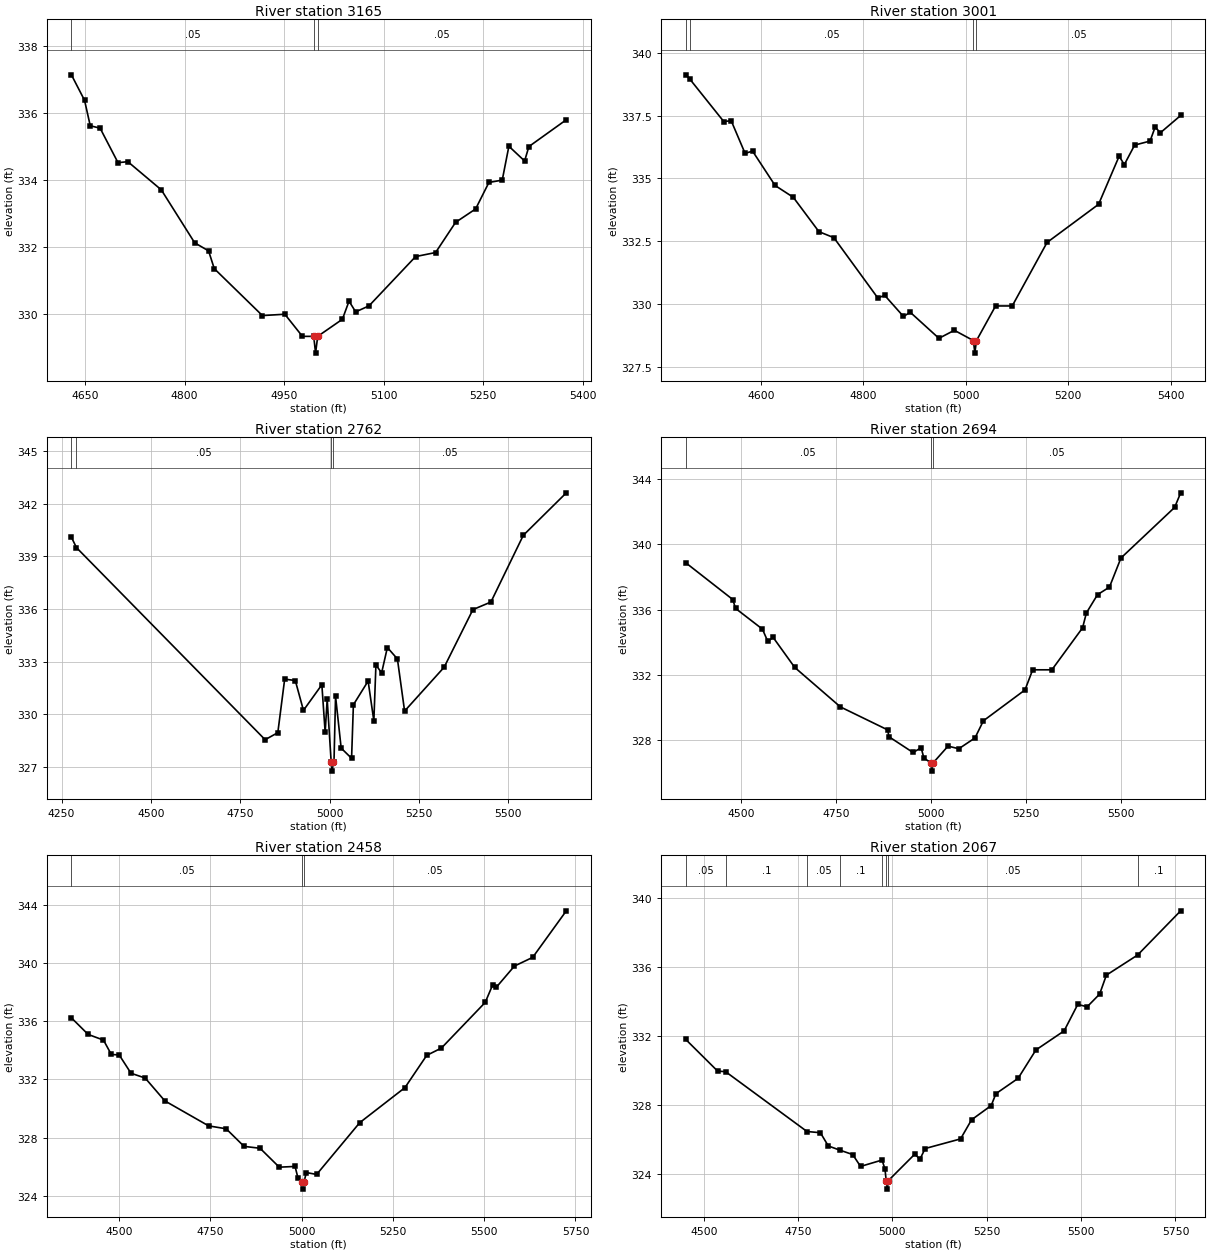
Type RM Length L Ch R = 1 ,3165    ,164,164,164
BEGIN DESCRIPTION:
UNT037 IN SUCR 5.0
END DESCRIPTION:
XS GIS Cut Line= 3
      2271053.51     13432500.06      2270871.18     13432369.83
      2270351.55     13432326.52
#Sta/Elev= 30
  4629.6  337.14  4649.4  336.38    4658  335.62  4672.8  335.55  4699.8  334.52
  4714.6  334.55    4765  333.71  4815.3  332.13  4836.2  331.89  4844.8  331.36
  4917.3  329.96  4951.1     330  4977.6  329.34  4994.6  329.34  4997.4  328.84
  5000.6  329.34  5037.8  329.85  5047.8  330.39  5057.8  330.07  5077.9  330.25
  5148.1  331.72  5178.2  331.84  5208.3  332.74  5238.5  333.14  5258.5  333.93
  5278.6     334  5288.6  335.01  5312.3  334.57  5318.7     335  5375.1   335.8
#Mann= 3 ,-1 , 0
  4629.6     .05       0  4994.6     .03       0  5000.6     .05       0
Bank Sta=4994.6,5000.6
XS Rating Curve= 0 ,0
Exp/Cntr=0.3,0.1

Type RM Length L Ch R = 1 ,3001    ,239,239,239
BEGIN DESCRIPTION:
Mapping XS 573948e0
END DESCRIPTION:
XS GIS Cut Line= 3
      2271170.66     13432487.02      2270793.05     13432209.24
      2270298.27     13432157.15
#Sta/Elev= 30
    4453  339.13  4460.5  338.97  4527.1  337.27  4541.7   337.3  4568.8     336
  4583.4  336.09  4627.4  334.72  4662.9  334.25    4713  332.88  4742.2  332.64
  4827.9  330.24  4841.5  330.34  4878.1   329.5  4891.2  329.67  4947.3  328.63
  4977.4  328.95  5014.6  328.54  5017.4  328.04  5020.6  328.54  5057.9  329.92
  5090.4  329.92  5158.4  332.45    5259  333.97  5299.2  335.89  5309.2  335.55
  5329.4  336.33  5359.5  336.49  5369.5  337.05  5379.6  336.82  5419.3  337.51
#Mann= 4 ,-1 , 0
    4453      .1       0  4460.5     .05       0  5014.6     .03       0
  5020.6     .05       0
Bank Sta=5014.6,5020.6
XS Rating Curve= 0 ,0
Exp/Cntr=0.3,0.1

Type RM Length L Ch R = 1 ,2762    ,68,68,68
BEGIN DESCRIPTION:
Mapping XS 12284b73
END DESCRIPTION:
XS GIS Cut Line= 6
      2271270.48     13432452.29      2270788.71     13432096.39
      2270771.35     13431983.54      2270688.88     13431966.18
      2270645.48     13432044.31       2270168.1     13431992.23
#Sta/Elev= 30
  4277.7  340.09  4291.8   339.5  4819.5  328.56    4855  328.96  4874.2  332.01
  4903.9  331.93  4926.7  330.23  4978.2  331.69  4987.4  328.98  4993.1  330.86
  5004.3  327.27    5007  326.77  5010.3  327.27  5012.1  327.27  5016.5  331.03
  5032.2  328.08  5061.3   327.5  5066.4  330.55  5107.6   331.9  5123.6  329.63
  5129.4  332.81  5145.4  332.37  5161.4  333.81  5189.5  333.16  5209.6  330.19
  5320.3  332.69  5400.7  335.97    5451   336.4  5541.6   340.2  5661.9  342.62
#Mann= 4 ,-1 , 0
  4277.7      .1       0  4291.8     .05       0  5004.3     .03       0
  5010.3     .05       0
Bank Sta=5004.3,5010.3
XS Rating Curve= 0 ,0
Exp/Cntr=0.3,0.1

Type RM Length L Ch R = 1 ,2694    ,236,236,236
BEGIN DESCRIPTION:
Mapping XS 3ae71b7b
END DESCRIPTION:
XS GIS Cut Line= 4
      2271279.15     13432400.19       2270905.9      13432022.6
      2270740.97     13431853.33      2270212.07     13431783.97
#Sta/Elev= 30
  4355.2  338.87  4478.8  336.62  4485.9  336.08  4556.6  334.81  4570.7  334.06
  4584.9   334.3  4641.4  332.47  4761.6  330.05  4886.1  328.64  4888.9  328.23
  4952.5  327.26  4973.8  327.55  4980.8  326.94  4999.1  326.62  5001.8  326.12
  5005.1  326.62  5044.5  327.65  5072.8  327.49  5115.3  328.15  5137.4   329.2
  5246.8  331.09  5266.9  332.32  5317.4  332.32  5398.1  334.89  5408.1   335.8
  5437.4  336.92  5468.7  337.38  5498.9  339.16  5640.1  342.26  5655.9  343.15
#Mann= 3 ,-1 , 0
  4355.2     .05       0  4999.1     .03       0  5005.1     .05       0
Bank Sta=4999.1,5005.1
XS Rating Curve= 0 ,0
Exp/Cntr=0.3,0.1

Type RM Length L Ch R = 1 ,2458    ,391,391,391
BEGIN DESCRIPTION:
UNT037 IN SUCR 4.0
END DESCRIPTION:
XS GIS Cut Line= 4
      2271308.16     13432228.34      2271167.58      13431876.9
      2270675.63     13431595.79      2270265.72     13431584.07
#Sta/Elev= 30
  4369.7  336.24  4415.5   335.1  4457.5  334.71    4479  333.72  4500.5  333.69
  4532.9  332.43  4571.7   332.1  4625.5  330.53  4745.5  328.81  4793.5  328.61
  4842.5   327.4  4886.3  327.27  4938.9  325.97  4982.1  326.02  4989.9  325.25
  5000.7  324.96  5003.5  324.46  5006.7  324.96    5013   325.6  5041.2  325.47
  5159.2  329.03    5283  331.44  5342.7  333.66  5382.8  334.16  5502.8   337.3
  5522.8  338.48  5532.8  338.33  5582.8   339.8  5632.9   340.4  5724.9   343.6
#Mann= 3 ,-1 , 0
  4369.7     .05       0  5000.7     .03       0  5006.7     .05       0
Bank Sta=5000.7,5006.7
XS Rating Curve= 0 ,0
Exp/Cntr=0.3,0.1

Type RM Length L Ch R = 1 ,2067    ,378,378,378
BEGIN DESCRIPTION:
UNT037 IN SUCR 3.0
END DESCRIPTION:
XS GIS Cut Line= 4
       2271366.7     13431929.57      2271302.28     13431625.07
      2271032.88     13431261.96      2270494.07      13431162.4
#Sta/Elev= 30
  4452.5   331.8    4537  329.96  4557.9  329.93  4773.7  326.45  4809.2  326.38
  4830.1  325.61  4860.3  325.37  4894.8  325.11  4915.6  324.42  4972.5  324.79
  4980.3  324.27  4983.5   323.6  4986.3   323.1  4989.5   323.6  5059.6  325.14
  5072.8  324.83  5086.7  325.46  5180.6  326.02  5209.7  327.13  5261.8  327.96
  5274.3  328.65    5333  329.54  5380.2  331.19    5455   332.3  5491.1  333.84
    5516   333.7  5549.1  334.44  5566.9  335.54  5649.7  336.71  5763.8  339.28
#Mann= 8 ,-1 , 0
  4452.5     .05       0  4557.9      .1       0  4773.7     .05       0
  4860.3      .1       0  4972.5     .05       0  4983.5     .03       0
  4989.5     .05       0  5649.7      .1       0
Bank Sta=4983.5,4989.5
XS Rating Curve= 0 ,0
Exp/Cntr=0.3,0.1

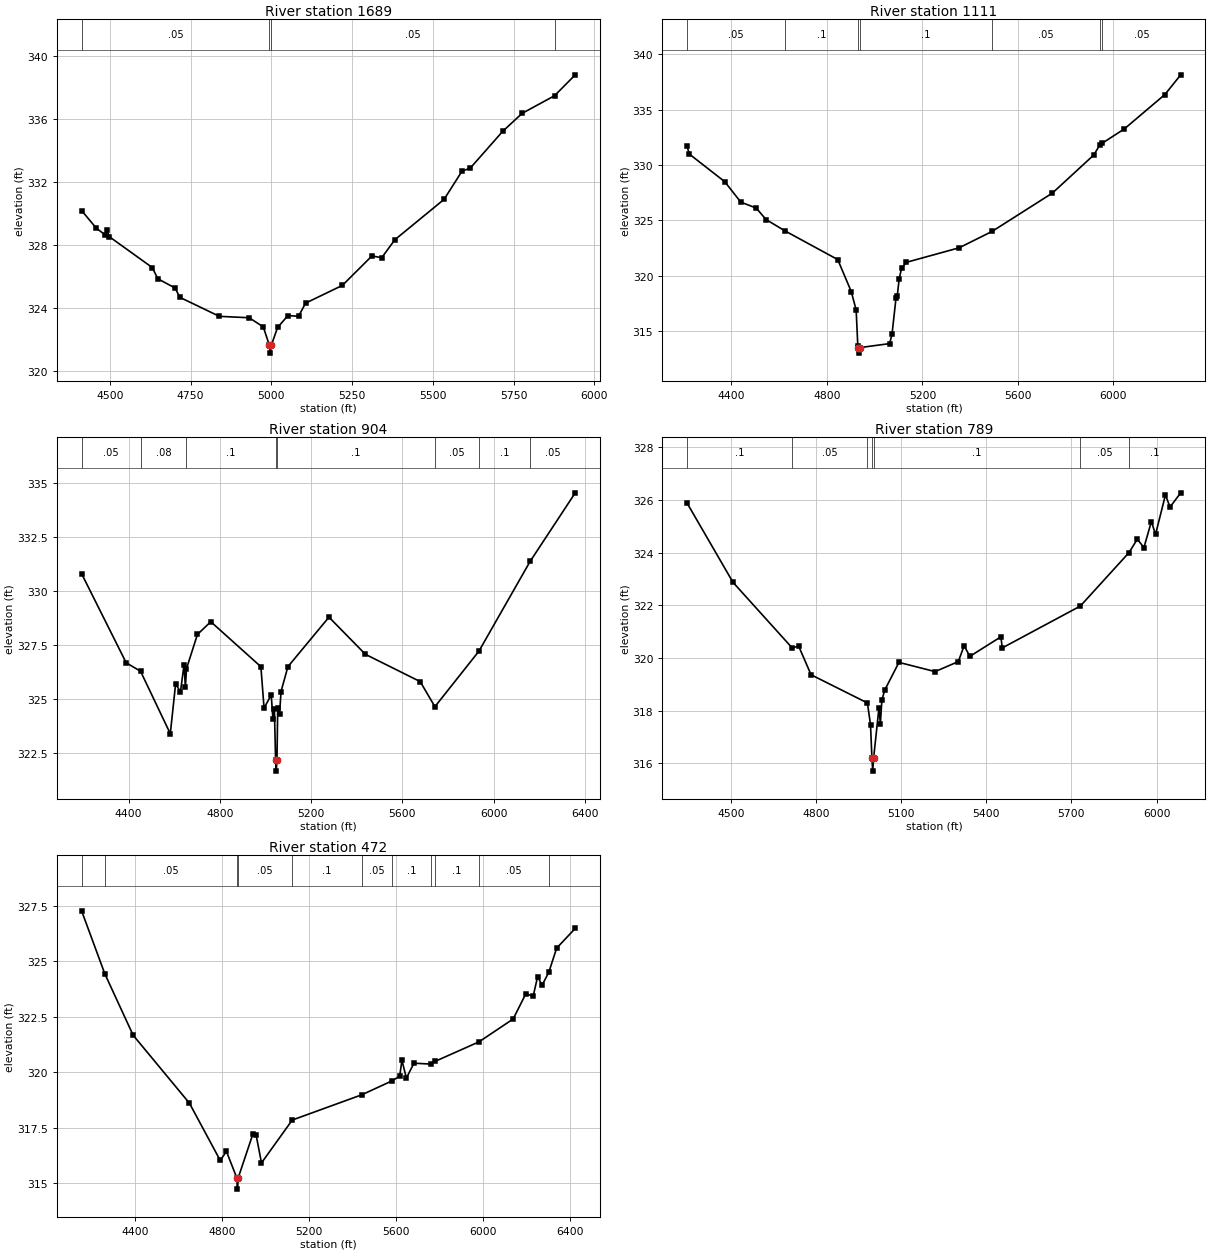
Type RM Length L Ch R = 1 ,1689    ,578,578,578
BEGIN DESCRIPTION:
UNT037 IN SUCR 2.0
END DESCRIPTION:
XS GIS Cut Line= 5
      2271507.26     13431742.18      2271524.83     13431496.22
      2271343.28     13431080.41      2270781.05      13430986.7
      2270523.35      13430986.7
#Sta/Elev= 30
  4412.6  330.19    4458  329.07  4486.1  328.63  4491.2  328.96  4498.1  328.53
  4631.5  326.56  4648.5  325.85  4702.1  325.26  4716.5  324.67    4839  323.46
  4931.3  323.37  4974.9  322.79  4993.8  321.62  4996.5  321.12  4999.8  321.62
  5019.2  322.75  5051.3  323.51    5084  323.46  5105.9   324.3  5219.9  325.43
  5311.2   327.3  5341.6  327.19  5382.1  328.33  5534.6   330.9  5590.3   332.7
  5615.3  332.88  5716.2  335.23  5776.2  336.37  5876.4  337.49  5940.6  338.82
#Mann= 4 ,-1 , 0
  4412.6     .05       0  4993.8     .03       0  4999.8     .05       0
  5876.4      .1       0
Bank Sta=4993.8,4999.8
XS Rating Curve= 0 ,0
Exp/Cntr=0.3,0.1

Type RM Length L Ch R = 1 ,1111    ,207,207,207
BEGIN DESCRIPTION:
Mapping XS 0cbc1966
END DESCRIPTION:
XS GIS Cut Line= 4
      2271726.21     13431705.78      2271896.77     13430991.16
      2271837.72     13430946.85      2270581.57     13430855.16
#Sta/Elev= 30
  4213.9  331.71  4223.1     331  4371.7   328.5    4439  326.65  4503.1  326.12
  4545.2  325.07  4625.8  324.03    4845  321.46  4901.6  318.57  4922.2   316.9
  4929.2  313.62  4931.4   313.5  4934.1     313  4937.4   313.5  5062.5  313.86
  5072.5  314.73  5089.3  318.01  5094.3  318.16  5102.6  319.74  5112.6  320.68
  5132.7  321.21  5353.3  322.52  5491.3     324  5744.3  327.47  5917.5  330.91
  5942.2  331.79  5951.7  331.96  6045.1  333.26  6215.6  336.38  6281.9  338.16
#Mann= 7 ,-1 , 0
  4213.9     .05       0  4625.8      .1       0  4931.4     .07       0
  4937.4      .1       0  5491.3     .05       0  5942.2      .1       0
  5951.7     .05       0
Bank Sta=4931.4,4937.4
XS Rating Curve= 0 ,0
Exp/Cntr=0.3,0.1

Type RM Length L Ch R = 1 ,904     ,432,432,432
BEGIN DESCRIPTION:
Mapping XS 1ffba313
END DESCRIPTION:
XS GIS Cut Line= 6
      2271808.66     13431653.72      2271925.86     13431271.74
      2272056.07     13431050.38      2272051.73     13430881.11
      2271995.31     13430837.71      2270727.96     13430824.69
#Sta/Elev= 30
  4193.8  330.81  4389.3  326.69  4452.2   326.3  4582.7  323.41  4605.9  325.71
  4627.3  325.35    4643  326.61  4648.8  325.55  4653.7  326.42  4701.6     328
  4760.2  328.59  4979.8  326.51  4993.7   324.6  5025.2   325.2  5032.8  324.07
  5039.1  324.53  5044.3  322.18    5047  321.68  5050.3  322.18  5053.6  324.61
  5061.8  324.33  5068.1  325.36  5098.3  326.51  5278.3   328.8  5438.3  327.08
  5678.3  325.82  5742.8  324.66  5935.9  327.23  6160.3  331.38  6358.1  334.55
#Mann= 8 ,-1 , 0
  4193.8     .05       0  4452.2     .08       0  4653.7      .1       0
  5044.3     .07       0  5050.3      .1       0  5742.8     .05       0
  5935.9      .1       0  6160.3     .05       0
Bank Sta=5044.3,5050.3
XS Rating Curve= 0 ,0
Exp/Cntr=0.3,0.1

Type RM Length L Ch R = 1 ,789     ,317,317,317
BEGIN DESCRIPTION:
UNT037 IN SUCR 1.1
END DESCRIPTION:
XS GIS Cut Line= 4
      2272041.46     13431518.79      2272183.82     13431103.89
      2272152.57     13430746.25      2271230.87     13430550.47
#Sta/Elev= 30
  4345.5  325.88  4507.4  322.87  4715.9  320.38  4738.7  320.45  4782.5  319.36
    4981  318.29    4992  317.47    4997   316.2  4999.8   315.7    5003   316.2
  5021.8   318.1  5026.8   317.5  5032.1   318.4  5042.2  318.78  5092.3  319.83
  5219.7  319.48  5301.4  319.86  5321.9  320.46  5342.3  320.06  5451.4   320.8
  5456.5  320.38  5731.6  321.97  5903.1     324  5932.3  324.51  5955.7  324.19
  5981.9  325.18  5996.6  324.69  6031.5  326.19  6047.7  325.73  6085.4  326.27
#Mann= 7 ,-1 , 0
  4345.5      .1       0  4715.9     .05       0    4981      .1       0
    4997     .07       0    5003      .1       0  5731.6     .05       0
  5903.1      .1       0
Bank Sta=4997,5003
XS Rating Curve= 0 ,0
Exp/Cntr=0.3,0.1

Type RM Length L Ch R = 1 ,472     ,0,0,0
BEGIN DESCRIPTION:
UNT037 IN SUCR 1.0
END DESCRIPTION:
XS GIS Cut Line= 4
      2272075.37     13431607.47      2272508.74     13431021.84
      2272391.61     13430711.44      2271208.54     13430453.75
#Sta/Elev= 30
  4153.8  327.27  4260.4  324.44  4390.9  321.67  4649.8  318.61  4791.7  316.03
  4820.1  316.44    4868  315.24  4870.8  314.74    4874  315.24  4941.1   317.2
  4956.6  317.18  4981.4  315.92  5122.9  317.85  5443.4  318.99  5583.2  319.62
  5617.2  319.83  5627.5  320.54  5647.9  319.74  5682.9  320.41  5760.5  320.37
  5779.5  320.49  5981.9  321.37  6139.2   322.4  6197.2  323.53  6231.3  323.43
  6251.8  324.31  6272.2  323.92    6303   324.5  6339.3  325.59  6424.9  326.48
#Mann= 11 ,-1 , 0
  4153.8      .1       0  4260.4     .05       0    4868     .03       0
    4874     .05       0  5122.9      .1       0  5443.4     .05       0
  5583.2      .1       0  5760.5     .05       0  5779.5      .1       0
  5981.9     .05       0    6303      .1       0
Bank Sta=4868,4874
XS Rating Curve= 0 ,0
Exp/Cntr=0.3,0.1

Chan Stop Cuts=-1
Use User Specified Reach Order=0
Composite Channel Slope=5