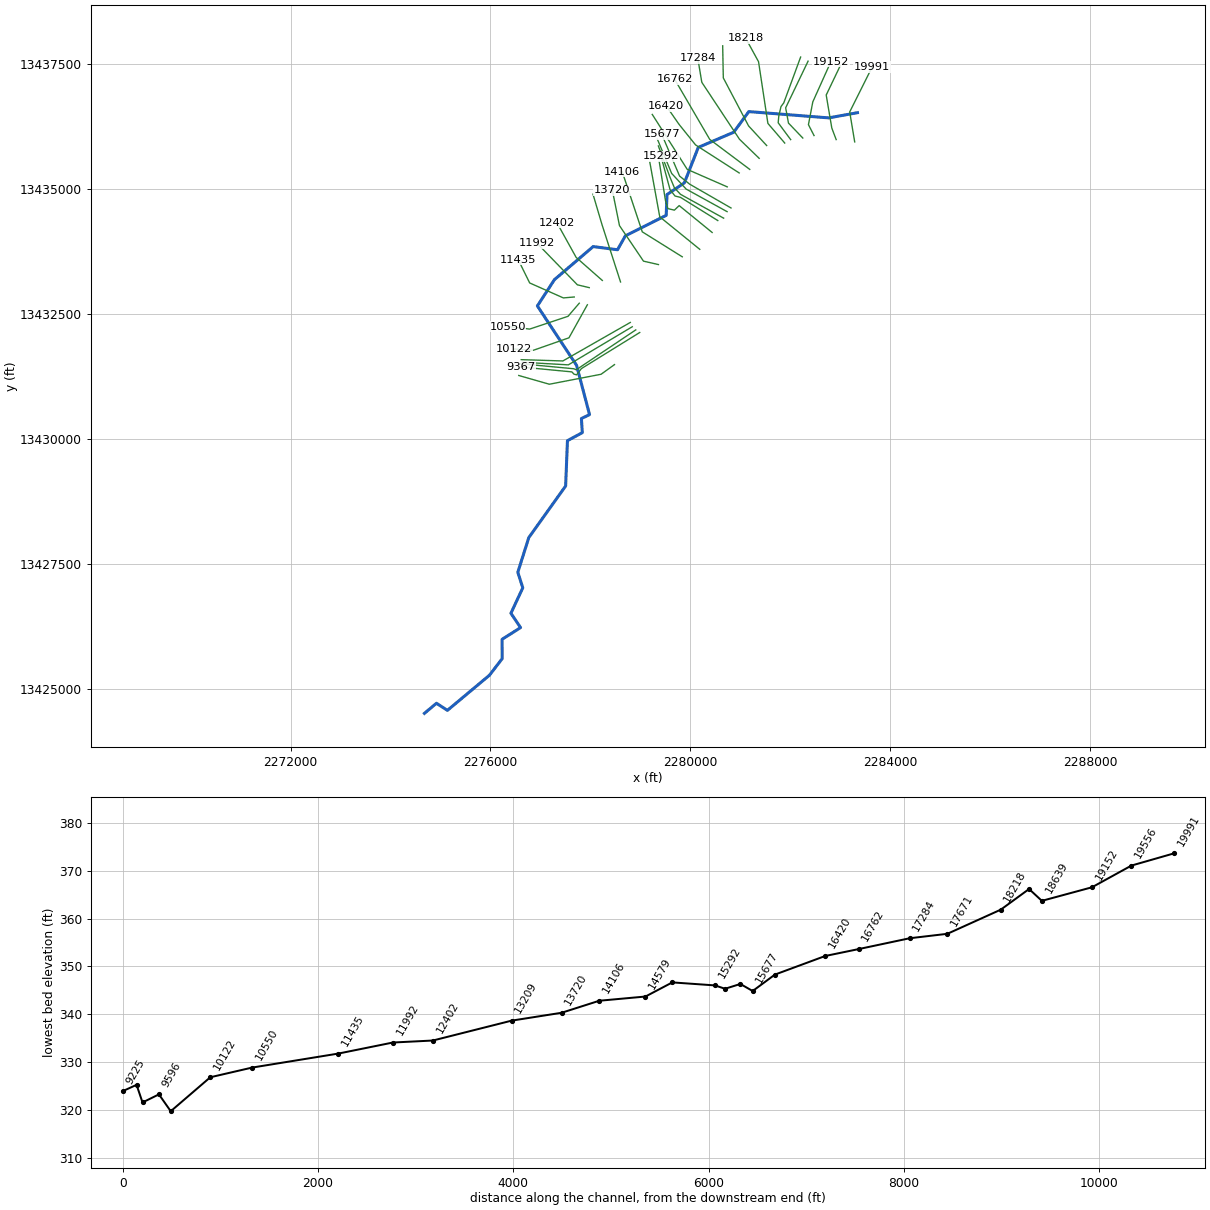
--- UNT038 IN SUCR.prj (project) ---

Proj Title=UNT038 IN SUCR Base Level Engineering
Current Plan=p01
Default Exp/Contr=0.3,0.1
English Units
Geom File=g01
Flow File=f01
Plan File=p01
Y Axis Title=Elevation
X Axis Title(PF)=Main Channel Distance
X Axis Title(XS)=Station
BEGIN DESCRIPTION:
UNT038 IN SUCR
END DESCRIPTION:
DSS Export Rating Curves= 0
DSS Export Rating Curve Sorted= 0
DSS Export Volume Flow Curves= 0
DXF OffsetX= 0
DXF OffsetY= 0
DXF ScaleX= 1
DXF ScaleY= 10

--- UNT038 IN SUCR.p01 (plan) ---

Plan Title=Multiple Run
Short Identifier=Multiple
Geom File=g01
Flow File=f01
Subcritical Flow
K Sum by GR= 0
Std Step Tol= 0.01
Critical Tol= 0.01
Num of Std Step Trials= 20
Max Error Tol= 0.3
Flow Tol Ratio= 0.001
Split Flow NTrial= 30
Split Flow Tol= 0.02
Split Flow Ratio= 0.02
Log Output Level= 0
Friction Slope Method= 1
Unsteady Friction Slope Method= 2
Unsteady Bridges Friction Slope Method= 1
Parabolic Critical Depth
Global Vel Dist=  1 , 1 , 1
Global Log Level= 0
CheckData=True
Encroach Param= -1, 0, 0, 0
BEGIN DESCRIPTION:
Multiple Run
END DESCRIPTION:

--- UNT038 IN SUCR.f01 (steady flow) ---

Flow Title=Multiple
Program Version=4.10
Number of Profiles= 7
Profile Names=10-year,25-year,50-year,1pct_min,100-year,1pct_plu,500-year
River Rch & RM=UNT038 IN SUCR,Reach-1         ,19991
     161     215     257     227     307     415     443
River Rch & RM=UNT038 IN SUCR,Reach-1         ,19556
     297     409     502     452     612     828     924
River Rch & RM=UNT038 IN SUCR,Reach-1         ,13720
     361     503     620     563     761    1029    1161
River Rch & RM=UNT038 IN SUCR,Reach-1         ,7927
     424     594     737     671     907    1227    1395
River Rch & RM=UNT038 IN SUCR,Reach-1         ,4641
     462     651     810     740    1000    1353    1548
Boundary for River Rch & Prof#=UNT038 IN SUCR,Reach-1         , 1
Up Type= 0
Dn Type= 3
Dn Slope=0.0073
Boundary for River Rch & Prof#=UNT038 IN SUCR,Reach-1         , 2
Up Type= 0
Dn Type= 3
Dn Slope=0.0073
Boundary for River Rch & Prof#=UNT038 IN SUCR,Reach-1         , 3
Up Type= 0
Dn Type= 3
Dn Slope=0.0073
Boundary for River Rch & Prof#=UNT038 IN SUCR,Reach-1         , 4
Up Type= 0
Dn Type= 3
Dn Slope=0.0073
Boundary for River Rch & Prof#=UNT038 IN SUCR,Reach-1         , 5
Up Type= 0
Dn Type= 3
Dn Slope=0.0073
Boundary for River Rch & Prof#=UNT038 IN SUCR,Reach-1         , 6
Up Type= 0
Dn Type= 3
Dn Slope=0.0073
Boundary for River Rch & Prof#=UNT038 IN SUCR,Reach-1         , 7
Up Type= 0
Dn Type= 3
Dn Slope=0.0073
DSS Import GetInterval= 0
DSS Import GetPeak= 0
DSS Import FillOption= 0

--- UNT038 IN SUCR.g01 (geometry) ---

Geom Title=Existing Conditions
Program Version=4.10

River Reach=UNT038 IN SUCR  ,Reach-1
Reach XY= 30
      2283343.02      13436531.7      2282768.09      13436427.8
      2281168.92     13436553.64      2280866.06     13436139.52
      2280158.23     13435836.85        2279880.     13435127.21
      2279532.86     13434892.98      2279516.25     13434476.92
      2278699.85     13434066.76      2278542.29     13433788.12
      2278055.01     13433851.34      2277278.83     13433187.59
      2276939.18     13432663.09      2277722.86     13431474.86
      2277982.77     13430487.74      2277820.16     13430409.47
      2277837.72     13430126.85      2277540.74     13429965.58
      2277504.32      13429058.4      2276767.83     13428026.52
      2276547.55      13427331.1      2276647.38     13427020.77
      2276409.85     13426511.21      2276602.76     13426224.27
      2276233.01     13425989.55      2276235.54     13425603.25
      2275980.69     13425270.77      2275139.17     13424567.05
      2274920.39     13424709.68      2274678.62     13424506.95

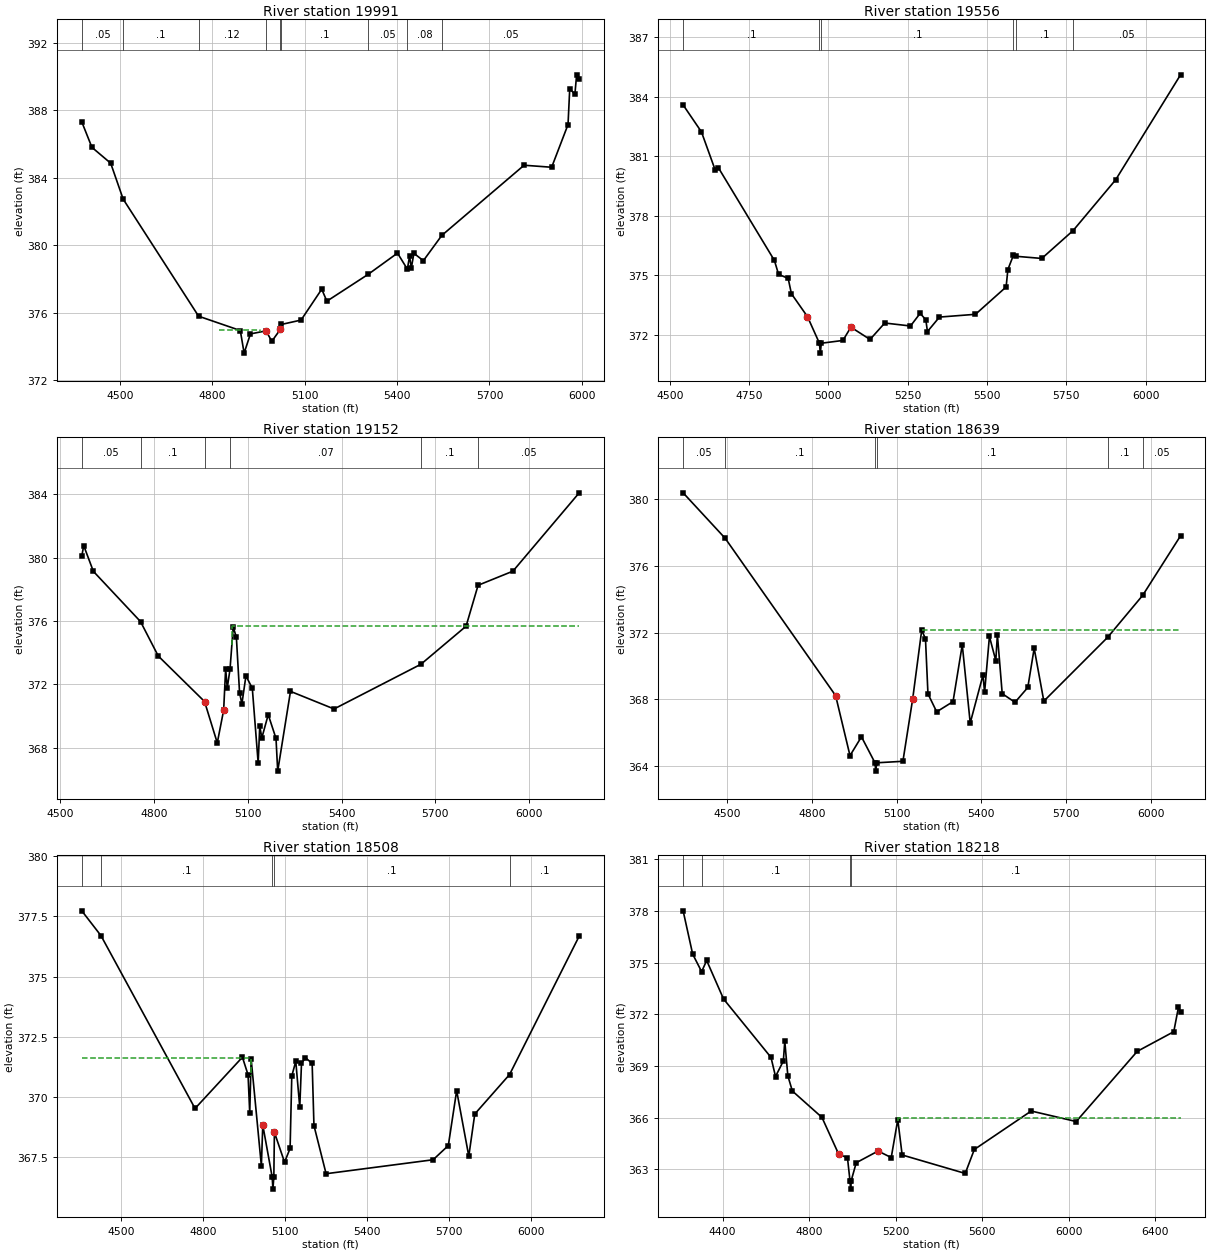
Type RM Length L Ch R = 1 ,19991   ,435,435,435
BEGIN DESCRIPTION:
UNT038 IN SUCR 36.0
END DESCRIPTION:
XS GIS Cut Line= 3
      2283287.72     13435946.85      2283187.72     13436546.85
      2283637.72     13437446.85
#Sta/Elev= 30
  4376.8  387.31  4409.7   385.8  4470.6  384.86  4511.1  382.73  4755.9  375.79
  4891.3  374.94  4903.7   373.6  4924.2  374.74  4974.9  374.92  4993.5   374.3
  5021.4  375.01  5024.6   375.3  5088.5  375.56  5155.6  377.39  5172.3  376.68
  5306.2  378.27  5401.5  379.53  5433.5  378.58  5440.7  379.35  5446.3  378.64
  5454.7  379.52  5485.4  379.08  5545.4  380.58  5812.4  384.74  5901.9  384.62
    5955  387.15  5960.6  389.28  5977.3  388.94  5982.9   390.1  5991.3  389.83
#Mann= 9 ,-1 , 0
  4376.8     .05       0  4511.1      .1       0  4755.9     .12       0
  4974.9     .07       0  5021.4     .12       0  5024.6      .1       0
  5306.2     .05       0  5433.5     .08       0  5545.4     .05       0
#XS Ineff= 1 ,-1
 4821.55  4953.8  374.99
Permanent Ineff=
       T
Bank Sta=4974.9,5021.4
XS Rating Curve= 0 ,0
Exp/Cntr=0.3,0.1

Type RM Length L Ch R = 1 ,19556   ,404,404,404
BEGIN DESCRIPTION:
UNT038 IN SUCR 35.0
END DESCRIPTION:
XS GIS Cut Line= 4
      2282917.22     13435992.92      2282829.91     13436223.69
      2282717.62     13436884.93      2282998.32     13437471.27
#Sta/Elev= 30
  4542.2  383.59  4599.9  382.23  4643.8  380.28  4653.3  380.42  4829.8  375.74
  4842.9  375.04  4873.3  374.83  4883.4  374.06  4934.1   372.9  4971.7  371.56
  4974.5  371.06  4977.7  371.56  5045.7   371.7  5070.9  372.37  5131.2  371.75
  5177.6  372.58  5258.7  372.43  5289.2  373.07    5307  372.74  5312.1  372.15
    5350  372.88  5463.5  373.02    5560   374.4  5565.6  375.28  5582.7  375.99
  5590.4  375.95  5672.4  375.84  5771.3  377.25  5905.2  379.81  6109.7  385.11
#Mann= 6 ,-1 , 0
  4542.2      .1       0  4971.7     .07       0  4977.7      .1       0
  5582.7     .05       0  5590.4      .1       0  5771.3     .05       0
Bank Sta=4934.1,5070.9
XS Rating Curve= 0 ,0
Exp/Cntr=0.3,0.1

Type RM Length L Ch R = 1 ,19152   ,513,513,513
BEGIN DESCRIPTION:
Mapping XS d6f0899a
END DESCRIPTION:
XS GIS Cut Line= 4
      2282474.35     13436073.95      2282362.05     13436292.31
      2282449.38     13436747.69      2282811.06      13437552.1
#Sta/Elev= 30
    4569  380.09  4575.2  380.75    4606  379.13  4756.9  375.96  4813.6  373.79
  4961.7  370.92  5002.4  368.31  5022.8  370.37  5029.2  372.99  5034.3  371.77
  5043.2  372.96  5053.4  375.62  5063.5  374.97  5073.7  371.48  5081.2  370.77
  5094.1  372.54  5114.5  371.75  5133.2  367.05  5138.3  369.36    5145  368.63
  5165.4  370.09  5190.3  368.59  5195.7  366.53  5236.6  371.56    5376  370.45
  5653.9  373.27  5798.3  375.67  5836.7  378.25  5948.2  379.14  6160.2  384.08
#Mann= 6 ,-1 , 0
    4569     .05       0  4756.9      .1       0  4961.7     .05       0
  5043.2     .07       0  5653.9      .1       0  5836.7     .05       0
#XS Ineff= 2 , 0
       0                 5048.95       0  375.66
Permanent Ineff=
       F       T
Bank Sta=4961.7,5022.8
XS Rating Curve= 0 ,0
Exp/Cntr=0.3,0.1

Type RM Length L Ch R = 1 ,18639   ,131,131,131
BEGIN DESCRIPTION:
UNT038 IN SUCR 34.0
END DESCRIPTION:
XS GIS Cut Line= 4
      2282249.75     13436024.08      2281962.81      13436323.5
      2281906.67     13436629.17      2282355.07     13437563.33
#Sta/Elev= 30
  4344.3   380.4  4493.3  377.67  4884.4  368.23  4935.3  364.63  4975.9  365.76
  5023.8   364.2  5026.5   363.7  5029.8   364.2  5122.7  364.29  5157.3  368.03
  5189.2  372.15  5202.6  371.65  5211.4  368.34  5242.3  367.26  5300.2  367.87
  5332.9  371.28  5361.1  366.59  5406.4  369.47    5412  368.42  5429.1  371.78
  5451.7  370.33  5457.3  371.89  5474.4  368.35  5519.7  367.83    5565  368.72
  5587.6  371.07  5621.8   367.9  5847.8  371.73    5972  374.25    6106  377.82
#Mann= 6 ,-1 , 0
  4344.3     .05       0  4493.3      .1       0  5023.8     .07       0
  5029.8      .1       0  5847.8      .1       0    5972     .05       0
#XS Ineff= 2 , 0
       0                 5189.26       0  372.17
Permanent Ineff=
       F       T
Bank Sta=4884.4,5157.3
XS Rating Curve= 0 ,0
Exp/Cntr=0.3,0.1

Type RM Length L Ch R = 1 ,18508   ,290,290,290
BEGIN DESCRIPTION:
UNT038 IN SUCR 33.0
END DESCRIPTION:
XS GIS Cut Line= 6
      2282006.45     13435992.92      2281756.95     13436329.74
      2281769.43     13436466.98       2281813.1     13436654.12
      2281869.24     13436728.98      2282206.09     13437645.95
#Sta/Elev= 30
  4355.6  377.73  4425.7   376.7  4769.9  369.52  4943.2  371.65  4963.8  370.92
    4970  369.32  4975.1  371.58  5012.5  367.14  5017.7  368.83  5052.1  366.67
  5054.8  366.17  5058.1  366.67  5060.2  368.53  5097.3  367.29  5117.6  367.86
  5123.8  370.87  5138.4  371.48    5153  369.57  5159.3  371.39  5173.8  371.63
  5198.3  371.39  5204.9  368.81  5249.3  366.81  5640.8  367.39  5696.4  367.98
  5726.9  370.26  5771.3  367.54  5793.2  369.29  5920.5  370.93  6175.2  376.68
#Mann= 5 ,-1 , 0
  4355.6     .05       0  4425.7      .1       0  5052.1     .07       0
  5058.1      .1       0  5920.5      .1       0
#XS Ineff= 2 , 0
       0 4973.47  371.61 5192.26       0  371.35
Permanent Ineff=
       T       T
Bank Sta=5017.7,5060.2
XS Rating Curve= 0 ,0
Exp/Cntr=0.3,0.1

Type RM Length L Ch R = 1 ,18218   ,547,547,547
BEGIN DESCRIPTION:
UNT038 IN SUCR 32.0
END DESCRIPTION:
XS GIS Cut Line= 4
      2281887.94     13435924.28       2281551.1     13436317.26
      2281363.95      13437552.4       2281108.2     13438020.24
#Sta/Elev= 30
  4217.6     378  4261.7  375.49  4303.2  374.47  4326.4  375.12  4404.4  372.89
  4623.9   369.5  4644.8  368.39    4681  369.29  4687.6  370.44  4701.8  368.43
  4722.7  367.55  4859.5  366.02  4937.1  363.88  4977.5  363.68    4989  362.36
  4991.8  361.86    4995  362.36    5018  363.39  5119.1  364.07  5179.8  363.69
  5210.1  365.89  5230.4  363.84    5522  362.77  5564.1  364.16  5827.1  366.39
  6035.1  365.78  6317.4  369.85  6486.3  370.99  6508.1  372.42  6517.6  372.11
#Mann= 4 ,-1 , 0
  4217.6     .05       0  4303.2      .1       0    4989     .07       0
    4995      .1       0
#XS Ineff= 2 , 0
       0                 5211.16       0  365.97
Permanent Ineff=
       F       T
Bank Sta=4937.1,5119.1
XS Rating Curve= 0 ,0
Exp/Cntr=0.3,0.1

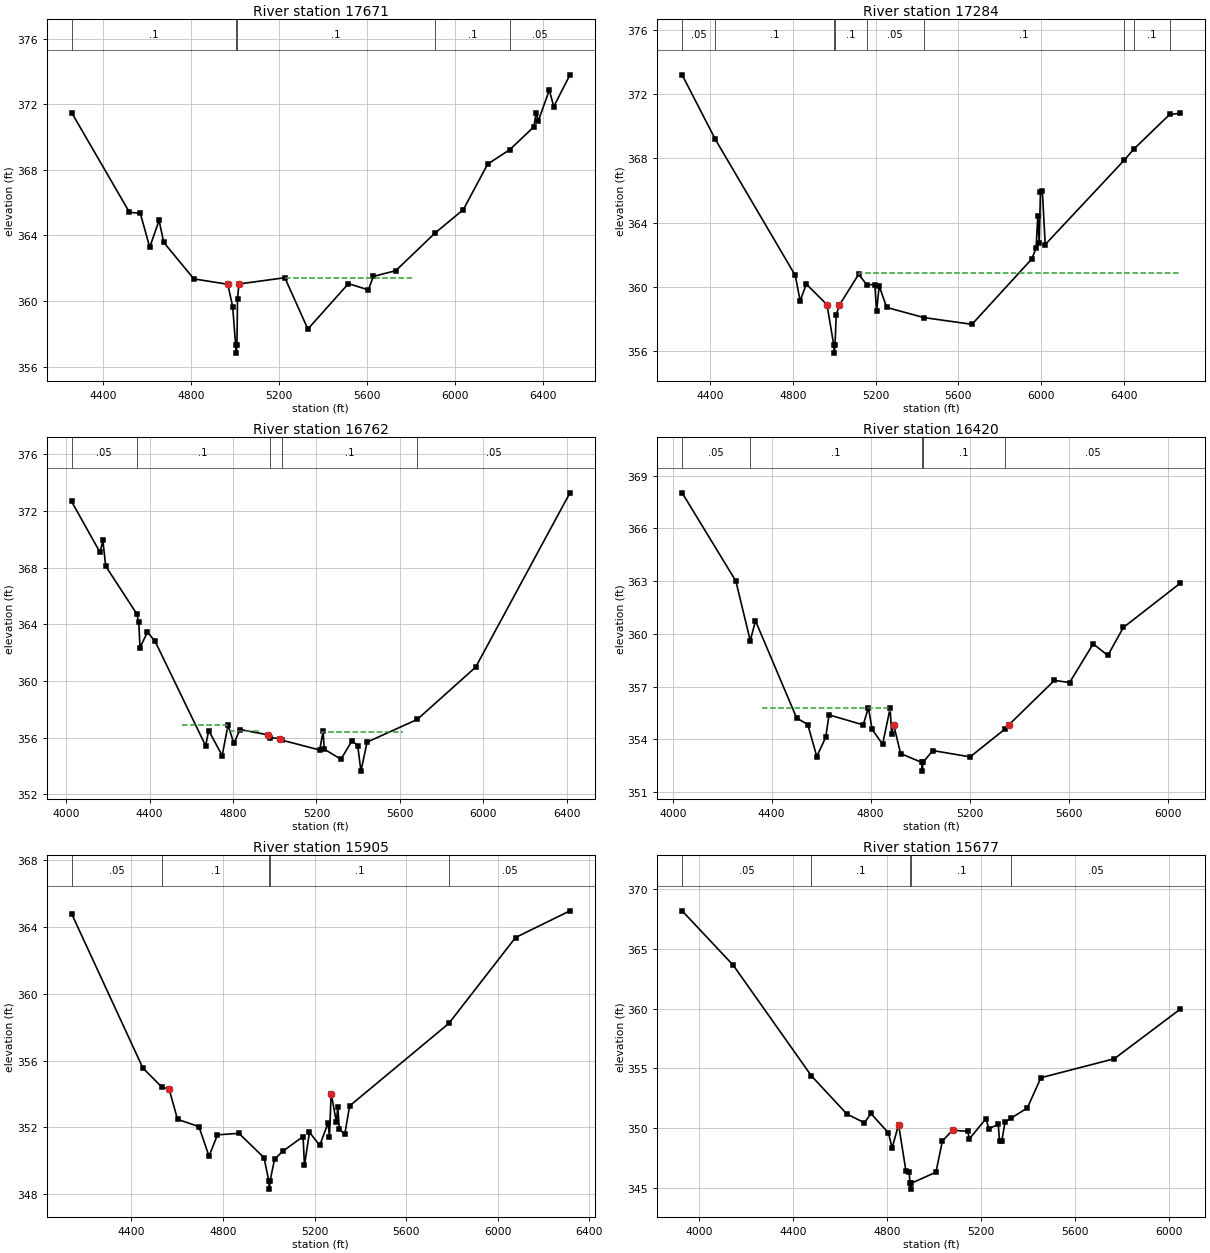
Type RM Length L Ch R = 1 ,17671   ,387,387,387
BEGIN DESCRIPTION:
UNT038 IN SUCR 31.0
END DESCRIPTION:
XS GIS Cut Line= 4
      2281526.15     13435874.36      2281164.34     13436267.36
      2280659.05     13437228.02      2280646.57     13437870.57
#Sta/Elev= 30
  4258.4   371.5  4520.7  365.42  4570.6  365.34  4613.1  363.28  4655.6  364.92
  4676.6  363.58  4813.3  361.35  4967.5  361.02  4989.6  359.65    5003  357.32
  5005.7  356.82    5009  357.32  5011.6  360.15    5018  361.04  5226.4  361.42
  5330.9  358.29  5515.1  361.06  5605.5  360.68  5628.1   361.5  5729.8  361.85
  5906.9  364.13  6036.9  365.58  6146.9  368.35    6248  369.24    6357  370.63
    6367  371.47    6377  370.99    6427  372.87    6447  371.86  6520.7   373.8
#Mann= 5 ,-1 , 0
  4258.4      .1       0    5003     .07       0    5009      .1       0
  5906.9      .1       0    6248     .05       0
#XS Ineff= 1 ,-1
 5226.94 5807.35  361.42
Permanent Ineff=
       T
Bank Sta=4967.5,5018
XS Rating Curve= 0 ,0
Exp/Cntr=0.3,0.1

Type RM Length L Ch R = 1 ,17284   ,522,522,522
BEGIN DESCRIPTION:
UNT038 IN SUCR 30.0
END DESCRIPTION:
XS GIS Cut Line= 4
      2281376.43     13435618.59      2280983.43     13435999.12
      2280228.62     13437140.69      2280147.52     13437627.29
#Sta/Elev= 30
  4264.7  373.19  4425.6  369.17  4811.7  360.72  4835.1  359.14  4865.2  360.18
  4964.9   358.9  4997.8  356.39  5000.6  355.89  5003.8  356.39  5009.6  358.27
  5024.7  358.87    5118  360.79  5156.7  360.15  5196.2  360.14  5204.6  358.48
  5217.3  360.07  5253.4  358.73  5433.4   358.1  5665.7  357.68  5954.6  361.74
  5975.6  362.41  5983.9   364.4  5990.7  362.71  5996.7  365.89  6005.8  365.99
  6019.8  362.64  6402.8   367.9  6448.5  368.58  6621.6  370.73  6673.6   370.8
#Mann= 9 ,-1 , 0
  4264.7     .05       0  4425.6      .1       0  4997.8     .07       0
  5003.8      .1       0  5156.7     .05       0  5433.4      .1       0
  6402.8     .05       0  6448.5      .1       0  6621.6     .05       0
#XS Ineff= 2 , 0
       0                 5121.18       0  360.88
Permanent Ineff=
       F       T
Bank Sta=4964.9,5024.7
XS Rating Curve= 0 ,0
Exp/Cntr=0.3,0.1

Type RM Length L Ch R = 1 ,16762   ,342,342,342
BEGIN DESCRIPTION:
UNT038 IN SUCR 29.0
END DESCRIPTION:
XS GIS Cut Line= 3
      2281187.74     13435396.84      2280387.72     13435996.85
      2279687.71     13437196.88
#Sta/Elev= 30
  4025.9  372.68  4162.4  369.08  4175.9  369.93  4189.5  368.11  4338.3  364.74
  4347.8  364.16  4354.1  362.36  4389.5  363.45  4425.9  362.81  4668.6  355.42
  4683.2   356.5  4747.8  354.73  4775.9  356.87  4804.1  355.59  4833.2  356.57
  4968.6  356.19  4975.9     356  5022.8  355.93  5033.8  355.82  5215.7  355.12
  5231.4  356.46  5237.2  355.18  5317.4  354.47  5370.3  355.78  5397.6  355.43
  5413.1  353.63  5442.7  355.68    5683  357.28  5963.3  360.98  6415.2  373.29
#Mann= 5 ,-1 , 0
  4025.9     .05       0  4338.3      .1       0  4975.9     .07       0
  5033.8      .1       0    5683     .05       0
#XS Ineff= 3 ,-1
  4555.1 4771.43  356.92 4779.59 4918.37  356.45 5228.57 5614.29   356.4
Permanent Ineff=
       T       T       T
Bank Sta=4968.6,5022.8
XS Rating Curve= 0 ,0
Exp/Cntr=0.3,0.1

Type RM Length L Ch R = 1 ,16420   ,515,515,515
BEGIN DESCRIPTION:
UNT038 IN SUCR 28.0
END DESCRIPTION:
XS GIS Cut Line= 4
      2280977.21     13435325.39      2280103.86     13435886.83
      2279773.24     13436298.55      2279517.46     13436666.62
#Sta/Elev= 30
    4038  368.02  4255.3     363  4313.5  359.61  4334.6  360.74    4501  355.21
  4545.9  354.84  4582.3  353.02  4618.6  354.12  4631.8  355.39  4769.8  354.82
    4791  355.79  4806.2  354.56  4848.4  353.72  4878.8  355.76  4884.8  354.32
  4893.3  354.82  4921.1  353.19  5005.9  352.69  5008.7  352.19  5011.9  352.69
  5051.2  353.36    5202     353  5344.6   354.6  5358.4  354.82  5542.8  357.35
  5604.3  357.23  5699.6  359.43  5758.7  358.77  5821.5  360.36  6052.5  362.89
#Mann= 5 ,-1 , 0
    4038     .05       0  4313.5      .1       0  5005.9     .07       0
  5011.9      .1       0  5344.6     .05       0
#XS Ineff= 1 ,-1
 4359.18 4879.59   355.8
Permanent Ineff=
       T
Bank Sta=4893.3,5358.4
XS Rating Curve= 0 ,0
Exp/Cntr=0.3,0.1

Type RM Length L Ch R = 1 ,15905   ,228,228,228
BEGIN DESCRIPTION:
UNT038 IN SUCR 27.0
END DESCRIPTION:
XS GIS Cut Line= 3
      2280737.68     13435046.87      2279937.72     13435396.85
      2279237.72     13436496.85
#Sta/Elev= 30
  4138.8   364.8  4450.2  355.56  4533.7  354.41  4564.4  354.32  4601.5  352.49
    4695  352.05  4739.1  350.28  4776.1  351.56  4869.7  351.65  4979.6  350.19
    5000  348.81  5002.8  348.31    5006  348.81  5025.5  350.11  5061.9  350.58
    5150  351.46  5155.9  349.73  5177.9  351.71  5222.8  350.93  5259.2  352.27
  5265.1  351.46  5272.7  354.03  5295.6  352.32  5301.5  353.24  5308.3  351.91
    5332  351.59  5353.2  353.29  5786.7  358.23  6077.9  363.37  6315.8  364.97
#Mann= 5 ,-1 , 0
  4138.8     .05       0  4533.7      .1       0    5000     .07       0
    5006      .1       0  5786.7     .05       0
Bank Sta=4564.4,5272.7
XS Rating Curve= 0 ,0
Exp/Cntr=0.3,0.1

Type RM Length L Ch R = 1 ,15677   ,126,126,126
BEGIN DESCRIPTION:
Mapping XS f42ebc77
END DESCRIPTION:
XS GIS Cut Line= 4
      2280813.48     13434624.37      2279984.46     13435101.81
       2279784.8      13435262.4      2279428.88     13436095.78
#Sta/Elev= 30
  3928.6  368.21  4146.4  363.64  4478.5  354.37  4629.1  351.18  4703.8  350.44
  4731.5  351.22  4805.9  349.59  4821.6  348.33    4849  350.29  4880.5  346.38
  4893.9   346.3  4897.8  345.38  4900.6  344.88  4903.8  345.38    5008   346.3
  5035.2  348.91  5078.4  349.82  5144.2  349.72  5149.3  349.08  5220.1  350.77
  5233.3  349.96  5272.8   350.3  5278.2  348.93  5287.7   348.9  5301.8  350.51
  5328.2  350.84  5396.2  351.68  5454.3  354.22  5766.2  355.81  6047.7  359.98
#Mann= 5 ,-1 , 0
  3928.6     .05       0  4478.5      .1       0  4897.8     .07       0
  4903.8      .1       0  5328.2     .05       0
Bank Sta=4849,5078.4
XS Rating Curve= 0 ,0
Exp/Cntr=0.3,0.1

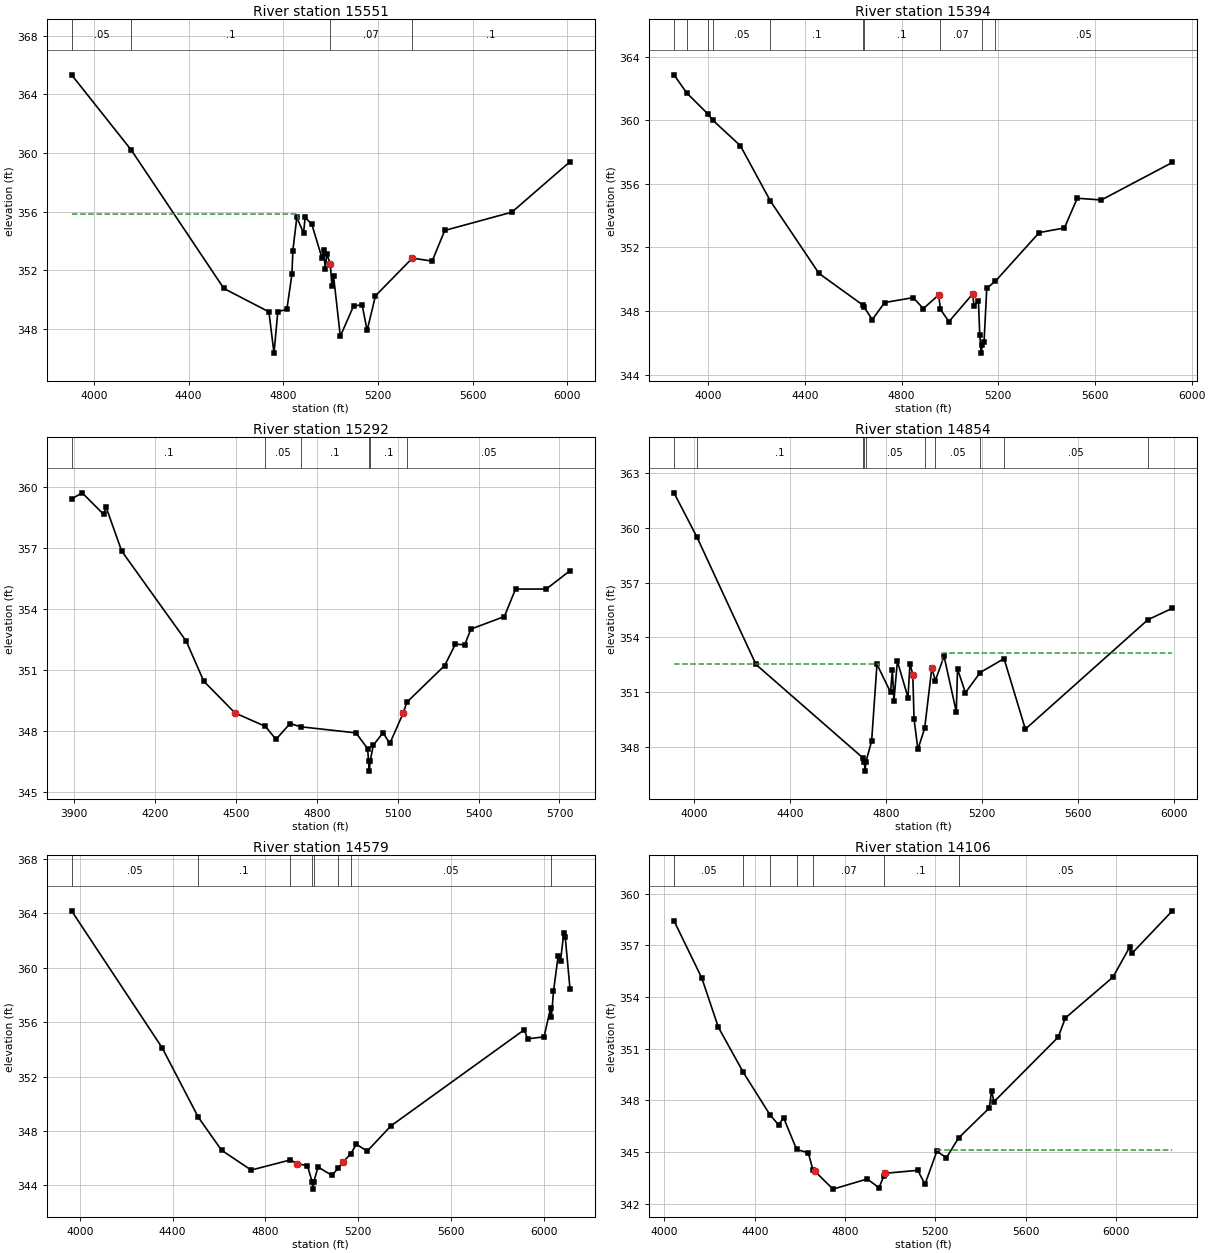
Type RM Length L Ch R = 1 ,15551   ,157,157,157
BEGIN DESCRIPTION:
UNT038 IN SUCR 26.0
END DESCRIPTION:
XS GIS Cut Line= 4
       2280735.3     13434550.61      2279916.16     13435002.24
       2279625.4     13435316.43      2279339.81     13436001.84
#Sta/Elev= 30
  3905.5  365.34  4158.1   360.2    4549  350.76  4739.3  349.17  4760.8  346.35
  4777.1  349.19    4815  349.33  4836.7  351.73  4840.5  353.35  4857.3  355.61
  4885.7  354.55  4892.5  355.62  4920.8  355.13  4963.4  352.85  4970.2  353.42
  4977.5  352.12  4984.3   353.1  4998.5  352.45  5005.9  350.91  5012.7  351.59
    5041   347.5  5097.7  349.59  5133.3  349.63  5154.4   347.9  5189.6  350.26
  5345.3  352.83  5429.2  352.63  5482.3  354.72  5766.1  355.97  6011.5  359.41
#Mann= 4 ,-1 , 0
  3905.5     .05       0  4158.1      .1       0  4998.5     .07       0
  5345.3      .1       0
#XS Ineff= 2 , 0
       0 4864.08  355.86               0
Permanent Ineff=
       T       F
Bank Sta=4998.5,5345.3
XS Rating Curve= 0 ,0
Exp/Cntr=0.3,0.1

Type RM Length L Ch R = 1 ,15394   ,102,102,102
BEGIN DESCRIPTION:
Mapping XS eb36b1d0
END DESCRIPTION:
XS GIS Cut Line= 5
      2280665.84     13434420.41      2279802.17     13434897.82
      2279680.64     13435028.03      2279593.83     13435236.36
      2279359.46     13435865.69
#Sta/Elev= 30
    3858  362.85  3911.3   361.7  3998.7  360.38  4018.4     360  4132.8  358.39
  4257.1  354.91  4458.1  350.36  4638.8  348.38    4643  348.28  4678.5  347.46
  4729.6  348.53  4847.6  348.84  4889.7  348.15  4953.2  349.01  4960.5   348.1
  4995.7  347.33  5093.8  349.07  5099.2  348.33  5117.7  348.65  5123.1  346.51
  5129.8  345.35    5133  345.85  5140.8  346.03  5152.3  349.43  5188.3  349.88
  5369.2  352.93  5473.3  353.22  5526.6  355.09  5626.2  354.98  5920.2  357.34
#Mann= 10 ,-1 , 0
    3858      .1       0  3911.3     .05       0  3998.7      .1       0
  4018.4     .05       0  4257.1      .1       0  4638.8     .05       0
    4643      .1       0  4960.5     .07       0    5133      .1       0
  5188.3     .05       0
#XS Ineff= 1 ,-1
 5091.84 5181.63  348.77
Permanent Ineff=
       T
Bank Sta=4953.2,5093.8
XS Rating Curve= 0 ,0
Exp/Cntr=0.3,0.1

Type RM Length L Ch R = 1 ,15292   ,438,438,438
BEGIN DESCRIPTION:
Mapping XS 760792b4
END DESCRIPTION:
XS GIS Cut Line= 5
      2280548.67     13434372.66      2279802.17     13434837.06
      2279693.66      13434863.1      2279593.83     13434988.97
      2279411.54      13435661.7
#Sta/Elev= 30
  3890.6  359.43  3929.9  359.73  4009.5  358.67  4018.5  359.03  4076.3  356.87
  4315.7  352.44  4380.9  350.47  4496.6  348.91  4609.2  348.25  4648.8  347.61
  4700.8  348.39  4740.1  348.23  4945.4  347.93  4988.3  347.16  4992.1  346.55
  4994.8  346.05  4998.1  346.55  5009.5  347.32  5045.6  347.94  5070.9  347.41
  5120.1  348.89  5134.2  349.44  5274.3  351.24  5314.1  352.29  5348.8  352.26
  5371.4  353.03  5495.7  353.65  5537.1     355  5651.1     355    5739   355.9
#Mann= 6 ,-1 , 0
  3890.6      .1       0  4609.2     .05       0  4740.1      .1       0
  4992.1     .07       0  4998.1      .1       0  5134.2     .05       0
Bank Sta=4496.6,5120.1
XS Rating Curve= 0 ,0
Exp/Cntr=0.3,0.1

Type RM Length L Ch R = 1 ,14854   ,275,275,275
BEGIN DESCRIPTION:
Mapping XS ed1ff3a2
END DESCRIPTION:
XS GIS Cut Line= 6
      2280435.83     13434133.95      2279776.12     13434672.13
      2279680.64     13434580.98      2279550.43     13434611.36
      2279502.69     13434767.61      2279376.92     13435552.54
#Sta/Elev= 30
  3915.9  361.92  4011.8  359.49    4258  352.52  4705.4  347.39  4710.3  347.18
    4713  346.68  4716.3  347.18  4740.5  348.32  4762.8  352.53  4819.4     351
    4827   352.2  4833.6  350.54  4847.9   352.7  4892.2  350.71  4900.5  352.57
  4912.3  351.96  4917.4  349.55  4933.5  347.87  4961.8  349.03  4991.5  352.32
  5006.3  351.64  5042.7  352.97  5093.7  349.93  5098.9  352.28  5131.7  350.97
  5193.4  352.08    5293  352.84  5381.9  348.98  5893.2  354.97  5995.3   355.6
#Mann= 10 ,-1 , 0
  3915.9     .05       0  4011.8      .1       0  4705.4     .05       0
  4710.3     .07       0  4716.3     .05       0  4961.8      .1       0
  5006.3     .05       0  5193.4      .1       0    5293     .05       0
  5893.2      .1       0
#XS Ineff= 2 , 0
       0 4769.39  352.56 5034.69       0  353.15
Permanent Ineff=
       T       T
Bank Sta=4912.3,4991.5
XS Rating Curve= 0 ,0
Exp/Cntr=0.3,0.1

Type RM Length L Ch R = 1 ,14579   ,473,473,473
BEGIN DESCRIPTION:
UNT038 IN SUCR 25.0
END DESCRIPTION:
XS GIS Cut Line= 3
      2280187.72     13433796.86      2279387.72     13434446.85
      2279187.72     13435546.85
#Sta/Elev= 30
  3964.5  364.18  4355.2  354.11  4510.6  349.02    4611  346.59  4738.8  345.13
  4906.6  345.87  4938.5  345.61  4981.6  345.44  5002.4  344.23  5005.2  343.73
  5008.4  344.23    5027  345.36  5086.7  344.74  5113.1  345.25  5133.8   345.7
  5168.8  346.34  5192.2  347.03  5239.2  346.52  5340.8  348.37  5916.4  355.44
  5930.4  354.77  6001.5  354.92  6029.7  357.03  6033.3  356.35  6042.2  358.26
  6062.5  360.88  6072.7  360.52  6086.6  362.55    6093  362.23  6113.3  358.46
#Mann= 8 ,-1 , 0
  3964.5     .05       0  4510.6      .1       0  4906.6     .05       0
  5002.4    .035       0  5008.4     .05       0  5113.1      .1       0
  5168.8     .05       0  6029.7      .1       0
Bank Sta=4938.5,5133.8
XS Rating Curve= 0 ,0
Exp/Cntr=0.3,0.1

Type RM Length L Ch R = 1 ,14106   ,386,386,386
BEGIN DESCRIPTION:
UNT038 IN SUCR 24.0
END DESCRIPTION:
XS GIS Cut Line= 3
      2279837.73     13433646.85      2279037.72     13434146.85
      2278637.73     13435346.83
#Sta/Elev= 30
  4042.4  358.42  4165.6   355.1  4238.8  352.25  4349.7  349.62  4467.8  347.16
  4506.4  346.57  4527.7     347  4585.9  345.15  4637.3  344.96  4658.6  343.94
  4667.4  343.88    4747  342.85  4899.1  343.44  4950.4  342.93  4972.2   343.6
  4978.1  343.77  5122.8  343.94  5154.5  343.13  5207.2  345.05  5249.3  344.67
  5303.4  345.82  5439.1  347.55  5449.6  348.56  5460.2  347.92  5744.8  351.67
  5776.4  352.78  5987.2  355.15    6061  356.88  6071.5  356.53  6250.7     359
#Mann= 7 ,-1 , 0
  4042.4     .05       0  4349.7      .1       0  4467.8     .08       0
  4585.9      .1       0  4658.6     .07       0  4972.2      .1       0
  5303.4     .05       0
#XS Ineff= 2 , 0
                         5208.16           345.1
Permanent Ineff=
       F       F
Bank Sta=4667.4,4978.1
XS Rating Curve= 0 ,0
Exp/Cntr=0.3,0.1

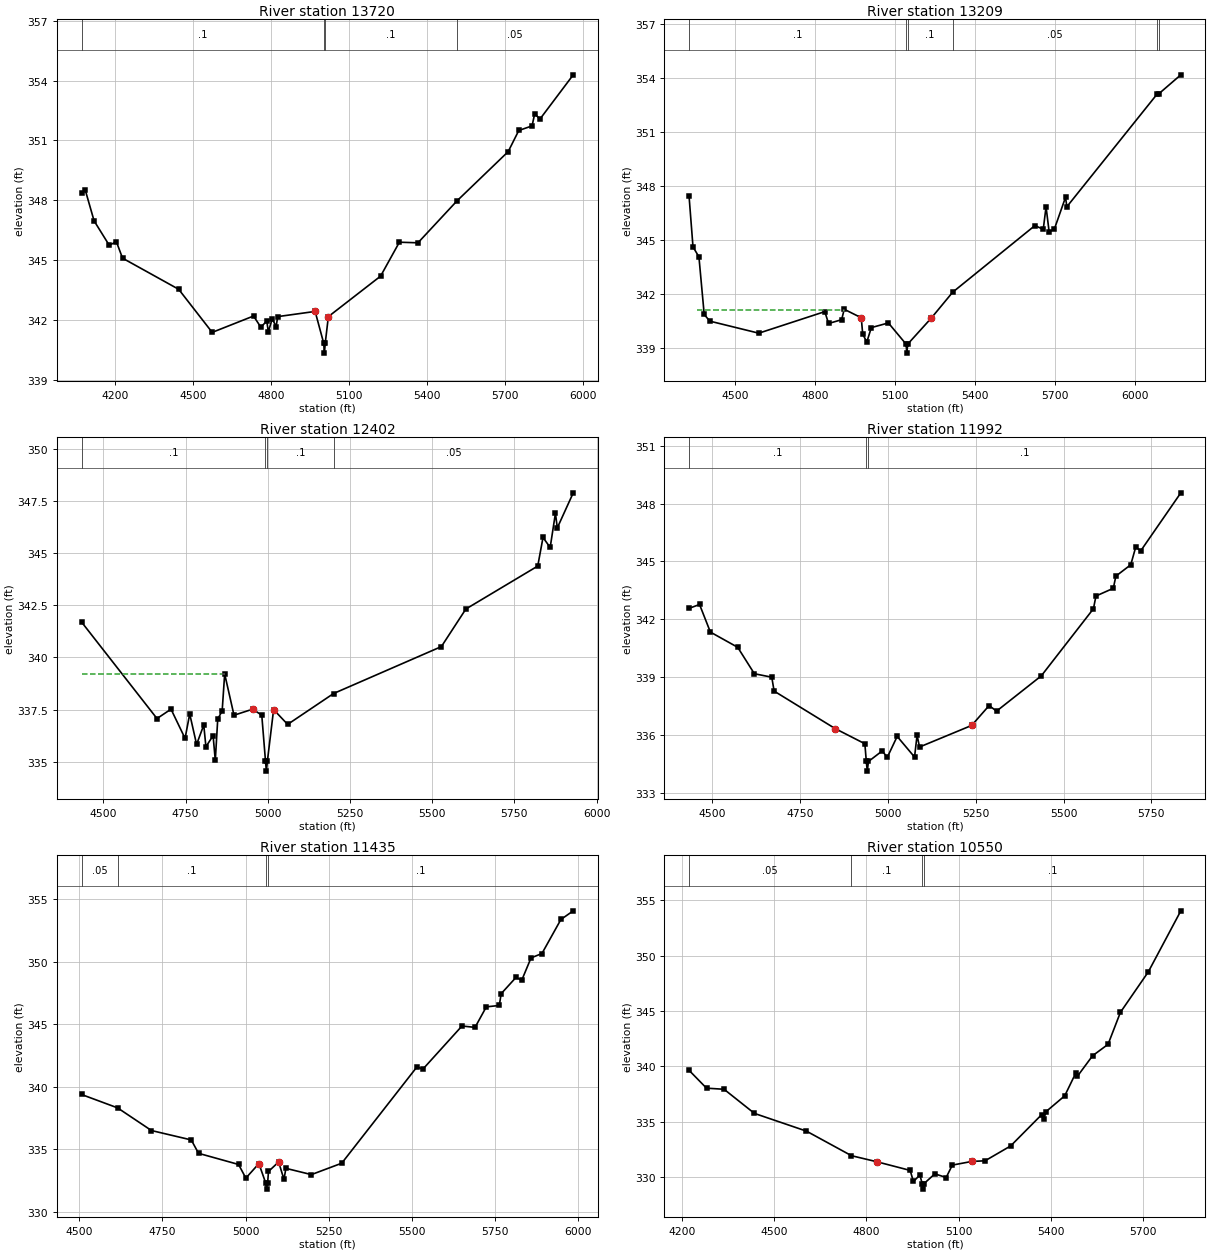
Type RM Length L Ch R = 1 ,13720   ,511,511,511
BEGIN DESCRIPTION:
UNT038 IN SUCR 23.0
END DESCRIPTION:
XS GIS Cut Line= 4
      2279361.51     13433491.41       2279062.1     13433560.02
      2278581.76     13434271.17      2278438.33     13434982.11
#Sta/Elev= 30
  4072.5  348.35  4086.6  348.53  4120.9  346.97    4179  345.75  4206.7  345.92
  4230.3   345.1  4446.1  343.54    4575  341.38  4733.9   342.2    4762  341.64
  4784.8  341.95  4790.8  341.41  4805.8  342.06  4820.8  341.67  4826.8  342.17
  4970.7  342.43  5003.6  340.84  5006.4  340.34  5009.6  340.84  5021.6  342.17
  5222.4   344.2  5294.6   345.9  5366.1  345.87    5516  347.97  5712.9  350.44
  5753.7   351.5  5804.7  351.73  5814.9  352.34    5835  352.07  5963.1  354.29
#Mann= 4 ,-1 , 0
  4072.5      .1       0  5003.6     .07       0  5009.6      .1       0
    5516     .05       0
Bank Sta=4970.7,5021.6
XS Rating Curve= 0 ,0
Exp/Cntr=0.3,0.1

Type RM Length L Ch R = 1 ,13209   ,807,807,807
BEGIN DESCRIPTION:
Mapping XS bbe5f0a6
END DESCRIPTION:
XS GIS Cut Line= 3
      2278602.83     13433142.85      2278232.43     13434289.88
      2278051.52     13434901.22
#Sta/Elev= 30
    4329  347.42  4343.7  344.61  4365.9  344.06  4385.7  340.85  4406.8  340.48
  4590.2  339.81  4837.6  341.01  4851.7  340.35  4900.7  340.56  4910.5  341.14
  4974.2  340.67  4979.8  339.75  4995.2  339.32  5011.9  340.12  5075.9  340.38
  5142.3   339.2    5145   338.7  5148.3   339.2  5236.1  340.64  5316.8  342.09
  5625.1   345.8  5656.3  345.59  5666.8  346.84  5678.4  345.45  5698.1  345.61
  5739.7  347.37  5744.9  346.85  6084.2  353.14  6090.6  353.15  6171.9  354.19
#Mann= 6 ,-1 , 0
    4329      .1       0  5142.3     .07       0  5148.3      .1       0
  5316.8     .05       0  6084.2      .1       0  6090.6     .05       0
#XS Ineff= 1 ,-1
 4357.14 4908.16   341.1
Permanent Ineff=
       T
Bank Sta=4974.2,5236.1
XS Rating Curve= 0 ,0
Exp/Cntr=0.3,0.1

Type RM Length L Ch R = 1 ,12402   ,410,410,410
BEGIN DESCRIPTION:
UNT038 IN SUCR 22.0
END DESCRIPTION:
XS GIS Cut Line= 3
      2278238.65     13433173.28      2277714.67     13433634.88
      2277328.38     13434332.69
#Sta/Elev= 30
  4433.2   341.7  4662.8  337.07  4705.5  337.52  4748.2  336.12  4762.4  337.29
  4783.3  335.83  4805.1  336.76  4811.7  335.72  4833.5  336.25  4840.2  335.06
  4847.6  337.04  4861.1  337.44  4868.7  339.21  4897.1  337.23    4954  337.52
  4981.6  337.23  4992.8  335.05  4995.6  334.55  4998.8  335.05  5017.6   337.5
  5060.3  336.79    5200  338.27    5528  340.52  5602.4  342.32  5821.1  344.38
  5837.1  345.75  5858.9  345.27  5874.9  346.91  5880.6  346.21  5929.1  347.89
#Mann= 4 ,-1 , 0
  4433.2      .1       0  4992.8     .07       0  4998.8      .1       0
    5200     .05       0
#XS Ineff= 2 , 0
       0  4868.9  339.22               0
Permanent Ineff=
       T       F
Bank Sta=4954,5017.6
XS Rating Curve= 0 ,0
Exp/Cntr=0.3,0.1

Type RM Length L Ch R = 1 ,11992   ,557,557,557
BEGIN DESCRIPTION:
Mapping XS 64979f11
END DESCRIPTION:
XS GIS Cut Line= 3
      2277976.69     13433029.78      2277739.62     13433085.93
      2276934.94     13433915.56
#Sta/Elev= 30
  4434.3  342.57  4464.1  342.77  4494.9  341.34  4572.7  340.55  4620.1  339.18
  4669.6     339  4676.3  338.28  4849.6  336.34  4934.5  335.55  4938.7  334.63
  4941.4  334.13  4944.7  334.63  4984.1  335.18  4998.2  334.84  5026.5  335.93
  5075.9  334.86  5083.1  335.99  5090.1  335.38  5238.5   336.5  5288.2  337.53
  5309.3  337.24  5436.6  339.07    5585  342.55  5592.2  343.21  5641.6  343.61
  5648.8  344.24  5691.2  344.83  5705.4  345.75  5719.5  345.55  5833.7  348.56
#Mann= 3 ,-1 , 0
  4434.3      .1       0  4938.7     .07       0  4944.7      .1       0
Bank Sta=4849.6,5238.5
XS Rating Curve= 0 ,0
Exp/Cntr=0.3,0.1

Type RM Length L Ch R = 1 ,11435   ,885,885,885
BEGIN DESCRIPTION:
UNT038 IN SUCR 21.0
END DESCRIPTION:
XS GIS Cut Line= 4
      2277677.25     13432842.64      2277458.91     13432823.93
      2276785.19     13433123.36      2276554.38     13433591.22
#Sta/Elev= 30
    4507  339.39  4615.5  338.32  4717.3  336.51  4836.9  335.76  4858.8  334.69
  4979.1   333.8    5001  332.71  5040.2  333.87  5060.5  332.33  5063.2  331.83
  5066.5  332.33    5069  333.24  5099.5     334  5115.5  332.61  5121.4  333.49
    5198  332.99  5289.2   333.9  5515.8  341.61  5532.7   341.4  5650.6  344.86
  5689.9  344.75  5723.8  346.39  5762.8   346.5  5768.4  347.44  5813.3  348.75
  5830.2  348.51  5858.2   350.3    5891  350.65    5948  353.37  5985.1  354.06
#Mann= 4 ,-1 , 0
    4507     .05       0  4615.5      .1       0  5060.5     .07       0
  5066.5      .1       0
Bank Sta=5040.2,5099.5
XS Rating Curve= 0 ,0
Exp/Cntr=0.3,0.1

Type RM Length L Ch R = 1 ,10550   ,428,428,428
BEGIN DESCRIPTION:
UNT038 IN SUCR 20.0
END DESCRIPTION:
XS GIS Cut Line= 4
      2277777.07      13432717.9      2277552.48     13432455.88
      2276785.19     13432200.12      2276342.49       13432250.
#Sta/Elev= 30
    4223  339.63  4279.7  338.02  4336.8  337.92  4435.6  335.74  4604.7  334.14
  4751.2  331.92  4832.6  331.38  4942.1  330.59  4952.6  329.59  4973.7  330.17
  4981.2   329.4    4984   328.9  4987.2   329.4  5022.3  330.28  5059.2  329.95
  5079.1  331.07  5142.3   331.4  5185.7  331.46  5268.8   332.8  5370.2  335.64
  5376.9  335.26  5384.4  335.91  5444.8  337.33  5480.9   339.4  5485.9  339.09
  5535.4  340.95  5585.7  341.98  5625.9  344.87  5716.5  348.52  5822.4  354.04
#Mann= 4 ,-1 , 0
    4223     .05       0  4751.2      .1       0  4981.2     .07       0
  4987.2      .1       0
Bank Sta=4832.6,5142.3
XS Rating Curve= 0 ,0
Exp/Cntr=0.3,0.1

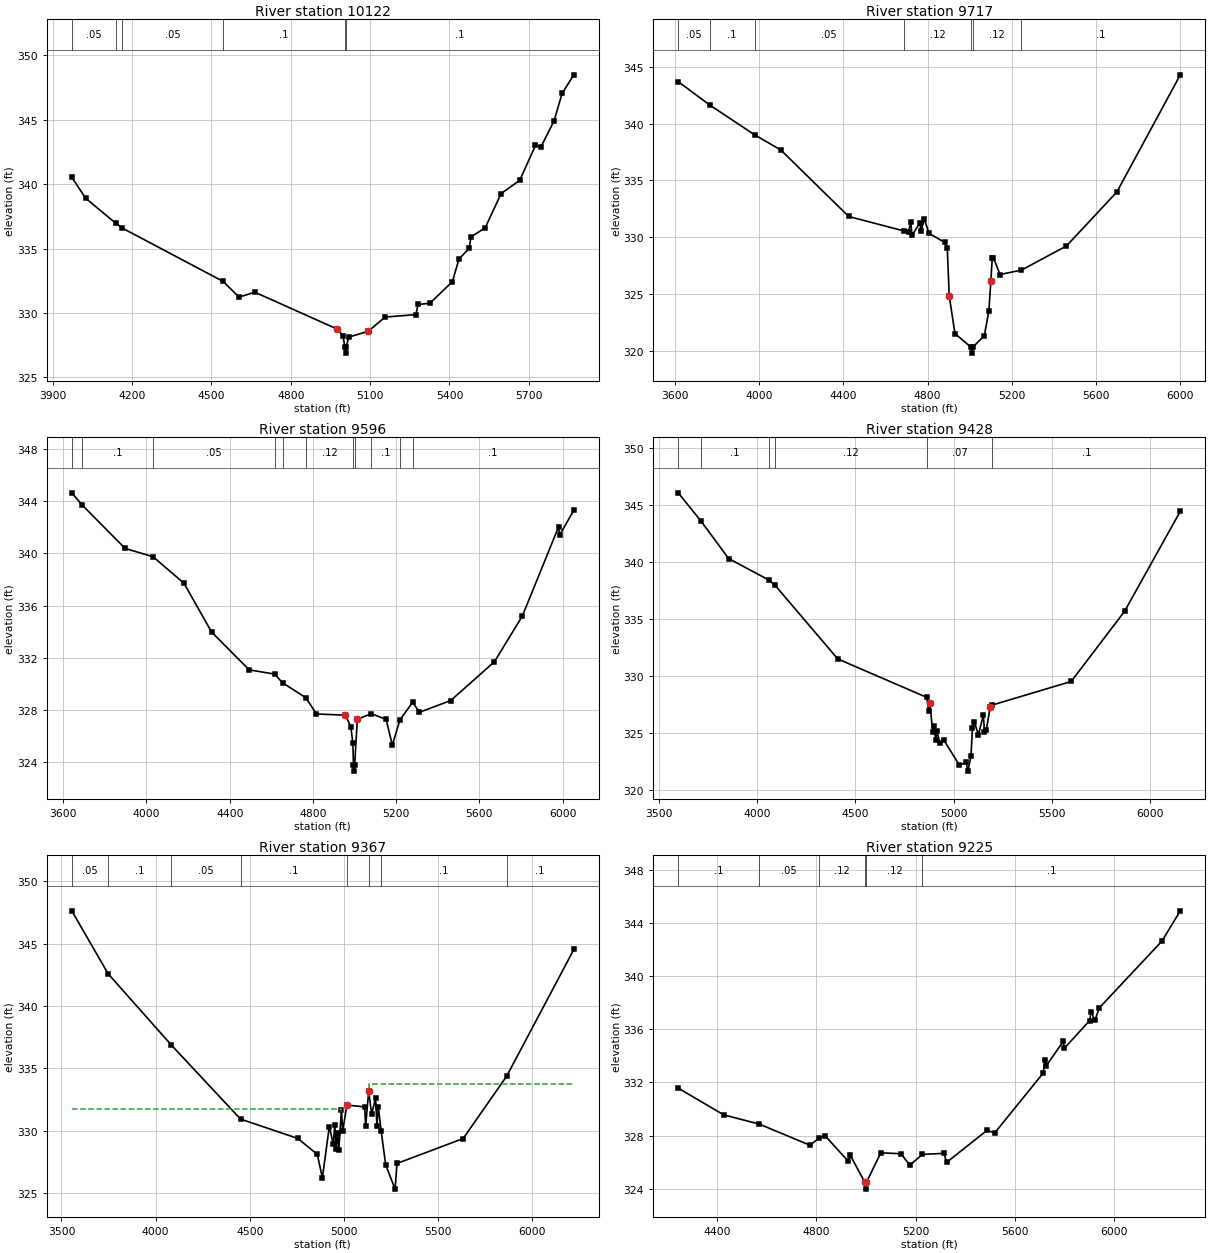
Type RM Length L Ch R = 1 ,10122   ,405,405,405
BEGIN DESCRIPTION:
UNT038 IN SUCR 19.0
END DESCRIPTION:
XS GIS Cut Line= 4
      2277939.25     13432686.71      2277571.19     13432025.45
      2276860.05     13431775.93      2276473.29     13431800.88
#Sta/Elev= 30
  3972.2  340.53  4025.1   338.9  4138.1  336.97  4163.3  336.59  4544.1  332.45
  4604.8  331.23  4664.3  331.61  4976.3  328.74  4997.6  328.22  5004.3  327.38
  5007.1  326.88  5010.3  327.38  5018.8  328.12    5093  328.58  5156.6  329.68
  5273.2  329.87    5281  330.66  5326.1  330.75  5410.9  332.43    5436  334.19
  5474.5  335.01  5481.2   335.9  5535.1  336.61  5595.2  339.27  5665.3  340.29
  5725.2  343.01  5745.5  342.88  5795.6  344.92  5825.7  347.05  5870.2  348.49
#Mann= 6 ,-1 , 0
  3972.2     .05       0  4138.1      .1       0  4163.3     .05       0
  4544.1      .1       0  5004.3     .07       0  5010.3      .1       0
Bank Sta=4976.3,5093
XS Rating Curve= 0 ,0
Exp/Cntr=0.3,0.1

Type RM Length L Ch R = 1 ,9717    ,121,121,121
BEGIN DESCRIPTION:
Mapping XS 9d2bb43a
END DESCRIPTION:
XS GIS Cut Line= 3
      2278798.53     13432332.77      2277449.56     13431561.93
      2276616.25     13431587.97
#Sta/Elev= 30
  3614.3  343.69  3763.3  341.64  3977.3  339.01  4102.3  337.67  4424.8  331.82
  4686.5  330.55  4709.9  330.48  4719.9  331.35  4725.7  330.16  4763.1  331.24
  4768.9  330.52  4784.7   331.6  4806.3  330.34  4881.2  329.54  4893.7  329.03
  4902.8  324.83  4930.1  321.51  5007.7  320.29  5010.5  319.79  5013.7  320.29
  5069.8  321.33  5091.4  323.52    5101  326.17  5107.2  328.14    5113  328.19
  5144.6  326.71  5246.3   327.1    5460  329.22  5700.1  333.98  6001.7  344.29
#Mann= 7 ,-1 , 0
  3614.3     .05       0  3763.3      .1       0  3977.3     .05       0
  4686.5     .12       0  5007.7     .07       0  5013.7     .12       0
  5246.3      .1       0
Bank Sta=4902.8,5101
XS Rating Curve= 0 ,0
Exp/Cntr=0.3,0.1

Type RM Length L Ch R = 1 ,9596    ,168,168,168
BEGIN DESCRIPTION:
UNT038 IN SUCR 18.0
END DESCRIPTION:
XS GIS Cut Line= 3
      2278837.74     13432246.87      2277558.93      13431483.8
      2276637.07     13431535.88
#Sta/Elev= 30
  3641.2  344.64  3689.8  343.73  3897.4  340.38  4031.9  339.74  4180.3  337.71
  4312.7  333.98  4493.6  331.07  4615.8  330.75    4654  330.08  4766.4  328.93
  4816.7  327.69  4954.9   327.6  4982.1  326.73  4991.9  325.43  4994.7  323.81
  4997.5  323.31  5000.7  323.81  5013.3  327.29    5081  327.71  5151.6  327.27
  5181.7   325.3  5217.4  327.22  5279.1  328.59  5311.9  327.82  5462.1  328.72
  5672.4   331.7  5806.3   335.2  5980.1  342.02  5985.1  341.39  6053.7  343.31
#Mann= 11 ,-1 , 0
  3641.2     .05       0  3689.8      .1       0  4031.9     .05       0
  4615.8      .1       0    4654     .05       0  4766.4     .12       0
  4994.7     .07       0  5000.7     .12       0    5081      .1       0
  5217.4     .12       0  5279.1      .1       0
Bank Sta=4954.9,5013.3
XS Rating Curve= 0 ,0
Exp/Cntr=0.3,0.1

Type RM Length L Ch R = 1 ,9428    ,61,61,61
BEGIN DESCRIPTION:
Mapping XS e961f3bf
END DESCRIPTION:
XS GIS Cut Line= 4
      2278907.18     13432183.39      2277716.23      13431384.8
      2277667.62     13431405.63      2276605.08     13431506.33
#Sta/Elev= 30
  3598.5  346.05  3715.3  343.55  3854.7  340.28  4060.3  338.39  4091.8  337.92
  4409.9  331.47  4863.1  328.09  4872.1  326.88  4878.1  327.59  4893.1  325.09
  4899.1  325.56  4908.1  324.35  4914.1  325.17  4929.1  324.11  4950.1  324.33
  5028.5  322.15  5063.4  322.38    5072  321.62  5087.8  322.96  5095.2  325.42
  5105.3  325.92  5125.4   324.8  5150.9  326.56  5155.9  325.09  5165.6  325.22
  5185.6  327.26  5195.7  327.42  5597.5  329.49  5868.7  335.64  6152.6  344.43
#Mann= 6 ,-1 , 0
  3598.5     .05       0  3715.3      .1       0  4060.3     .05       0
  4091.8     .12       0  4863.1     .07       0  5195.7      .1       0
Bank Sta=4878.1,5185.6
XS Rating Curve= 0 ,0
Exp/Cntr=0.3,0.1

Type RM Length L Ch R = 1 ,9367    ,142,142,142
BEGIN DESCRIPTION:
Mapping XS 5959e81e
END DESCRIPTION:
XS GIS Cut Line= 6
      2278987.07     13432131.33      2277820.39     13431409.11
      2277723.17     13431284.11      2277671.09     13431297.99
      2277629.42     13431343.13      2276612.38     13431440.33
#Sta/Elev= 30
  3554.6  347.63  3748.3  342.57  4084.3  336.85  4451.2  330.92  4754.9  329.37
    4859  328.09  4886.1  326.21  4922.8  330.31  4943.9  328.92  4952.1  330.46
  4958.4  328.55  4966.5   329.8  4972.9  328.41  4987.3  331.64  4993.7  329.93
  5016.3  332.04  5110.7   331.9  5115.9  330.35  5132.1  333.17  5147.8  331.32
  5168.8  332.59  5176.1  330.34  5182.9  331.91  5198.3     330  5222.2  327.26
  5272.2   325.3  5282.5  327.36  5634.1  329.36  5865.1  334.36  6222.1  344.53
#Mann= 8 ,-1 , 0
  3554.6     .05       0  3748.3      .1       0  4084.3     .05       0
  4451.2      .1       0  5016.3     .05       0  5132.1     .12       0
  5198.3      .1       0  5865.1      .1       0
#XS Ineff= 2 , 0
       0 4986.53  331.71 5135.92       0  333.76
Permanent Ineff=
       T       T
Bank Sta=5016.3,5132.1
XS Rating Curve= 0 ,0
Exp/Cntr=0.3,0.1

Type RM Length L Ch R = 1 ,9225    ,452,452,452
BEGIN DESCRIPTION:
UNT038 IN SUCR 17.0
END DESCRIPTION:
XS GIS Cut Line= 4
      2278481.92     13431488.95      2278213.72     13431295.59
      2277178.19     13431095.98      2276566.88     13431270.64
#Sta/Elev= 30
  4244.8  331.57  4428.3  329.56  4570.8  328.87    4775  327.28  4811.3  327.81
  4836.1  327.99  4927.8   326.1    4938  326.51  4996.1  324.48  4998.8  323.98
  5002.1  324.48  5060.2  326.71  5141.7  326.64  5176.8  325.78  5227.7  326.59
  5314.8  326.67    5325  325.99  5487.9   328.4  5518.5   328.2  5713.7   332.7
  5721.6  333.68  5726.8  333.27  5794.4  335.08  5799.6  334.58  5900.9  336.65
  5906.2  337.33  5921.7  336.66    5940  337.61  6192.1  342.63  6265.8   344.9
#Mann= 6 ,-1 , 0
  4244.8      .1       0  4570.8     .05       0  4811.3     .12       0
  4996.1     .07       0  5002.1     .12       0  5227.7      .1       0
Bank Sta=4996.1,5002.1
XS Rating Curve= 0 ,0
Exp/Cntr=0.3,0.1