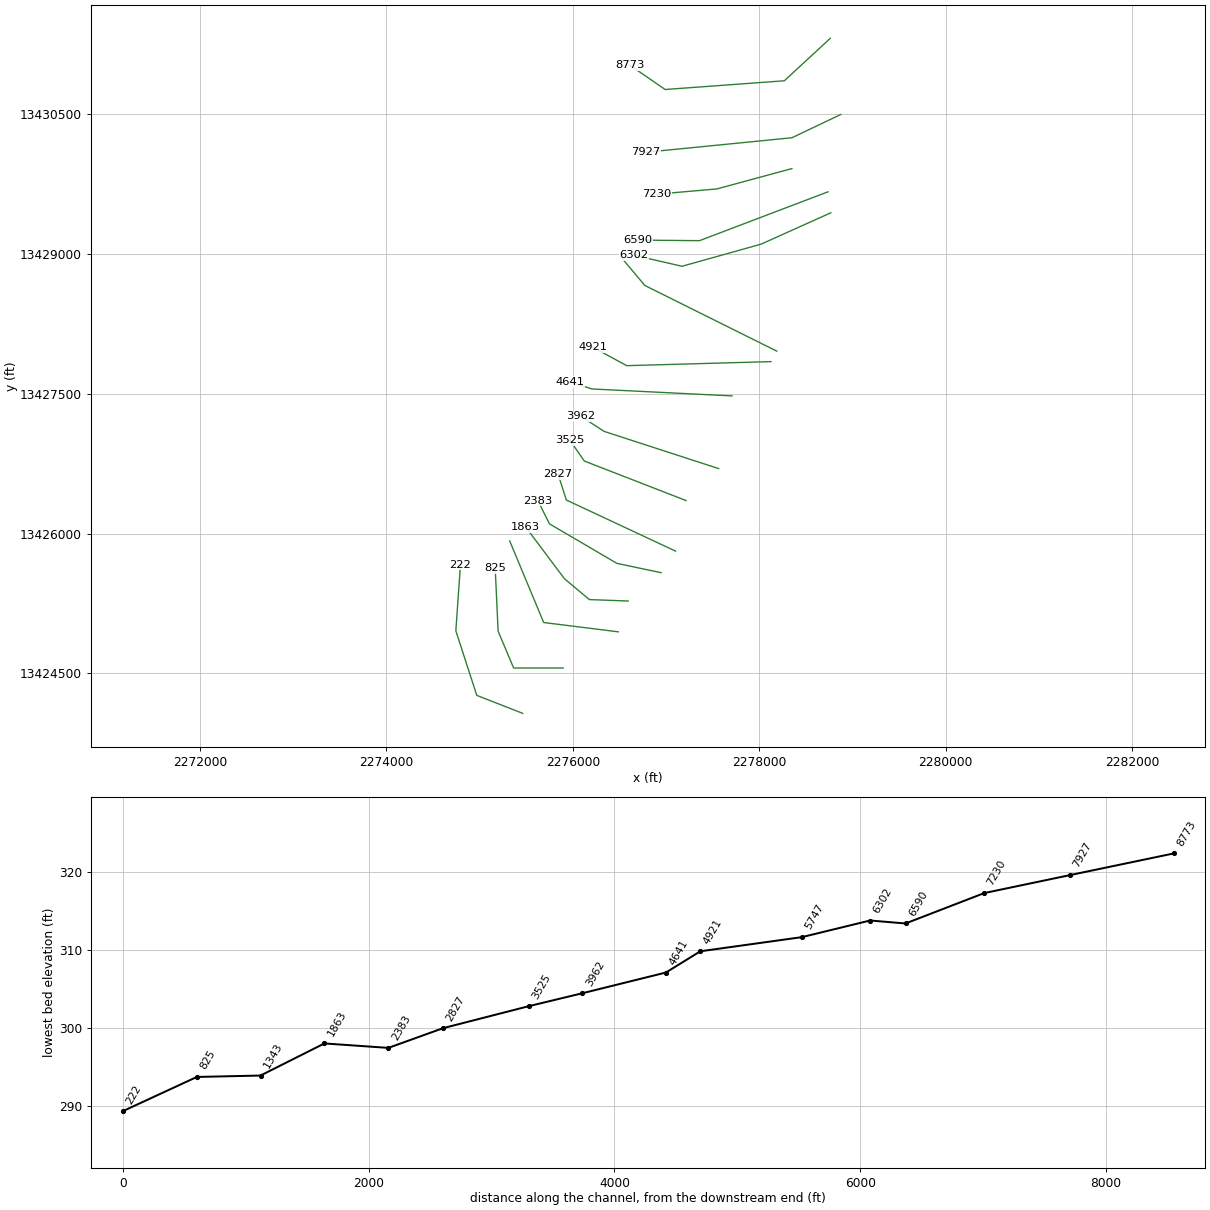
HEC-RAS study UNT038 IN SUCR.prj: UNT038 IN SUCR Base Level Engineering

--- UNT038 IN SUCR.g01 (geometry) --- (continued)

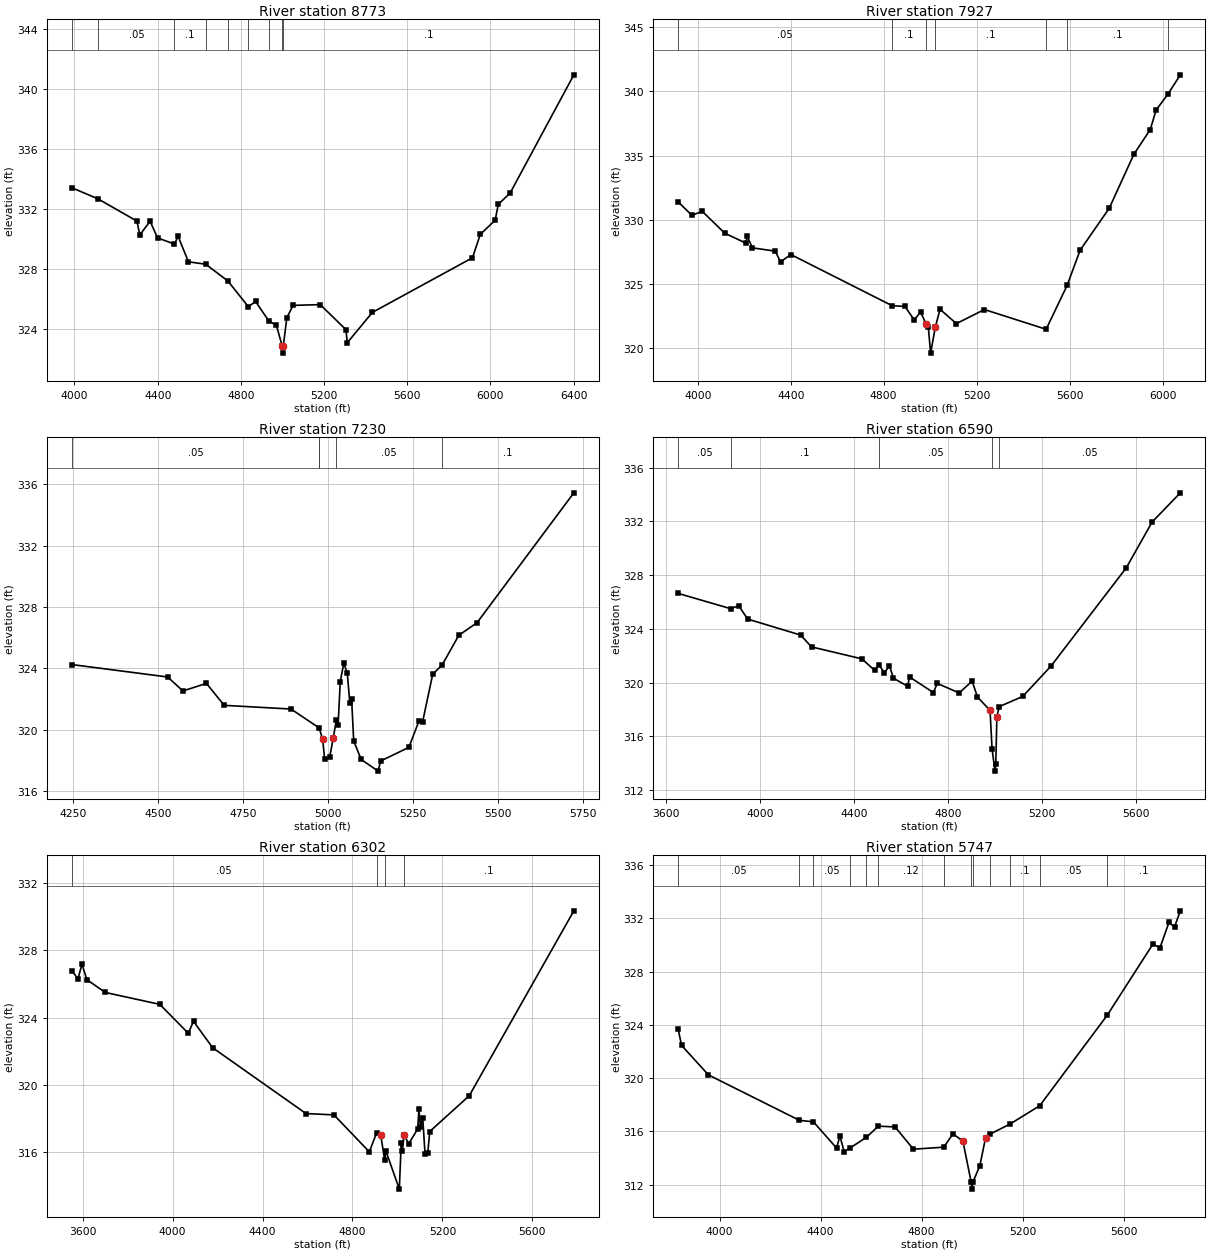
Type RM Length L Ch R = 1 ,8773    ,846,846,846
BEGIN DESCRIPTION:
UNT038 IN SUCR 16.0
END DESCRIPTION:
XS GIS Cut Line= 4
      2278762.69     13431314.33      2278269.86     13430858.93
      2276991.05     13430765.36      2276611.64     13431026.59
#Sta/Elev= 30
  3986.9  333.43  4113.7  332.68    4300   331.2  4314.2  330.28  4363.5  331.19
  4399.2  330.08  4480.8  329.66  4497.9  330.19  4547.8  328.48  4630.5  328.32
  4737.5   327.2  4835.9  325.48  4870.6  325.83  4934.2  324.53  4970.9  324.23
    4998  322.88  5000.7  322.38    5004  322.88    5021  324.75  5051.1  325.57
  5181.5  325.62  5304.9  323.95  5311.8  323.08  5432.1   325.1  5913.4  328.75
  5950.9  330.31  6022.6  331.26  6037.5  332.32  6094.3  333.07  6400.8  340.97
#Mann= 9 ,-1 , 0
  3986.9      .1       0  4113.7     .05       0  4480.8      .1       0
  4630.5     .05       0  4737.5      .1       0  4835.9     .05       0
  4934.2      .1       0    4998     .07       0    5004      .1       0
Bank Sta=4998,5004
XS Rating Curve= 0 ,0
Exp/Cntr=0.3,0.1

Type RM Length L Ch R = 1 ,7927    ,697,697,697
BEGIN DESCRIPTION:
UNT038 IN SUCR 15.0
END DESCRIPTION:
XS GIS Cut Line= 3
      2278874.94     13430497.11      2278350.95     13430247.59
      2276778.94     13430091.64
#Sta/Elev= 30
  3916.1  331.39  3974.4  330.35  4019.8  330.65  4116.2  328.95    4207  328.18
  4212.5  328.72  4235.2  327.81  4333.9  327.55  4356.1  326.71  4400.4  327.29
  4836.3   323.3  4891.6  323.24  4931.8  322.17  4958.4  322.83  4982.1  321.88
  4992.1  321.62  5001.9   319.6  5022.3  321.64  5042.4  323.02  5112.7   321.9
  5233.3     323  5498.9  321.46  5589.2  324.88  5645.3  327.63  5770.5   330.9
  5876.5  335.11  5946.8  337.03  5972.3  338.56  6024.4  339.83  6076.2   341.3
#Mann= 7 ,-1 , 0
  3916.1     .05       0  4836.3      .1       0  4982.1     .07       0
  5022.3      .1       0  5498.9     .12       0  5589.2      .1       0
  6024.4     .05       0
Bank Sta=4982.1,5022.3
XS Rating Curve= 0 ,0
Exp/Cntr=0.3,0.1

Type RM Length L Ch R = 1 ,7230    ,640,640,640
BEGIN DESCRIPTION:
UNT038 IN SUCR 14.0
END DESCRIPTION:
XS GIS Cut Line= 3
      2278350.93     13429916.97      2277546.24     13429698.64
      2276903.67      13429642.5
#Sta/Elev= 30
  4245.5  324.25  4527.9  323.44  4572.9  322.53  4642.2  323.02  4694.4  321.59
  4891.2  321.35  4974.1  320.12  4984.5  319.37  4990.2  318.11  5005.2  318.22
  5015.6  319.45  5024.8  320.64    5030  320.34  5036.3  323.14  5046.7  324.34
    5057  323.69  5064.6  321.72  5069.8  321.98  5075.9  319.27  5097.9  318.06
  5147.8   317.3  5155.2  317.96  5238.4  318.85  5267.8  320.55  5278.6  320.49
  5308.7  323.63  5335.8   324.2  5385.5  326.16  5439.2  326.98  5724.3  335.45
#Mann= 5 ,-1 , 0
  4245.5     .05       0  4974.1     .12       0  4974.1     .03       0
  5024.8     .05       0  5335.8      .1       0
Bank Sta=4984.5,5015.6
XS Rating Curve= 0 ,0
Exp/Cntr=0.3,0.1

Type RM Length L Ch R = 1 ,6590    ,288,288,288
BEGIN DESCRIPTION:
UNT038 IN SUCR 13.0
END DESCRIPTION:
XS GIS Cut Line= 3
      2278737.75     13429667.47       2277359.1     13429143.45
      2276697.91     13429149.69
#Sta/Elev= 30
  3651.4  326.64  3875.4   325.5  3908.2  325.73  3947.1  324.73  4172.1  323.54
  4218.4  322.66  4432.4  321.77  4487.3  320.91  4505.1  321.33  4528.7  320.73
  4550.1  321.26    4567  320.33  4627.2  319.73  4635.6  320.42    4737  319.26
  4753.3  319.94  4846.8  319.23  4901.7  320.11  4924.5  318.93    4978  317.93
  4986.7  315.04  4999.1  313.41  5002.4  313.91  5007.1  317.45  5016.8  318.21
  5117.1  318.97  5237.7  321.24  5557.7  328.55  5667.7  331.96  5787.5  334.13
#Mann= 5 ,-1 , 0
  3651.4     .05       0  3875.4      .1       0  4505.1     .05       0
  4986.7     .03       0  5016.8     .05       0
Bank Sta=4978,5007.1
XS Rating Curve= 0 ,0
Exp/Cntr=0.3,0.1

Type RM Length L Ch R = 1 ,6302    ,555,555,555
BEGIN DESCRIPTION:
UNT038 IN SUCR 12.0
END DESCRIPTION:
XS GIS Cut Line= 4
      2278768.94      13429442.9      2278020.34     13429106.02
      2277171.95     13428868.98      2276654.23     13428987.49
#Sta/Elev= 30
  3551.6   326.8  3579.4  326.31  3596.8  327.19  3618.7  326.26  3700.7   325.5
  3943.1  324.79  4069.8  323.07    4093  323.78    4178  322.21  4593.3  318.29
  4717.6  318.21  4874.9  316.01  4907.6  317.15  4925.5  317.03  4943.3   315.5
  4948.4  316.07  5008.3  313.79  5016.8  316.54  5021.9  316.08  5029.4  317.02
  5050.1  316.49  5090.3  317.38  5095.4  318.55    5102  317.51  5112.4  318.02
  5122.8  315.87  5134.8  315.93  5143.6  317.22  5319.3  319.35  5784.5  330.36
#Mann= 4 ,-1 , 0
  3551.6     .05       0  4907.6      .1       0  4943.3     .07       0
  5029.4      .1       0
Bank Sta=4925.5,5029.4
XS Rating Curve= 0 ,0
Exp/Cntr=0.3,0.1

Type RM Length L Ch R = 1 ,5747    ,826,826,826
BEGIN DESCRIPTION:
UNT038 IN SUCR 11.0
END DESCRIPTION:
XS GIS Cut Line= 3
      2278188.75     13427958.22      2276772.72     13428663.12
       2276511.7     13428973.86
#Sta/Elev= 30
  3836.6  323.65  3849.6  322.46    3956  320.24    4316  316.83  4371.9  316.71
  4463.3  314.75  4476.6  315.64  4493.4  314.48  4517.5  314.76  4580.8  315.54
  4628.9  316.39  4694.9  316.33  4767.6  314.66  4887.5  314.81  4924.4  315.81
  4963.6  315.26  4996.5  312.16  4999.2  311.66  5002.5  312.16  5030.7  313.42
  5053.1  315.51  5071.8   315.8  5149.4  316.54  5267.5  317.92  5534.5  324.71
  5715.4  330.05    5744   329.8  5779.2  331.69  5801.3  331.35  5824.2  332.56
#Mann= 13 ,-1 , 0
  3836.6     .05       0    4316      .1       0  4371.9     .05       0
  4517.5     .12       0  4580.8     .05       0  4628.9     .12       0
  4887.5      .1       0  4996.5     .07       0  5002.5      .1       0
  5071.8     .16       0  5149.4      .1       0  5267.5     .05       0
  5534.5      .1       0
Bank Sta=4963.6,5053.1
XS Rating Curve= 0 ,0
Exp/Cntr=0.3,0.1

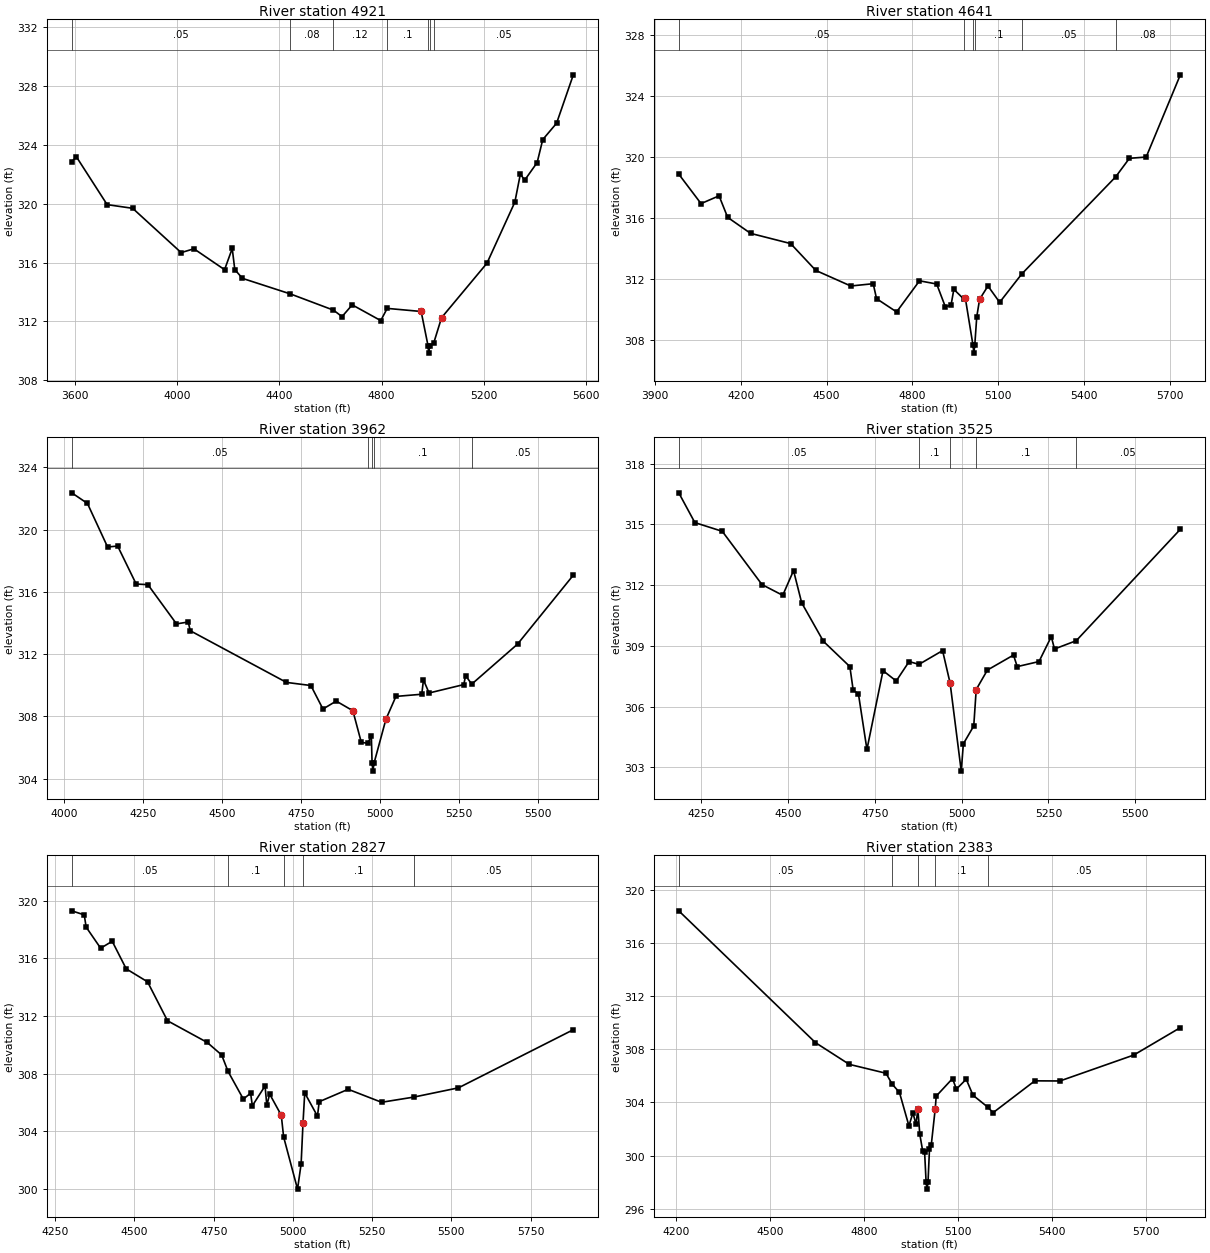
Type RM Length L Ch R = 1 ,4921    ,280,280,280
BEGIN DESCRIPTION:
UNT038 IN SUCR 10.0
END DESCRIPTION:
XS GIS Cut Line= 3
      2278126.36     13427845.93      2276579.34     13427802.26
      2276212.02     13428001.48
#Sta/Elev= 30
  3585.9  322.87  3604.5  323.18  3724.6  319.94  3824.6  319.69  4014.7  316.68
  4064.7  316.94  4184.8  315.52  4214.8  316.96  4224.8  315.53  4254.8  314.93
  4443.1  313.87  4611.6  312.77    4645  312.33    4685  313.13  4796.8  312.06
    4822  312.89  4955.1  312.68  4982.1  310.35  4984.8  309.85  4988.1  310.35
  5004.6  310.55  5035.1  312.26    5213  315.96  5322.3  320.11  5344.1  322.04
  5360.3  321.59  5409.7   322.8  5431.6  324.36  5485.8  325.47  5551.4  328.76
#Mann= 7 ,-1 , 0
  3585.9     .05       0  4443.1     .08       0  4611.6     .12       0
    4822      .1       0  4982.1     .07       0  4988.1      .1       0
  5004.6     .05       0
Bank Sta=4955.1,5035.1
XS Rating Curve= 0 ,0
Exp/Cntr=0.3,0.1

Type RM Length L Ch R = 1 ,4641    ,679,679,679
BEGIN DESCRIPTION:
UNT038 IN SUCR 9.0
END DESCRIPTION:
XS GIS Cut Line= 3
      2277708.46     13427477.88      2276205.05     13427552.74
      2275967.96     13427627.61
#Sta/Elev= 30
  3982.8  318.86  4060.7  316.93  4123.7  317.44  4153.7  316.03  4233.8  314.98
    4374  314.31    4462  312.55  4584.3  311.53  4662.7  311.68  4674.4   310.7
  4744.5  309.83  4824.6  311.87  4884.7  311.66  4914.7  310.18  4934.7  310.26
  4944.7  311.31  4980.8  310.65  4984.8  310.74  5011.8  307.63  5014.6  307.13
  5017.8  307.63  5024.8  309.51  5034.8  310.66    5064  311.53  5104.9  310.46
  5182.3  312.32  5510.4  318.68  5558.7   319.9  5617.2  319.98  5736.7  325.37
#Mann= 6 ,-1 , 0
  3982.8     .05       0  4980.8      .1       0  5011.8     .07       0
  5017.8      .1       0  5182.3     .05       0  5510.4     .08       0
Bank Sta=4984.8,5034.8
XS Rating Curve= 0 ,0
Exp/Cntr=0.3,0.1

Type RM Length L Ch R = 1 ,3962    ,437,437,437
BEGIN DESCRIPTION:
UNT038 IN SUCR 8.0
END DESCRIPTION:
XS GIS Cut Line= 3
      2277564.92     13426698.13      2276336.05     13427097.36
      2276086.53     13427259.55
#Sta/Elev= 30
  4023.2  322.36  4072.9  321.68  4136.8  318.88  4168.7  318.94  4227.4   316.5
  4264.6  316.46  4355.2  313.94  4392.4  314.06  4398.8   313.5  4703.7  310.18
  4781.1  309.98  4819.4  308.47  4861.4  308.98  4914.2  308.36  4940.9  306.33
  4961.1  306.27  4972.8  306.72  4975.1  304.98  4977.8  304.48  4981.1  304.98
  5019.1  307.82  5050.7  309.28  5132.6  309.42  5137.9  310.34  5155.8   309.5
  5265.7  310.04  5271.5  310.61    5291  310.07  5436.1  312.64  5612.9  317.07
#Mann= 5 ,-1 , 0
  4023.2     .05       0  4961.1      .1       0  4975.1     .07       0
  4981.1      .1       0    5291     .05       0
Bank Sta=4914.2,5019.1
XS Rating Curve= 0 ,0
Exp/Cntr=0.3,0.1

Type RM Length L Ch R = 1 ,3525    ,698,698,698
BEGIN DESCRIPTION:
UNT038 IN SUCR 6.0
END DESCRIPTION:
XS GIS Cut Line= 3
      2277215.63     13426355.02      2276123.95     13426779.21
      2275968.69     13427002.79
#Sta/Elev= 30
    4186  316.56  4232.3  315.09  4311.2  314.66  4425.5  312.03  4485.2   311.5
  4516.3  312.72  4539.7  311.13  4602.2  309.23  4678.4  307.98    4688  306.81
    4703  306.64  4727.5  303.89  4773.8  307.78  4811.8  307.27  4848.9  308.23
  4877.2  308.09  4945.2  308.77  4966.9  307.16  4998.9  302.82    5005  304.17
  5034.9  305.05    5042  306.85  5074.2  307.81  5149.3  308.55    5160  307.98
  5222.7  308.23    5258  309.46  5267.3  308.85  5329.9  309.26  5629.4  314.76
#Mann= 5 ,-1 , 0
    4186     .05       0  4877.2      .1       0  4966.9     .07       0
    5042      .1       0  5329.9     .05       0
Bank Sta=4966.9,5042
XS Rating Curve= 0 ,0
Exp/Cntr=0.3,0.1

Type RM Length L Ch R = 1 ,2827    ,444,444,444
BEGIN DESCRIPTION:
UNT038 IN SUCR 5.0
END DESCRIPTION:
XS GIS Cut Line= 3
      2277103.38     13425812.29      2275930.57     13426361.26
      2275843.23     13426635.77
#Sta/Elev= 30
    4302  319.29  4341.4  319.01  4347.5  318.16  4393.2   316.7  4429.7  317.18
  4473.9  315.27  4541.2  314.37  4604.2  311.67  4729.4  310.17  4775.1   309.3
  4795.3  308.16  4843.6  306.24  4866.5  306.65    4872  305.78  4912.1  307.15
  4917.7  305.81  4926.6  306.59  4963.3  305.12  4970.7  303.62  5014.6     300
  5025.9  301.74  5031.8  304.55  5037.3  306.67  5077.5  305.06    5083  306.06
  5174.4  306.92  5279.9  306.02  5381.7  306.38  5522.4  307.02    5885  311.05
#Mann= 5 ,-1 , 0
    4302     .05       0  4795.3      .1       0  4970.7     .07       0
  5031.8      .1       0  5381.7     .05       0
Bank Sta=4963.3,5031.8
XS Rating Curve= 0 ,0
Exp/Cntr=0.3,0.1

Type RM Length L Ch R = 1 ,2383    ,520,520,520
BEGIN DESCRIPTION:
UNT038 IN SUCR 4.0
END DESCRIPTION:
XS GIS Cut Line= 4
      2276947.38      13425581.5      2276473.29     13425681.31
      2275749.67      13426105.5      2275625.69     13426353.46
#Sta/Elev= 30
  4207.9   318.4  4644.2  308.49  4751.9  306.86  4869.2  306.19  4888.9  305.37
  4912.1  304.75  4942.3  302.24  4955.1  303.21    4965  302.35  4970.8   303.5
    4977  301.61  4986.5  300.31  4992.3   300.3  4997.2  297.98    5000  297.48
  5003.2  297.98  5007.9  300.46  5013.7  300.82 5026.38  303.54  5029.4  304.47
  5081.4  305.79  5093.8     305  5125.2  305.74  5146.7  304.54  5193.5  303.65
  5211.1  303.23  5344.1  305.62  5424.2  305.61  5659.9  307.56  5808.4  309.62
#Mann= 5 ,-1 , 0
  4207.9     .05       0  4888.9      .1       0  4970.8     .07       0
 5026.38      .1       0  5193.5     .05       0
Bank Sta=4970.8,5026.38
XS Rating Curve= 0 ,0
Exp/Cntr=0.3,0.1

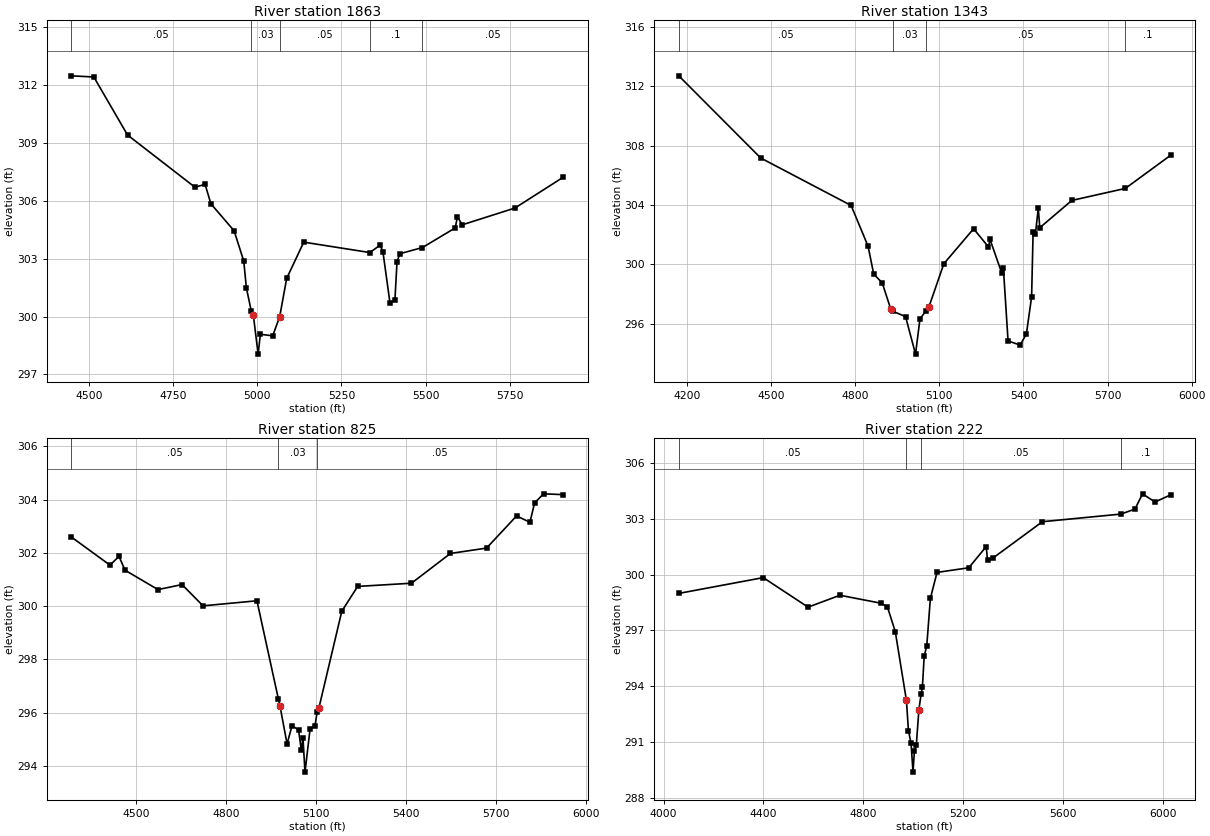
Type RM Length L Ch R = 1 ,1863    ,520,520,520
BEGIN DESCRIPTION:
UNT038 IN SUCR 3.0
END DESCRIPTION:
XS GIS Cut Line= 4
      2276594.72     13425277.16      2276178.03     13425292.79
      2275909.81      13425517.4      2275493.97     13426071.86
#Sta/Elev= 30
    4448  312.49    4515  312.43  4615.1  309.42  4815.3  306.71  4845.3  306.86
  4862.6  305.85  4931.5  304.45  4960.1  302.88  4967.9  301.49  4982.2  300.31
  4988.7  300.06  5002.8  298.05  5009.5  299.08    5046     299  5066.8  299.99
  5087.6  301.98  5138.3  303.86  5334.7  303.32  5365.2  303.71  5373.5  303.34
  5394.4  300.69  5408.9  300.85  5415.2  302.85  5423.5  303.26  5490.6  303.58
  5588.1   304.6  5594.4  305.18  5608.9  304.76  5765.2  305.63  5907.9  307.22
#Mann= 5 ,-1 , 0
    4448     .05       0  4982.2     .03       0  5066.8     .05       0
  5334.7      .1       0  5490.6     .05       0
Bank Sta=4988.7,5066.8
XS Rating Curve= 0 ,0
Exp/Cntr=0.3,0.1

Type RM Length L Ch R = 1 ,1343    ,518,518,518
BEGIN DESCRIPTION:
UNT038 IN SUCR 2.0
END DESCRIPTION:
XS GIS Cut Line= 3
      2276487.76     13424946.85      2275687.72     13425046.85
      2275323.13     13425921.87
#Sta/Elev= 30
  4170.4   312.7  4462.7  307.16  4785.2  303.96  4845.7  301.21  4865.8  299.33
    4896  298.75  4926.3  296.99  4933.8  296.83  4979.4  296.47  5014.9  293.94
  5030.8  296.32  5052.5  296.86  5062.8  297.13  5115.9  300.03    5222  302.39
  5275.1  301.17  5280.5  301.68  5322.8  299.39  5328.2  299.77    5345  294.83
  5388.3  294.55  5410.5  295.31    5429   297.8  5434.4  302.19  5442.5  302.01
  5452.8  303.78  5458.2  302.46  5572.5   304.3  5763.4  305.11  5924.6  307.34
#Mann= 4 ,-1 , 0
  4170.4     .05       0  4933.8     .03       0  5052.5     .05       0
  5763.4      .1       0
Bank Sta=4926.3,5062.8
XS Rating Curve= 0 ,0
Exp/Cntr=0.3,0.1

Type RM Length L Ch R = 1 ,825     ,603,603,603
BEGIN DESCRIPTION:
Mapping XS 8f037862
END DESCRIPTION:
XS GIS Cut Line= 4
      2275896.83     13424558.41      2275365.53     13424558.41
      2275198.87     13424954.24      2275167.62     13425631.34
#Sta/Elev= 30
  4283.8   302.6  4412.9  301.54  4442.9  301.87  4462.9  301.35  4572.9  300.62
  4652.9  300.81  4722.9  300.01  4902.6   300.2  4973.8  296.52  4979.3  296.25
    5003  294.82  5019.6  295.51  5041.3  295.34  5050.5  294.58  5055.9  295.05
  5062.7  293.76  5079.6  295.38  5095.5  295.48  5103.4  296.03  5108.8  296.16
  5185.4  299.81  5238.3  300.74  5417.4  300.86  5547.5  301.98  5667.6  302.18
  5767.8  303.39  5812.2  303.15  5827.8  303.88  5857.8  304.22  5922.4  304.19
#Mann= 3 ,-1 , 0
  4283.8     .05       0  4973.8     .03       0  5103.4     .05       0
Bank Sta=4979.3,5108.8
XS Rating Curve= 0 ,0
Exp/Cntr=0.3,0.1

Type RM Length L Ch R = 1 ,222     ,0,0,0
BEGIN DESCRIPTION:
UNT038 IN SUCR 1.0
END DESCRIPTION:
XS GIS Cut Line= 4
      2275462.75     13424071.87      2274969.91     13424265.26
      2274745.34     13424957.69      2274795.24     13425668.87
#Sta/Elev= 30
  4061.2  298.99  4399.6  299.84  4579.1  298.25  4706.9  298.89  4872.1  298.46
  4897.2  298.26  4928.7  296.93  4973.3  293.23  4981.3  291.61  4991.8  290.92
  4999.7  289.37  5005.2  290.51  5012.8  290.82  5023.3  292.74    5032  293.56
  5037.2  293.93  5044.4   295.6  5054.9  296.18  5069.2  298.72  5095.9  300.12
  5223.1  300.37    5293  301.51  5298.3  300.77  5320.7   300.9  5518.2  302.85
  5832.9  303.26  5889.1  303.53  5919.2  304.35  5969.3  303.91  6031.5  304.29
#Mann= 4 ,-1 , 0
  4061.2     .05       0  4973.3     .03       0    5032     .05       0
  5832.9      .1       0
Bank Sta=4973.3,5023.3
XS Rating Curve= 0 ,0
Exp/Cntr=0.3,0.1

Chan Stop Cuts=-1
Use User Specified Reach Order=0
Composite Channel Slope=5