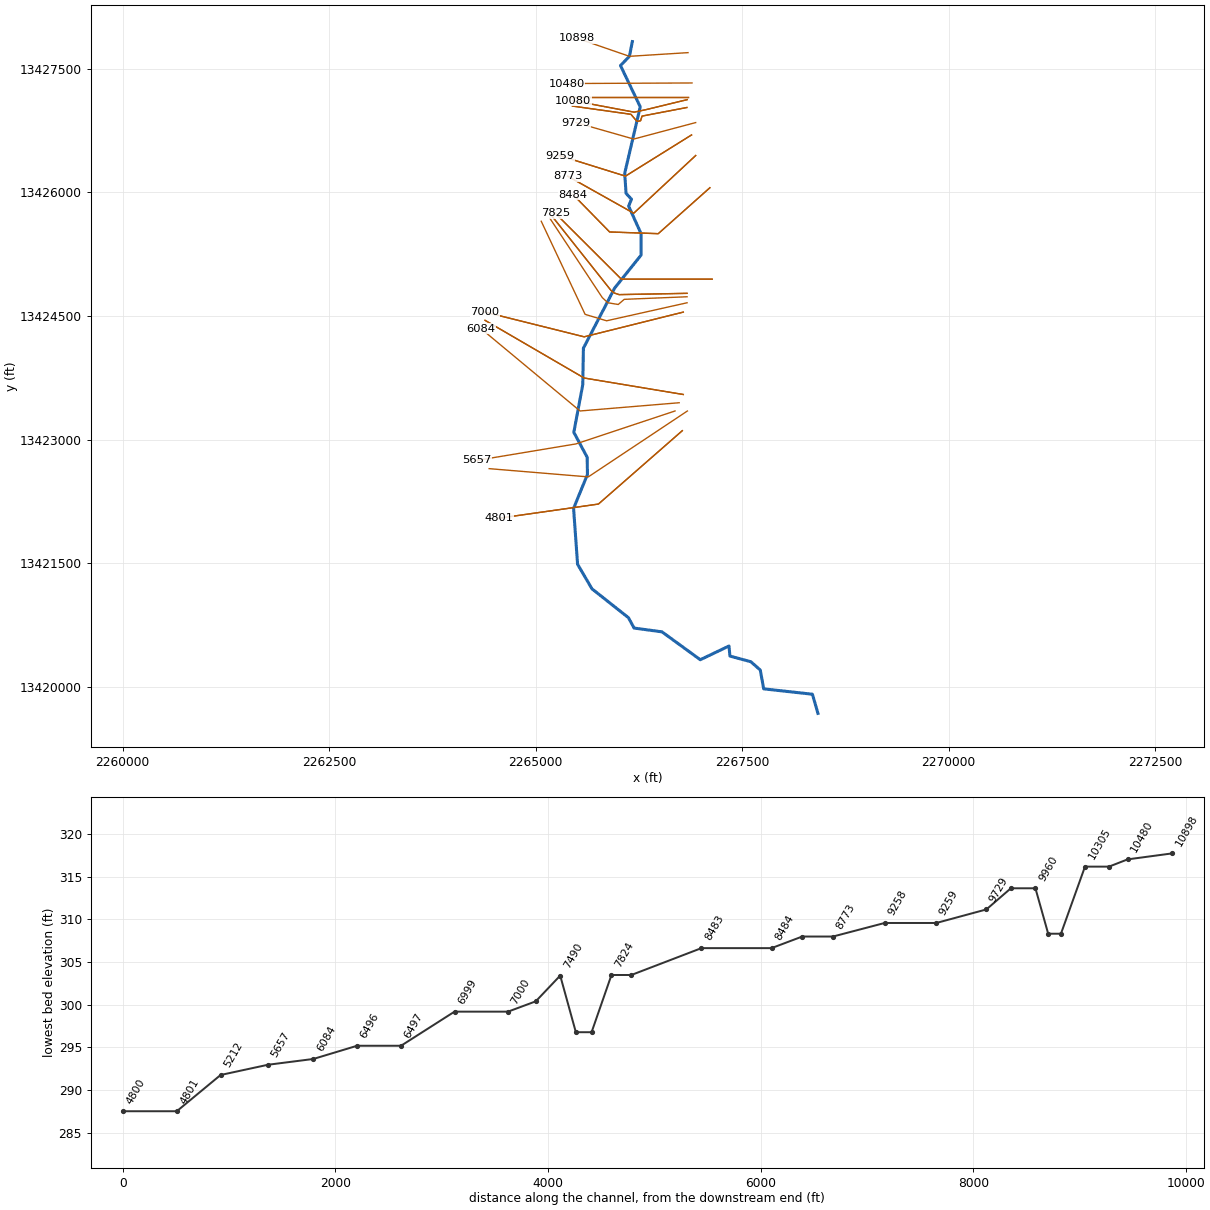
--- UNT039 IN SUCR.prj (project) ---

Proj Title=UNT039 IN SUCR Base Level Engineering
Current Plan=p01
Default Exp/Contr=0.3,0.1
English Units
Geom File=g01
Flow File=f01
Plan File=p01
Y Axis Title=Elevation
X Axis Title(PF)=Main Channel Distance
X Axis Title(XS)=Station
BEGIN DESCRIPTION:
UNT039 IN SUCR
END DESCRIPTION:
DSS Export Rating Curves= 0
DSS Export Rating Curve Sorted= 0
DSS Export Volume Flow Curves= 0
DXF OffsetX= 0
DXF OffsetY= 0
DXF ScaleX= 1
DXF ScaleY= 10

--- UNT039 IN SUCR.p01 (plan) ---

Plan Title=Multiple Run
Short Identifier=Multiple
Geom File=g01
Flow File=f01
Subcritical Flow
K Sum by GR= 0
Std Step Tol= 0.01
Critical Tol= 0.01
Num of Std Step Trials= 20
Max Error Tol= 0.3
Flow Tol Ratio= 0.001
Split Flow NTrial= 30
Split Flow Tol= 0.02
Split Flow Ratio= 0.02
Log Output Level= 0
Friction Slope Method= 1
Unsteady Friction Slope Method= 2
Unsteady Bridges Friction Slope Method= 1
Parabolic Critical Depth
Global Vel Dist=  1 , 1 , 1
Global Log Level= 0
CheckData=True
Encroach Param= -1, 0, 0, 0
BEGIN DESCRIPTION:
Multiple Run
END DESCRIPTION:

--- UNT039 IN SUCR.f01 (steady flow) ---

Flow Title=Multiple
Program Version=4.10
Number of Profiles= 7
Profile Names=10-year,25-year,50-year,1pct_min,100-year,1pct_plu,500-year
River Rch & RM=UNT039 IN SUCR,Reach-1         ,10898
     181     245     296     263     356     481     523
River Rch & RM=UNT039 IN SUCR,Reach-1         ,10480
     233     319     389     349     471     638     704
River Rch & RM=UNT039 IN SUCR,Reach-1         ,6999
     436     615     767     702     949    1283    1475
River Rch & RM=UNT039 IN SUCR,Reach-1         ,6084
     436     615     767     702     949    1283    1475
River Rch & RM=UNT039 IN SUCR,Reach-1         ,945
     458     648     809     740    1001    1354    1559
Boundary for River Rch & Prof#=UNT039 IN SUCR,Reach-1         , 1
Up Type= 0
Dn Type= 3
Dn Slope=0.0032
Boundary for River Rch & Prof#=UNT039 IN SUCR,Reach-1         , 2
Up Type= 0
Dn Type= 3
Dn Slope=0.0032
Boundary for River Rch & Prof#=UNT039 IN SUCR,Reach-1         , 3
Up Type= 0
Dn Type= 3
Dn Slope=0.0032
Boundary for River Rch & Prof#=UNT039 IN SUCR,Reach-1         , 4
Up Type= 0
Dn Type= 3
Dn Slope=0.0032
Boundary for River Rch & Prof#=UNT039 IN SUCR,Reach-1         , 5
Up Type= 0
Dn Type= 3
Dn Slope=0.0032
Boundary for River Rch & Prof#=UNT039 IN SUCR,Reach-1         , 6
Up Type= 0
Dn Type= 3
Dn Slope=0.0032
Boundary for River Rch & Prof#=UNT039 IN SUCR,Reach-1         , 7
Up Type= 0
Dn Type= 3
Dn Slope=0.0032
DSS Import GetInterval= 0
DSS Import GetPeak= 0
DSS Import FillOption= 0

--- UNT039 IN SUCR.g01 (geometry) ---

Geom Title=Existing Conditions
Program Version=4.10

River Reach=UNT039 IN SUCR  ,Reach-1
Reach XY= 30
      2266170.74      13427829.4      2266135.58     13427651.02
      2266027.51     13427539.04      2266266.64     13427037.82
      2266078.59     13426232.14       2266094.6     13425987.89
      2266160.53     13425917.03      2266125.98     13425832.96
      2266275.75     13425501.04      2266276.78      13425238.4
      2265957.38     13424839.25      2265578.52     13424108.77
      2265570.79      13423666.6      2265462.38     13423087.43
      2265624.15     13422785.38      2265627.51     13422576.51
      2265459.42     13422164.28      2265507.72     13421486.86
       2265682.1     13421188.53      2266123.51     13420838.27
      2266192.52     13420711.97      2266529.76      13420666.4
      2266993.58     13420327.97      2267340.62     13420494.21
      2267352.69     13420372.26       2267606.3     13420303.27
       2267719.7     13420202.75      2267761.15     13419974.43
      2268350.97      13419909.3      2268417.72     13419676.86

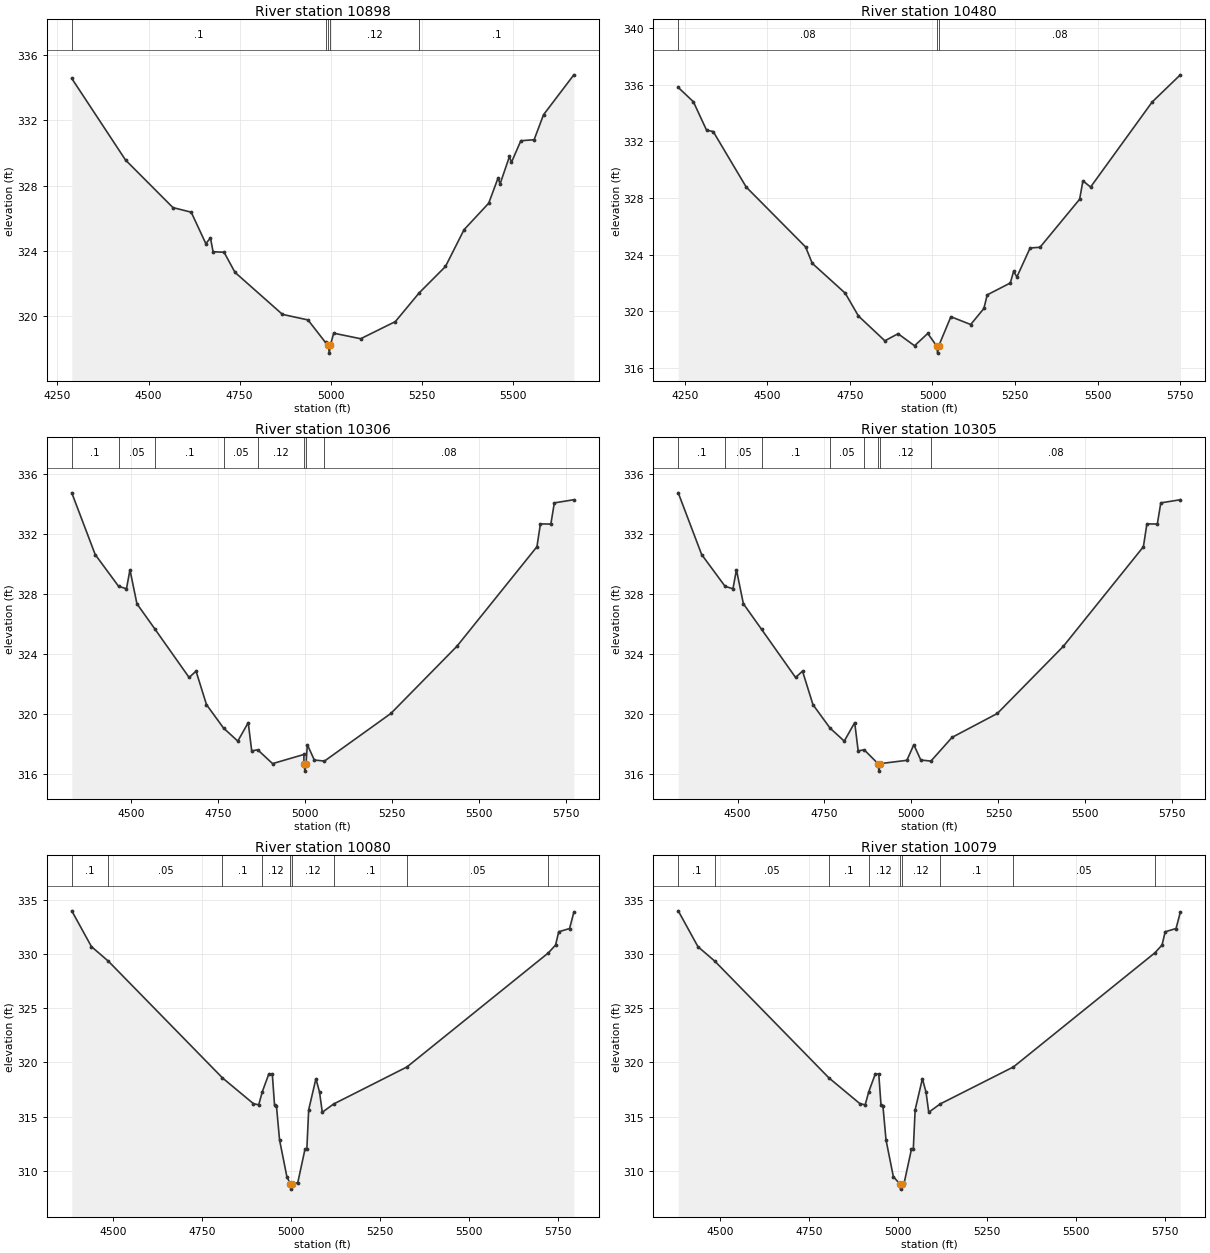
Type RM Length L Ch R = 1 ,10898   ,418,418,418
BEGIN DESCRIPTION:
UNT039 IN SUCR 21.0
END DESCRIPTION:
XS GIS Cut Line= 3
      2266844.98     13427695.61      2266135.58     13427651.02
      2265504.65     13427869.23
#Sta/Elev= 30
  4289.2  334.55  4436.8  329.56    4567  326.65  4617.1  326.37  4657.2  324.45
    4670  324.79  4677.2  323.95  4707.3  323.92  4737.3  322.69  4867.6  320.12
  4937.7  319.78  4985.9   318.4  4993.4  318.25  4996.2  317.75  4999.4  318.25
  5008.3  318.97  5082.4  318.63  5177.6  319.68  5242.8  321.43  5315.2  323.05
  5366.2   325.3  5433.9  326.92  5459.7  328.47    5465  328.09  5490.9  329.78
  5496.2  329.41  5522.1  330.74  5558.5   330.8  5584.4  332.33  5667.6  334.77
#Mann= 5 ,-1 , 0
  4289.2      .1       0  4985.9     .12       0  4993.4     .07       0
  4999.4     .12       0  5242.8      .1       0
Bank Sta=4993.4,4999.4
XS Rating Curve= 0 ,0
Exp/Cntr=0.3,0.1

Type RM Length L Ch R = 1 ,10480   ,175,175,175
BEGIN DESCRIPTION:
Mapping XS 4de7cd6d
END DESCRIPTION:
XS GIS Cut Line= 2
      2266893.61     13427327.55      2265372.73     13427320.61
#Sta/Elev= 30
  4229.8   335.8  4275.7  334.79  4315.7  332.78  4335.7  332.69  4435.7  328.77
  4615.7  324.54  4635.7  323.39  4735.7  321.28  4775.7  319.67  4855.7  317.92
  4895.7  318.42  4945.7  317.57  4985.7  318.44  5012.7  317.55  5015.4  317.05
  5018.7  317.55  5055.7  319.62  5115.7  319.07  5155.7   320.2  5165.7  321.16
  5235.7     322  5245.7  322.82  5255.7  322.43  5295.7  324.47  5325.7  324.52
  5445.7  327.91  5455.7  329.21  5478.9  328.77  5665.7  334.78  5750.7  336.69
#Mann= 3 ,-1 , 0
  4229.8     .08       0  5012.7     .07       0  5018.7     .08       0
Bank Sta=5012.7,5018.7
XS Rating Curve= 0 ,0
Exp/Cntr=0.3,0.1

Type RM Length L Ch R = 1 ,10306   ,226,226,226
BEGIN DESCRIPTION:
Mapping XS f635e993
END DESCRIPTION:
XS GIS Cut Line= 2
      2266845.01     13427160.88      2265401.61     13427160.88
#Sta/Elev= 30
  4329.6  334.74  4396.9  330.63  4464.3  328.51  4486.9  328.35  4496.9  329.61
  4516.9  327.35  4569.4  325.64  4666.9  322.44  4686.9  322.86  4716.9  320.63
  4765.9  319.07  4806.9   318.2  4836.9  319.43  4846.9  317.55  4864.2  317.62
  4906.9   316.7  4996.9  317.31    4997   316.7  4999.8   316.2    5003   316.7
  5006.9  317.96  5026.9  316.94  5056.1  316.87  5246.9  320.04  5436.9  324.52
  5666.9  331.15  5676.9  332.67  5706.9  332.66  5716.9  334.07    5773  334.28
#Mann= 8 ,-1 , 0
  4329.6      .1       0  4464.3     .05       0  4569.4      .1       0
  4765.9     .05       0  4864.2     .12       0    4997     .07       0
    5003     .12       0  5056.1     .08       0
Bank Sta=4997,5003
XS Rating Curve= 0 ,0
Exp/Cntr=0.3,0.1

Type RM Length L Ch R = 1 ,10305   ,226,226,226
BEGIN DESCRIPTION:
Mapping XS f635e993
END DESCRIPTION:
XS GIS Cut Line= 2
      2266845.01     13427160.88      2265401.61     13427160.88
#Sta/Elev= 30
  4329.6  334.74  4396.9  330.63  4464.3  328.51  4486.9  328.35  4496.9  329.61
  4516.9  327.35  4569.4  325.64  4666.9  322.44  4686.9  322.86  4716.9  320.63
  4765.9  319.07  4806.9   318.2  4836.9  319.43  4846.9  317.55  4864.2  317.62
  4903.9   316.7  4906.6   316.2  4909.9   316.7  4986.9  316.92  5006.9  317.96
  5026.9  316.94  5056.1  316.87  5116.9  318.45  5246.9  320.04  5436.9  324.52
  5666.9  331.15  5676.9  332.67  5706.9  332.66  5716.9  334.07    5773  334.28
#Mann= 8 ,-1 , 0
  4329.6      .1       0  4464.3     .05       0  4569.4      .1       0
  4765.9     .05       0  4864.2     .12       0  4903.9     .07       0
  4909.9     .12       0  5056.1     .08       0
Bank Sta=4903.9,4909.9
XS Rating Curve= 0 ,0
Exp/Cntr=0.3,0.1

Type RM Length L Ch R = 1 ,10080   ,120,120,120
BEGIN DESCRIPTION:
UNT039 IN SUCR 20.0
END DESCRIPTION:
XS GIS Cut Line= 4
      2266835.14     13427125.25      2266336.02     13427003.72
      2266192.79     13426973.34      2265455.95     13427112.04
#Sta/Elev= 30
  4383.6  333.97  4438.9  330.67  4486.4  329.33  4806.7  318.58  4893.9   316.2
  4908.6   316.1  4918.6   317.3  4936.5   318.9  4946.7  318.95  4953.1  316.04
  4958.3  316.02  4967.1  312.86  4987.6  309.49    4997  308.83  4999.8  308.33
    5003  308.83  5018.2  308.92  5038.6  312.02  5043.7  312.02  5048.9  315.64
  5069.2   318.5  5079.4  317.27  5087.1  315.41  5118.8  316.17    5325  319.59
  5722.1   330.1  5742.2  330.82    5751  332.04  5781.5  332.34  5793.5  333.84
#Mann= 9 ,-1 , 0
  4383.6      .1       0  4486.4     .05       0  4806.7      .1       0
  4918.6     .12       0    4997     .07       0    5003     .12       0
  5118.8      .1       0    5325     .05       0  5722.1     .08       0
Bank Sta=4997,5003
XS Rating Curve= 0 ,0
Exp/Cntr=0.3,0.1

Type RM Length L Ch R = 1 ,10079   ,120,120,120
BEGIN DESCRIPTION:
UNT039 IN SUCR 20.0
END DESCRIPTION:
XS GIS Cut Line= 4
      2266835.14     13427125.25      2266336.02     13427003.72
      2266192.79     13426973.34      2265455.95     13427112.04
#Sta/Elev= 30
  4383.6  333.97  4438.9  330.67  4486.4  329.33  4806.7  318.58  4893.9   316.2
  4908.6   316.1  4918.6   317.3  4936.5   318.9  4946.7  318.95  4953.1  316.04
  4958.3  316.02  4967.1  312.86  4987.6  309.49    5005  308.83  5007.8  308.33
    5011  308.83  5018.2  308.92  5038.6  312.02  5043.7  312.02  5048.9  315.64
  5069.2   318.5  5079.4  317.27  5087.1  315.41  5118.8  316.17    5325  319.59
  5722.1   330.1  5742.2  330.82    5751  332.04  5781.5  332.34  5793.5  333.84
#Mann= 9 ,-1 , 0
  4383.6      .1       0  4486.4     .05       0  4806.7      .1       0
  4918.6     .12       0    5005     .07       0    5011     .12       0
  5118.8      .1       0    5325     .05       0  5722.1     .08       0
Bank Sta=5005,5011
XS Rating Curve= 0 ,0
Exp/Cntr=0.3,0.1

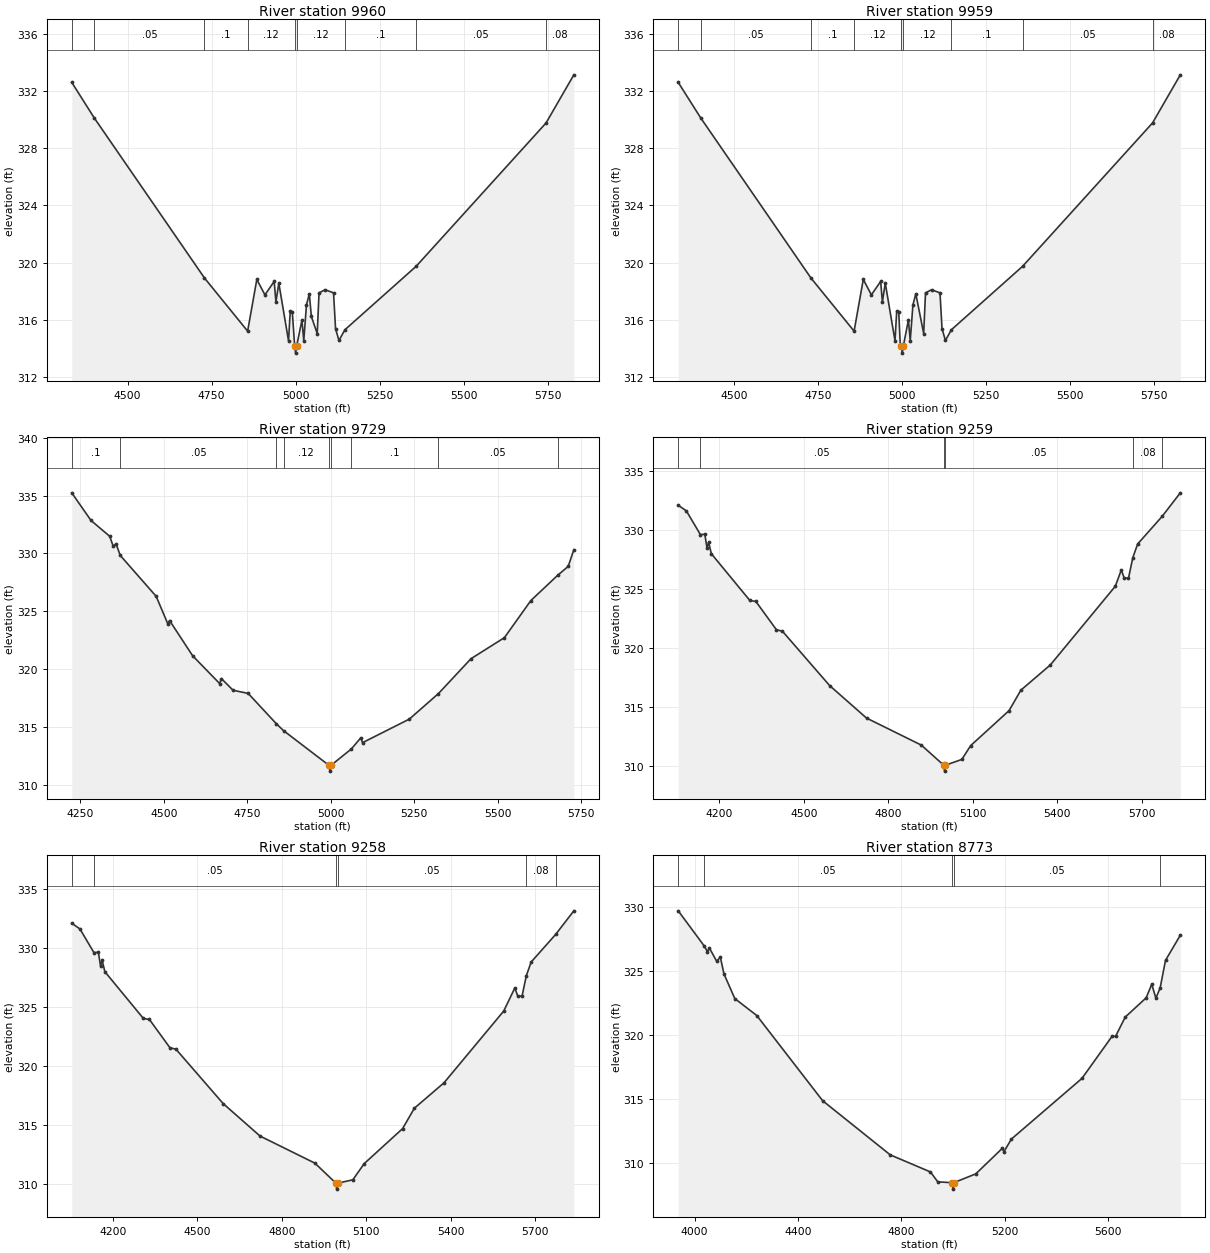
Type RM Length L Ch R = 1 ,9960    ,231,231,231
BEGIN DESCRIPTION:
Mapping XS 7504cd12
END DESCRIPTION:
XS GIS Cut Line= 6
       2266830.8     13427029.76      2266288.28      13426925.6
      2266270.92     13426869.17      2266227.51     13426860.49
      2266153.73      13426947.3      2265446.21     13427047.13
#Sta/Elev= 30
  4334.3  332.62  4400.9  330.14  4728.9  318.92  4857.2   315.2  4884.5  318.82
  4908.6  317.74  4936.1  318.68  4941.3  317.25  4949.9  318.56  4978.8  314.52
  4983.9   316.6    4990  316.53    4997  314.16  4999.8  313.66    5003  314.16
  5018.7  315.98  5024.1  314.53  5032.1  317.04  5040.7  317.81  5046.6  316.23
  5064.1  315.03  5069.5  317.88  5087.5   318.1  5112.6  317.88  5118.6  315.37
  5128.7  314.55  5146.6   315.3  5358.2  319.74  5744.5  329.78  5827.1  333.15
#Mann= 9 ,-1 , 0
  4334.3      .1       0  4400.9     .05       0  4728.9      .1       0
  4857.2     .12       0    4997     .07       0    5003     .12       0
  5146.6      .1       0  5358.2     .05       0  5744.5     .08       0
Bank Sta=4997,5003
XS Rating Curve= 0 ,0
Exp/Cntr=0.3,0.1

Type RM Length L Ch R = 1 ,9959    ,230,230,230
BEGIN DESCRIPTION:
Mapping XS 7504cd12
END DESCRIPTION:
XS GIS Cut Line= 6
       2266830.8     13427029.76      2266288.28      13426925.6
      2266270.92     13426869.17      2266227.51     13426860.49
      2266153.73      13426947.3      2265446.21     13427047.13
#Sta/Elev= 30
  4334.3  332.62  4400.9  330.14  4728.9  318.92  4857.2   315.2  4884.5  318.82
  4908.6  317.74  4936.1  318.68  4941.3  317.25  4949.9  318.56  4978.8  314.52
  4983.9   316.6    4990  316.53  4994.4  314.26  4997.6  314.16  5000.3  313.66
  5003.6  314.16  5018.7  315.98  5024.1  314.53  5032.1  317.04  5040.7  317.81
  5064.1  315.03  5069.5  317.88  5087.5   318.1  5112.6  317.88  5118.6  315.37
  5128.7  314.55  5146.6   315.3  5358.2  319.74  5744.5  329.78  5827.1  333.15
#Mann= 9 ,-1 , 0
  4334.3      .1       0  4400.9     .05       0  4728.9      .1       0
  4857.2     .12       0  4997.6     .07       0  5003.6     .12       0
  5146.6      .1       0  5358.2     .05       0  5744.5     .08       0
Bank Sta=4997.6,5003.6
XS Rating Curve= 0 ,0
Exp/Cntr=0.3,0.1

Type RM Length L Ch R = 1 ,9729    ,471,471,471
BEGIN DESCRIPTION:
UNT039 IN SUCR 19.0
END DESCRIPTION:
XS GIS Cut Line= 3
      2266937.72     13426846.85      2266187.72     13426646.85
      2265487.74     13426846.85
#Sta/Elev= 30
  4224.5  335.24  4282.1  332.85  4338.3  331.48  4348.7  330.61  4357.1  330.84
  4369.7  329.83  4477.4  326.29  4512.3  323.91  4517.5   324.2  4586.7  321.15
  4667.6  318.75  4672.8  319.18  4707.7  318.17    4753   317.9  4837.6  315.27
    4859  314.68  4995.1  311.68  4997.9  311.18  5001.1  311.68  5062.2   313.1
  5090.4  314.06  5095.6  313.64    5236  315.68  5323.2  317.89  5420.6   320.9
  5520.7  322.72    5600  325.93  5680.6  328.12  5711.8  328.88  5728.7  330.32
#Mann= 9 ,-1 , 0
  4224.5      .1       0  4369.7     .05       0  4837.6      .1       0
    4859     .12       0  4995.1     .07       0  5001.1     .12       0
  5062.2      .1       0  5323.2     .05       0  5680.6     .08       0
Bank Sta=4995.1,5001.1
XS Rating Curve= 0 ,0
Exp/Cntr=0.3,0.1

Type RM Length L Ch R = 1 ,9259    ,486,486,486
BEGIN DESCRIPTION:
UNT039 IN SUCR 18.0
END DESCRIPTION:
XS GIS Cut Line= 3
      2266887.75     13426696.88      2266087.72     13426196.85
      2265287.71     13426446.86
#Sta/Elev= 30
  4054.8  332.09  4083.7  331.61  4133.3  329.61  4149.2  329.63  4156.8  328.48
  4162.7  328.95  4172.2  327.99    4309  324.03  4330.2  323.95  4403.3  321.55
  4424.5  321.43    4592  316.83  4722.9  314.08  4917.5  311.79    4997  310.09
  4999.8  309.59    5003  310.09  5061.1  310.58  5092.5  311.75  5228.7  314.71
  5270.6  316.44  5375.4  318.58  5605.9  325.24  5626.9  326.61  5637.3  325.94
  5652.5  325.91  5667.8  327.65    5685  328.81  5771.7  331.14  5836.4  333.14
#Mann= 6 ,-1 , 0
  4054.8      .1       0  4133.3     .05       0    4997    .035       0
    5003     .05       0  5667.8     .08       0  5771.7      .1       0
Bank Sta=4997,5003
XS Rating Curve= 0 ,0
Exp/Cntr=0.3,0.1

Type RM Length L Ch R = 1 ,9258    ,486,486,486
BEGIN DESCRIPTION:
UNT039 IN SUCR 18.0
END DESCRIPTION:
XS GIS Cut Line= 3
      2266887.75     13426696.88      2266087.72     13426196.85
      2265287.71     13426446.86
#Sta/Elev= 30
  4054.8  332.09  4083.7  331.61  4133.3  329.61  4149.2  329.63  4156.8  328.48
  4162.7  328.95  4172.2  327.99    4309  324.03  4330.2  323.95  4403.3  321.55
  4424.5  321.43    4592  316.83  4722.9  314.08  4917.5  311.79  4992.3  310.09
    4995  309.59  4998.3  310.09  5052.2  310.38  5092.5  311.75  5228.7  314.71
  5270.6  316.44  5375.4  318.58  5587.6  324.66  5626.9  326.61  5637.3  325.94
  5652.5  325.91  5667.8  327.65    5685  328.81  5771.7  331.14  5836.4  333.14
#Mann= 6 ,-1 , 0
  4054.8      .1       0  4133.3     .05       0  4992.3    .035       0
  4998.3     .05       0  5667.8     .08       0  5771.7      .1       0
Bank Sta=4992.3,4998.3
XS Rating Curve= 0 ,0
Exp/Cntr=0.3,0.1

Type RM Length L Ch R = 1 ,8773    ,289,289,289
BEGIN DESCRIPTION:
UNT039 IN SUCR 17.0
END DESCRIPTION:
XS GIS Cut Line= 3
      2266937.74     13426446.87      2266187.72     13425746.85
      2265387.74     13426196.85
#Sta/Elev= 30
  3936.4  329.69  4037.4  326.94  4049.5   326.5  4056.8   326.8  4085.2  325.76
  4099.4  326.08  4113.5  324.77  4155.5  322.85  4240.5  321.53  4495.5  314.89
  4757.2  310.67  4912.8  309.34  4941.1  308.57    4997   308.5  4999.8     308
    5003   308.5  5088.5  309.19  5191.5  311.19  5197.2  310.91  5226.2   311.9
  5499.4  316.63  5616.3  319.92  5629.4   319.9    5667  321.41    5748  322.91
  5769.6  323.97  5785.6  322.88  5802.2  323.69  5822.9  325.83  5880.2  327.79
#Mann= 5 ,-1 , 0
  3936.4      .1       0  4037.4     .05       0    4997    .035       0
    5003     .05       0  5802.2     .08       0
Bank Sta=4997,5003
XS Rating Curve= 0 ,0
Exp/Cntr=0.3,0.1

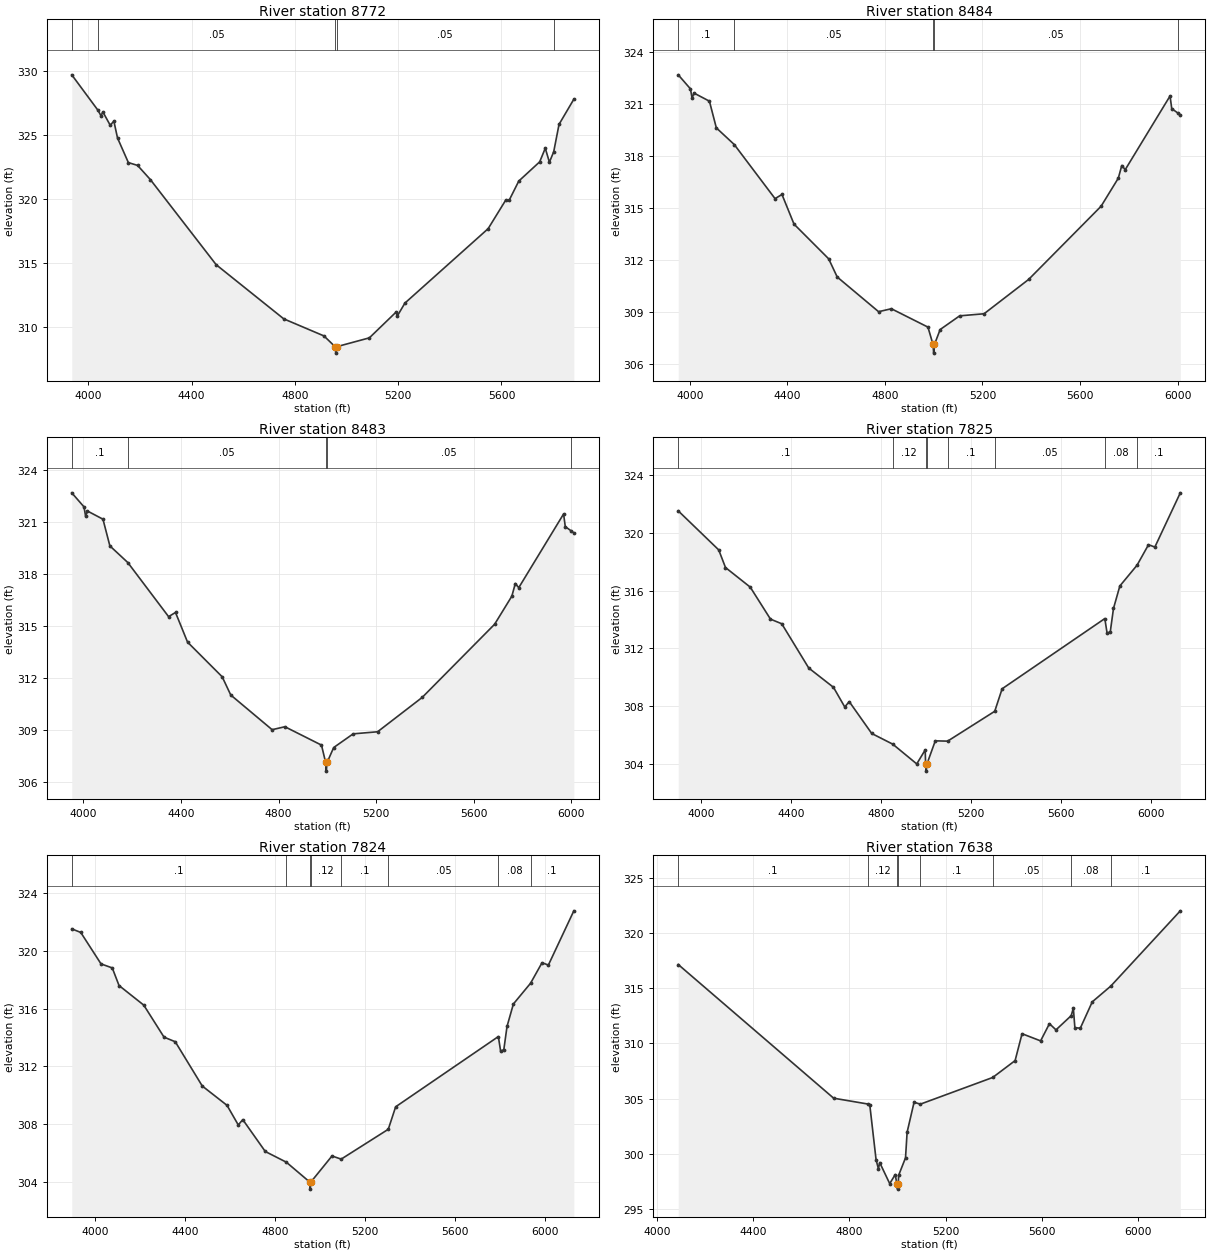
Type RM Length L Ch R = 1 ,8772    ,289,289,289
BEGIN DESCRIPTION:
UNT039 IN SUCR 17.0
END DESCRIPTION:
XS GIS Cut Line= 3
      2266937.74     13426446.87      2266187.72     13425746.85
      2265387.74     13426196.85
#Sta/Elev= 30
  3936.4  329.69  4037.4  326.94  4049.5   326.5  4056.8   326.8  4085.2  325.76
  4099.4  326.08  4113.5  324.77  4155.5  322.85  4191.2  322.63  4240.5  321.53
  4495.5  314.89  4757.2  310.67  4912.8  309.34  4955.9   308.5  4958.7     308
  4961.9   308.5  5088.5  309.19  5191.5  311.19  5197.2  310.91  5226.2   311.9
  5548.4   317.7  5616.3  319.92  5629.4   319.9    5667  321.41    5748  322.91
  5769.6  323.97  5785.6  322.88  5802.2  323.69  5822.9  325.83  5880.2  327.79
#Mann= 5 ,-1 , 0
  3936.4      .1       0  4037.4     .05       0  4955.9    .035       0
  4961.9     .05       0  5802.2     .08       0
Bank Sta=4955.9,4961.9
XS Rating Curve= 0 ,0
Exp/Cntr=0.3,0.1

Type RM Length L Ch R = 1 ,8484    ,659,659,659
BEGIN DESCRIPTION:
UNT039 IN SUCR 16.0
END DESCRIPTION:
XS GIS Cut Line= 4
      2267109.48     13426055.83      2266484.46     13425498.52
      2265895.92     13425519.35      2265453.49     13425972.18
#Sta/Elev= 30
    3952  322.69  4002.1  321.88  4008.8  321.34  4016.4  321.64  4079.9  321.17
  4108.3  319.63  4181.8  318.67  4349.1  315.55  4377.5  315.79  4426.9  314.08
    4569  312.08  4604.1  311.03  4773.8  309.03  4826.2   309.2  4976.3  308.14
    4997  307.14  4999.8  306.64    5003  307.14  5026.3     308  5106.3  308.79
  5206.4  308.91  5389.3  310.89  5686.4  315.11  5757.1  316.73  5771.3  317.46
  5785.4  317.22  5969.3  321.47  5976.3  320.74    6000   320.5  6011.4  320.38
#Mann= 5 ,-1 , 0
    3952      .1       0  4181.8     .05       0    4997     .03       0
    5003     .05       0    6000     .08       0
Bank Sta=4997,5003
XS Rating Curve= 0 ,0
Exp/Cntr=0.3,0.1

Type RM Length L Ch R = 1 ,8483    ,659,659,659
BEGIN DESCRIPTION:
UNT039 IN SUCR 16.0
END DESCRIPTION:
XS GIS Cut Line= 4
      2267109.48     13426055.83      2266484.46     13425498.52
      2265895.92     13425519.35      2265453.49     13425972.18
#Sta/Elev= 30
    3952  322.69  4002.1  321.88  4008.8  321.34  4016.4  321.64  4079.9  321.17
  4108.3  319.63  4181.8  318.67  4349.1  315.55  4377.5  315.79  4426.9  314.08
    4569  312.08  4604.1  311.03  4773.8  309.03  4826.2   309.2  4976.3  308.14
  4993.3  307.14    4996  306.64  4999.3  307.14  5026.3     308  5106.3  308.79
  5206.4  308.91  5389.3  310.89  5686.4  315.11  5757.1  316.73  5771.3  317.46
  5785.4  317.22  5969.3  321.47  5976.3  320.74    6000   320.5  6011.4  320.38
#Mann= 5 ,-1 , 0
    3952      .1       0  4181.8     .05       0  4993.3     .03       0
  4999.3     .05       0    6000     .08       0
Bank Sta=4993.3,4999.3
XS Rating Curve= 0 ,0
Exp/Cntr=0.3,0.1

Type RM Length L Ch R = 1 ,7825    ,187,187,187
BEGIN DESCRIPTION:
UNT039 IN SUCR 15.0
END DESCRIPTION:
XS GIS Cut Line= 3
      2267137.68     13424946.85      2266037.72     13424946.85
      2265237.74     13425746.84
#Sta/Elev= 30
  3897.6  321.54  4077.6  318.83  4107.6  317.61  4217.6  316.25  4307.6  314.03
  4357.6  313.71  4477.6  310.64  4587.6   309.3  4637.6  307.94  4657.6  308.31
  4757.6   306.1    4851  305.36  4957.6  303.99  4995.1  304.96    4997  303.99
  4999.8  303.49    5003  303.99    5040  305.59  5094.9  305.57  5304.2  307.64
    5337   309.2  5793.4  314.07  5803.7  313.04  5817.8  313.17  5831.9  314.77
  5860.2  316.33  5936.6  317.77  5987.5  319.19  6015.8  319.03  6128.9  322.79
#Mann= 8 ,-1 , 0
  3897.6      .1       0    4851     .12       0    4997     .07       0
    5003     .12       0  5094.9      .1       0  5304.2     .05       0
  5793.4     .08       0  5936.6      .1       0
Bank Sta=4997,5003
XS Rating Curve= 0 ,0
Exp/Cntr=0.3,0.1

Type RM Length L Ch R = 1 ,7824    ,187,187,187
BEGIN DESCRIPTION:
UNT039 IN SUCR 15.0
END DESCRIPTION:
XS GIS Cut Line= 3
      2267137.68     13424946.85      2266037.72     13424946.85
      2265237.74     13425746.84
#Sta/Elev= 30
  3897.6  321.54  3937.6  321.29  4027.6  319.11  4077.6  318.83  4107.6  317.61
  4217.6  316.25  4307.6  314.03  4357.6  313.71  4477.6  310.64  4587.6   309.3
  4637.6  307.94  4657.6  308.31  4757.6   306.1    4851  305.36  4954.6  303.99
  4957.3  303.49  4960.6  303.99  5054.1  305.79  5094.9  305.57  5304.2  307.64
    5337   309.2  5793.4  314.07  5803.7  313.04  5817.8  313.17  5831.9  314.77
  5860.2  316.33  5936.6  317.77  5987.5  319.19  6015.8  319.03  6128.9  322.79
#Mann= 8 ,-1 , 0
  3897.6      .1       0    4851     .12       0  4954.6     .07       0
  4960.6     .12       0  5094.9      .1       0  5304.2     .05       0
  5793.4     .08       0  5936.6      .1       0
Bank Sta=4954.6,4960.6
XS Rating Curve= 0 ,0
Exp/Cntr=0.3,0.1

Type RM Length L Ch R = 1 ,7638    ,148,148,148
BEGIN DESCRIPTION:
Mapping XS 7f125d01
END DESCRIPTION:
XS GIS Cut Line= 5
      2266833.42     13424774.56       2266010.5     13424758.93
        2265948.     13424779.77      2265911.54     13424811.02
      2265198.08     13425711.96
#Sta/Elev= 30
  4088.7  317.16  4734.5  305.03    4877   304.5  4884.5  304.44  4910.7  299.46
  4920.5  298.61  4925.8  299.19  4967.4  297.28  4990.4   298.1    4997  297.28
  4999.8  296.78    5003  297.28  5004.4  298.03  5033.1  299.62  5039.7  301.94
  5068.6  304.66  5094.8  304.49  5395.4  306.91  5488.4  308.44  5517.3  310.88
  5594.4  310.23  5631.1  311.79  5658.3  311.23  5721.6  312.52  5730.4   313.2
  5736.8  311.43  5759.3  311.38    5809  313.77    5886   315.2  6174.9  322.03
#Mann= 8 ,-1 , 0
  4088.7      .1       0    4877     .12       0    4997     .07       0
    5003     .12       0  5094.8      .1       0  5395.4     .05       0
  5721.6     .08       0    5886      .1       0
Bank Sta=4997,5003
XS Rating Curve= 0 ,0
Exp/Cntr=0.3,0.1

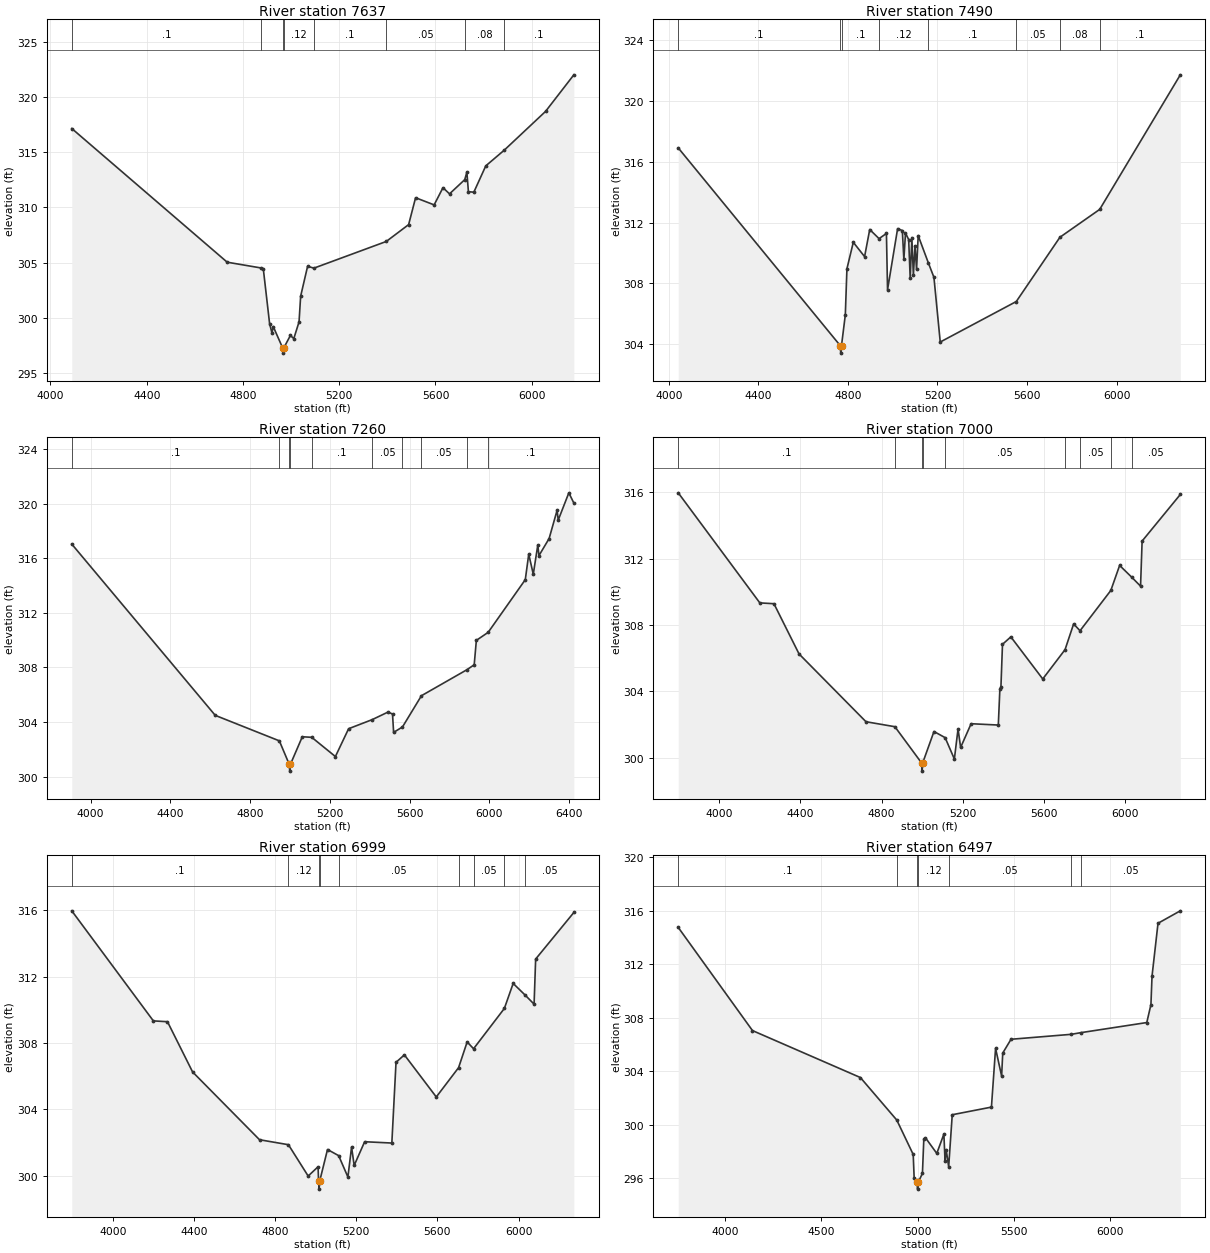
Type RM Length L Ch R = 1 ,7637    ,147,147,147
BEGIN DESCRIPTION:
Mapping XS 7f125d01
END DESCRIPTION:
XS GIS Cut Line= 5
      2266833.42     13424774.56       2266010.5     13424758.93
        2265948.     13424779.77      2265911.54     13424811.02
      2265198.08     13425711.96
#Sta/Elev= 30
  4088.7  317.16  4734.5  305.03    4877   304.5  4884.5  304.44  4910.7  299.46
  4920.5  298.61  4925.8  299.19  4964.4  297.28  4967.2  296.78  4970.4  297.28
    4997  298.38  5011.3   298.1  5033.1  299.62  5039.7  301.94  5068.6  304.66
  5094.8  304.49  5395.4  306.91  5488.4  308.44  5517.3  310.88  5594.4  310.23
  5631.1  311.79  5658.3  311.23  5721.6  312.52  5730.4   313.2  5736.8  311.43
  5759.3  311.38    5809  313.77    5886   315.2  6057.3  318.71  6174.9  322.03
#Mann= 8 ,-1 , 0
  4088.7      .1       0    4877     .12       0  4964.4     .07       0
  4970.4     .12       0  5094.8      .1       0  5395.4     .05       0
  5721.6     .08       0    5886      .1       0
Bank Sta=4964.4,4970.4
XS Rating Curve= 0 ,0
Exp/Cntr=0.3,0.1

Type RM Length L Ch R = 1 ,7490    ,230,230,230
BEGIN DESCRIPTION:
Mapping XS 6b622da6
END DESCRIPTION:
XS GIS Cut Line= 6
      2266833.38     13424732.89        2266073.     13424701.64
      2266000.08     13424639.14      2265875.08     13424659.97
      2265807.37     13424722.47      2265172.35     13425685.47
#Sta/Elev= 30
  4042.4   316.9  4765.7  303.92  4768.4  303.42  4771.7  303.92  4788.7  305.93
  4795.9  308.96  4824.3   310.7  4874.8  309.76  4897.7  311.54  4939.4  310.94
  4972.3  311.28  4977.3  307.58  5022.3   311.6  5043.4  311.47  5050.2  309.57
  5057.5  311.31  5071.7  310.88  5078.5  308.33  5085.9  311.01  5092.7  308.56
  5100.1  310.47  5106.9  308.92  5114.2  311.14  5159.5  309.35  5184.5   308.4
  5212.7  304.15  5552.4  306.81  5747.2  311.03  5924.9  312.86    6285   321.7
#Mann= 8 ,-1 , 0
  4042.4      .1       0  4765.7     .07       0  4771.7      .1       0
  4939.4     .12       0  5159.5      .1       0  5552.4     .05       0
  5747.2     .08       0  5924.9      .1       0
Bank Sta=4765.7,4771.7
XS Rating Curve= 0 ,0
Exp/Cntr=0.3,0.1

Type RM Length L Ch R = 1 ,7260    ,261,261,261
BEGIN DESCRIPTION:
UNT039 IN SUCR 14.0
END DESCRIPTION:
XS GIS Cut Line= 4
       2266833.4     13424659.97      2265859.46     13424441.22
      2265599.04     13424519.35       2265067.8     13425649.53
#Sta/Elev= 30
  3905.6  317.05  4625.4  304.49    4947  302.62  4996.6   300.9  4999.3   300.4
  5002.6   300.9  5062.2  302.92  5109.5  302.88  5228.2  301.47  5294.5  303.51
  5413.3  304.18    5492  304.73  5514.8  304.59  5520.3  303.24  5564.8  303.64
  5659.9  305.93  5887.3  307.83  5924.6   308.2  5935.4  309.99  5994.8  310.58
  6180.9  314.44  6198.2  316.31    6221  314.84  6243.8     317  6249.3   316.2
  6300.5  317.46  6340.5  319.53  6346.1  318.81  6399.4  320.81  6424.5  320.06
#Mann= 10 ,-1 , 0
  3905.6      .1       0    4947     .12       0  4996.6     .07       0
  5002.6     .12       0  5109.5      .1       0  5413.3     .05       0
  5564.8     .08       0  5659.9     .05       0  5887.3     .08       0
  5994.8      .1       0
Bank Sta=4996.6,5002.6
XS Rating Curve= 0 ,0
Exp/Cntr=0.3,0.1

Type RM Length L Ch R = 1 ,7000    ,503,503,503
BEGIN DESCRIPTION:
UNT039 IN SUCR 13.0
END DESCRIPTION:
XS GIS Cut Line= 3
      2266787.71     13424546.85      2265587.72     13424246.85
      2264387.68     13424546.87
#Sta/Elev= 30
  3798.3  315.98  4200.3  309.34  4269.9  309.29  4393.6  306.26  4723.4  302.17
  4865.8  301.87    4997  299.69  4999.8  299.19    5003  299.69  5058.4  301.58
  5113.4  301.21  5158.9  299.92    5177  301.73  5189.8  300.62  5241.4  302.05
  5375.4  301.97  5383.1  304.13  5388.3  304.26    5396  306.84  5437.2  307.29
  5594.4  304.75  5704.3  306.52  5746.5  308.07  5778.1  307.66  5929.8  310.09
  5973.2   311.6  6031.9   310.9  6076.3  310.35    6084  313.07  6272.2  315.88
#Mann= 9 ,-1 , 0
  3798.3      .1       0  4865.8     .12       0    4997     .07       0
    5003     .12       0  5113.4     .05       0  5704.3      .1       0
  5778.1     .05       0  5929.8      .1       0  6031.9     .05       0
Bank Sta=4997,5003
XS Rating Curve= 0 ,0
Exp/Cntr=0.3,0.1

Type RM Length L Ch R = 1 ,6999    ,503,503,503
BEGIN DESCRIPTION:
UNT039 IN SUCR 13.0
END DESCRIPTION:
XS GIS Cut Line= 3
      2266787.71     13424546.85      2265587.72     13424246.85
      2264387.68     13424546.87
#Sta/Elev= 30
  3798.3  315.98  4200.3  309.34  4269.9  309.29  4393.6  306.26  4723.4  302.17
  4865.8  301.87  4963.1  299.98    5012  300.54  5014.2  299.69  5016.9  299.19
  5020.2  299.69  5058.4  301.58  5113.4  301.21  5158.9  299.92    5177  301.73
  5189.8  300.62  5241.4  302.05  5375.4  301.97    5396  306.84  5437.2  307.29
  5594.4  304.75  5704.3  306.52  5746.5  308.07  5778.1  307.66  5929.8  310.09
  5973.2   311.6  6031.9   310.9  6076.3  310.35    6084  313.07  6272.2  315.88
#Mann= 9 ,-1 , 0
  3798.3      .1       0  4865.8     .12       0  5014.2     .07       0
  5020.2     .12       0  5113.4     .05       0  5704.3      .1       0
  5778.1     .05       0  5929.8      .1       0  6031.9     .05       0
Bank Sta=5014.2,5020.2
XS Rating Curve= 0 ,0
Exp/Cntr=0.3,0.1

Type RM Length L Ch R = 1 ,6497    ,413,413,413
BEGIN DESCRIPTION:
UNT039 IN SUCR 12.0
END DESCRIPTION:
XS GIS Cut Line= 3
      2266787.75     13423546.85      2265587.72     13423746.85
      2264387.74     13424446.84
#Sta/Elev= 30
  3757.5  314.75  4142.8  307.04  4702.9  303.53  4891.9  300.35    4977  297.78
  4981.9  296.04    4997  295.69  4999.8  295.19    5003  295.69  5024.9  296.37
    5032   298.9  5040.6  299.03  5099.4  297.86  5136.2   299.3  5142.4  297.26
  5148.1  298.14  5161.1  296.86  5179.6  300.75    5383  301.32  5404.5  305.71
  5435.9  303.64  5441.7  305.36  5484.7  306.39  5797.5  306.76  5845.3  306.88
  6189.3  307.64  6210.8  308.98  6216.5  311.11  6247.6  315.06  6363.3  315.99
#Mann= 7 ,-1 , 0
  3757.5      .1       0  4891.9     .12       0    4997     .07       0
    5003     .12       0  5161.1     .05       0  5797.5      .1       0
  5845.3     .05       0
Bank Sta=4997,5003
XS Rating Curve= 0 ,0
Exp/Cntr=0.3,0.1

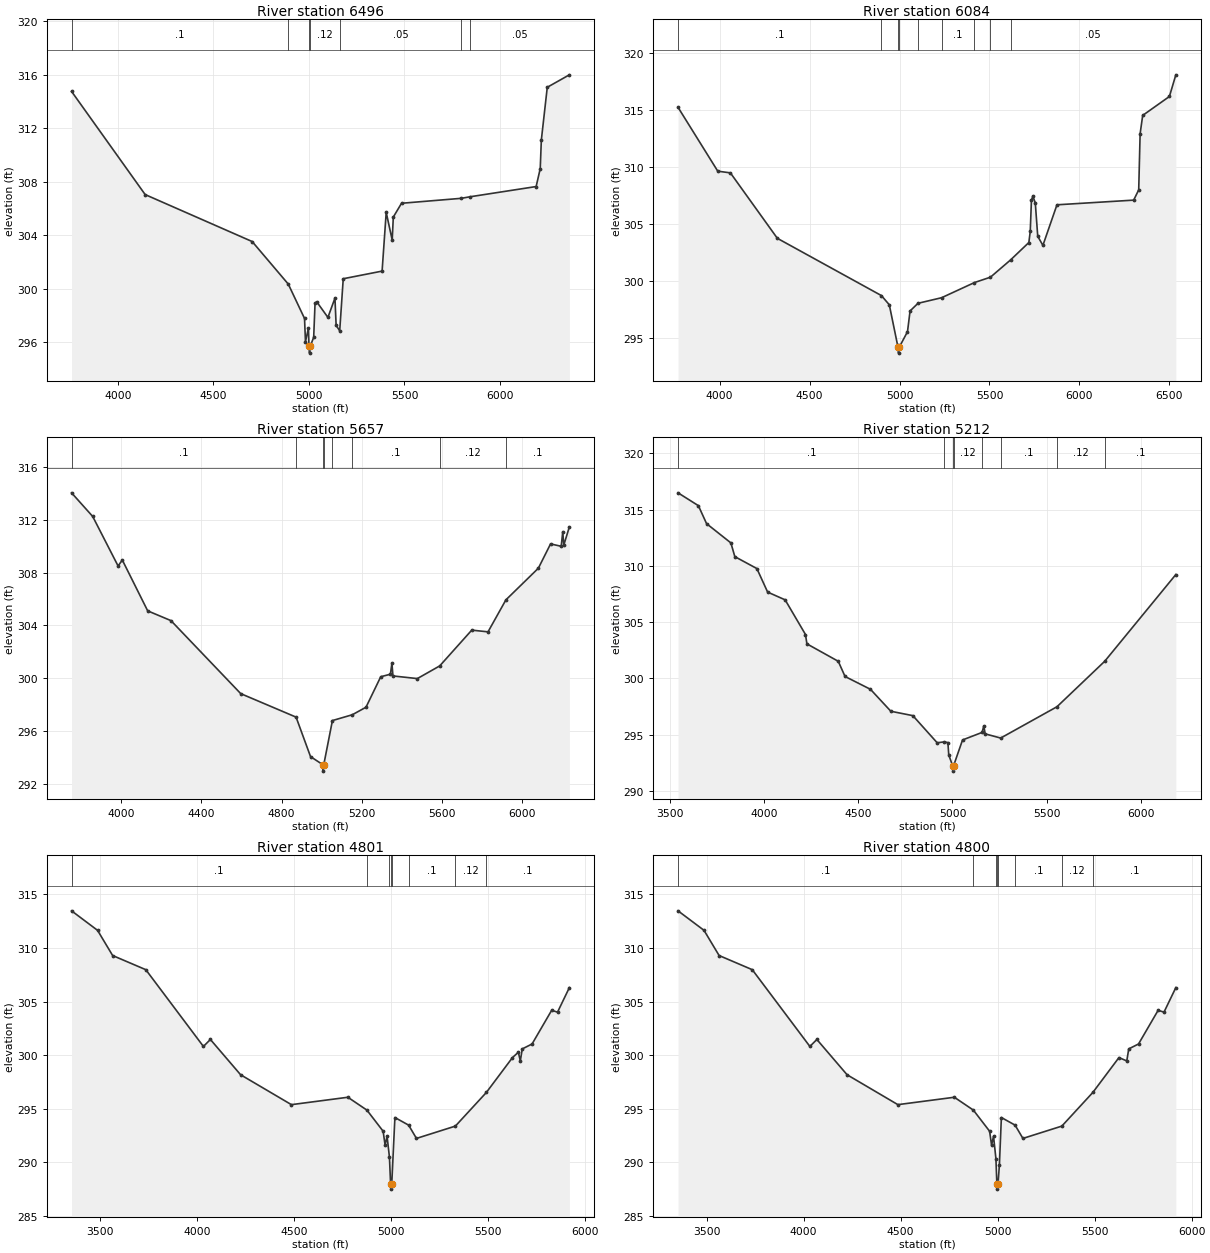
Type RM Length L Ch R = 1 ,6496    ,412,412,412
BEGIN DESCRIPTION:
UNT039 IN SUCR 12.0
END DESCRIPTION:
XS GIS Cut Line= 3
      2266787.75     13423546.85      2265587.72     13423746.85
      2264387.74     13424446.84
#Sta/Elev= 30
  3757.5  314.75  4142.8  307.04  4702.9  303.53  4891.9  300.35    4977  297.78
  4981.9  296.04  4997.2  297.05  5000.4  295.69  5003.2  295.19  5006.4  295.69
  5024.9  296.37    5032   298.9  5040.6  299.03  5099.4  297.86  5136.2   299.3
  5142.4  297.26  5161.1  296.86  5179.6  300.75    5383  301.32  5404.5  305.71
  5435.9  303.64  5441.7  305.36  5484.7  306.39  5797.5  306.76  5845.3  306.88
  6189.3  307.64  6210.8  308.98  6216.5  311.11  6247.6  315.06  6363.3  315.99
#Mann= 7 ,-1 , 0
  3757.5      .1       0  4891.9     .12       0  5000.4     .07       0
  5006.4     .12       0  5161.1     .05       0  5797.5      .1       0
  5845.3     .05       0
Bank Sta=5000.4,5006.4
XS Rating Curve= 0 ,0
Exp/Cntr=0.3,0.1

Type RM Length L Ch R = 1 ,6084    ,427,427,427
BEGIN DESCRIPTION:
UNT039 IN SUCR 11.0
END DESCRIPTION:
XS GIS Cut Line= 3
      2266737.71     13423446.85      2265537.72     13423346.85
      2264337.72     13424346.86
#Sta/Elev= 30
  3769.3   315.2  3990.1   309.6  4060.3  309.45  4321.2  303.71  4899.2  298.69
  4943.3  297.88  4991.9  294.14  4994.7  293.64  4997.9  294.14  5044.4  295.52
  5058.7  297.34  5102.7  298.01  5233.9   298.5  5416.5  299.83  5505.2   300.3
  5616.8  301.81  5718.7  303.34  5726.5  304.31    5733  307.03  5740.8  307.41
  5754.5  306.82  5768.1  303.89  5796.8  303.09  5874.9  306.65  6301.2  307.06
  6329.2  307.96    6337  312.88  6351.3  314.49  6499.7  316.15  6535.5  318.05
#Mann= 9 ,-1 , 0
  3769.3      .1       0  4899.2     .12       0  4991.9     .07       0
  4997.9     .12       0  5102.7     .05       0  5233.9      .1       0
  5416.5     .05       0  5505.2      .1       0  5616.8     .05       0
Bank Sta=4991.9,4997.9
XS Rating Curve= 0 ,0
Exp/Cntr=0.3,0.1

Type RM Length L Ch R = 1 ,5657    ,445,445,445
BEGIN DESCRIPTION:
UNT039 IN SUCR 10.0
END DESCRIPTION:
XS GIS Cut Line= 3
      2266687.75     13423346.86      2265487.72     13422946.85
      2264287.72     13422746.85
#Sta/Elev= 30
  3753.3  314.04  3858.7  312.25  3985.2   308.5  4006.3  308.95  4132.8   305.1
  4248.8  304.36  4596.6  298.83  4872.5  297.05  4944.5  294.06  5004.7  293.46
  5007.5  292.96  5010.7  293.46  5053.6  296.79  5152.7  297.23    5221   297.8
  5294.5  300.11  5342.7   300.3  5350.3  301.14  5355.3  300.17    5477  299.97
  5588.5  300.93  5748.2  303.64  5829.3  303.51  5918.3  305.93  6080.2  308.33
    6141  310.17  6194.2  309.99  6201.8   311.1  6206.9  310.08  6234.8  311.46
#Mann= 8 ,-1 , 0
  3753.3      .1       0  4872.5     .12       0  5004.7     .07       0
  5010.7     .12       0  5053.6     .05       0  5152.7      .1       0
  5588.5     .12       0  5918.3      .1       0
Bank Sta=5004.7,5010.7
XS Rating Curve= 0 ,0
Exp/Cntr=0.3,0.1

Type RM Length L Ch R = 1 ,5212    ,412,412,412
BEGIN DESCRIPTION:
UNT039 IN SUCR 9.0
END DESCRIPTION:
XS GIS Cut Line= 3
      2266837.74     13423346.87      2265637.72     13422546.85
      2264437.72     13422646.85
#Sta/Elev= 30
  3540.9  316.49  3649.1  315.35  3692.7  313.75  3821.9  312.04  3842.9  310.82
  3960.1  309.76  4017.2  307.67  4110.3  306.98  4218.5   303.9    4226  303.07
  4392.7  301.52  4428.8  300.17    4564  299.03  4672.2  297.08  4789.3  296.69
  4918.5  294.28  4957.4  294.36  4975.6  294.29  4980.1   293.2  5000.2  292.26
    5003  291.76  5006.2  292.26  5053.4  294.53  5157.3   295.2  5166.3  295.77
  5173.8  295.07  5256.2   294.7  5555.3  297.48  5809.1  301.52  6187.3  309.23
#Mann= 8 ,-1 , 0
  3540.9      .1       0  4957.4     .12       0  5000.2     .07       0
  5006.2     .12       0  5157.3     .08       0  5256.2      .1       0
  5555.3     .12       0  5809.1      .1       0
Bank Sta=5000.2,5006.2
XS Rating Curve= 0 ,0
Exp/Cntr=0.3,0.1

Type RM Length L Ch R = 1 ,4801    ,509,509,509
BEGIN DESCRIPTION:
Mapping XS 156242b0
END DESCRIPTION:
XS GIS Cut Line= 3
      2266776.14      13423107.9       2265760.5     13422217.27
      2264557.35     13422045.39
#Sta/Elev= 30
  3352.4  313.47  3486.4  311.65  3564.2   309.3  3735.1  307.98  4032.1  300.82
  4068.1  301.47  4223.8  298.18  4485.7  295.39  4776.8  296.08  4874.9  294.88
  4958.6  292.91  4968.7  291.61  4978.8  292.44  4991.1  290.49    4997  288.01
  4999.8  287.51    5003  288.01  5019.2  294.19  5089.9  293.48  5130.3  292.24
    5331  293.39  5490.8  296.53  5625.3  299.78  5655.6  300.28  5665.7  299.47
  5675.8  300.59  5726.3  301.05  5827.3  304.19  5857.6  304.02  5918.6  306.31
#Mann= 8 ,-1 , 0
  3352.4      .1       0  4874.9     .12       0  4991.1     .08       0
    4997     .07       0    5003     .08       0  5089.9      .1       0
    5331     .12       0  5490.8      .1       0
Bank Sta=4997,5003
XS Rating Curve= 0 ,0
Exp/Cntr=0.3,0.1

Type RM Length L Ch R = 1 ,4800    ,509,509,509
BEGIN DESCRIPTION:
Mapping XS 156242b0
END DESCRIPTION:
XS GIS Cut Line= 3
      2266776.14      13423107.9       2265760.5     13422217.27
      2264557.35     13422045.39
#Sta/Elev= 30
  3352.4  313.47  3486.4  311.65  3564.2   309.3  3735.1  307.98  4032.1  300.82
  4068.1  301.47  4223.8  298.18  4485.7  295.39  4776.8  296.08  4874.9  294.88
  4958.6  292.91  4968.7  291.61  4978.8  292.44  4991.1  290.36    4996  288.01
  4998.7  287.51    5002  288.01  5009.1  289.78  5019.2  294.19  5089.9  293.48
  5130.3  292.24    5331  293.39  5490.8  296.53  5625.3  299.78  5665.7  299.47
  5675.8  300.59  5726.3  301.05  5827.3  304.19  5857.6  304.02  5918.6  306.31
#Mann= 8 ,-1 , 0
  3352.4      .1       0  4874.9     .12       0  4991.1     .08       0
    4996     .07       0    5002     .08       0  5089.9      .1       0
    5331     .12       0  5490.8      .1       0
Bank Sta=4996,5002
XS Rating Curve= 0 ,0
Exp/Cntr=0.3,0.1