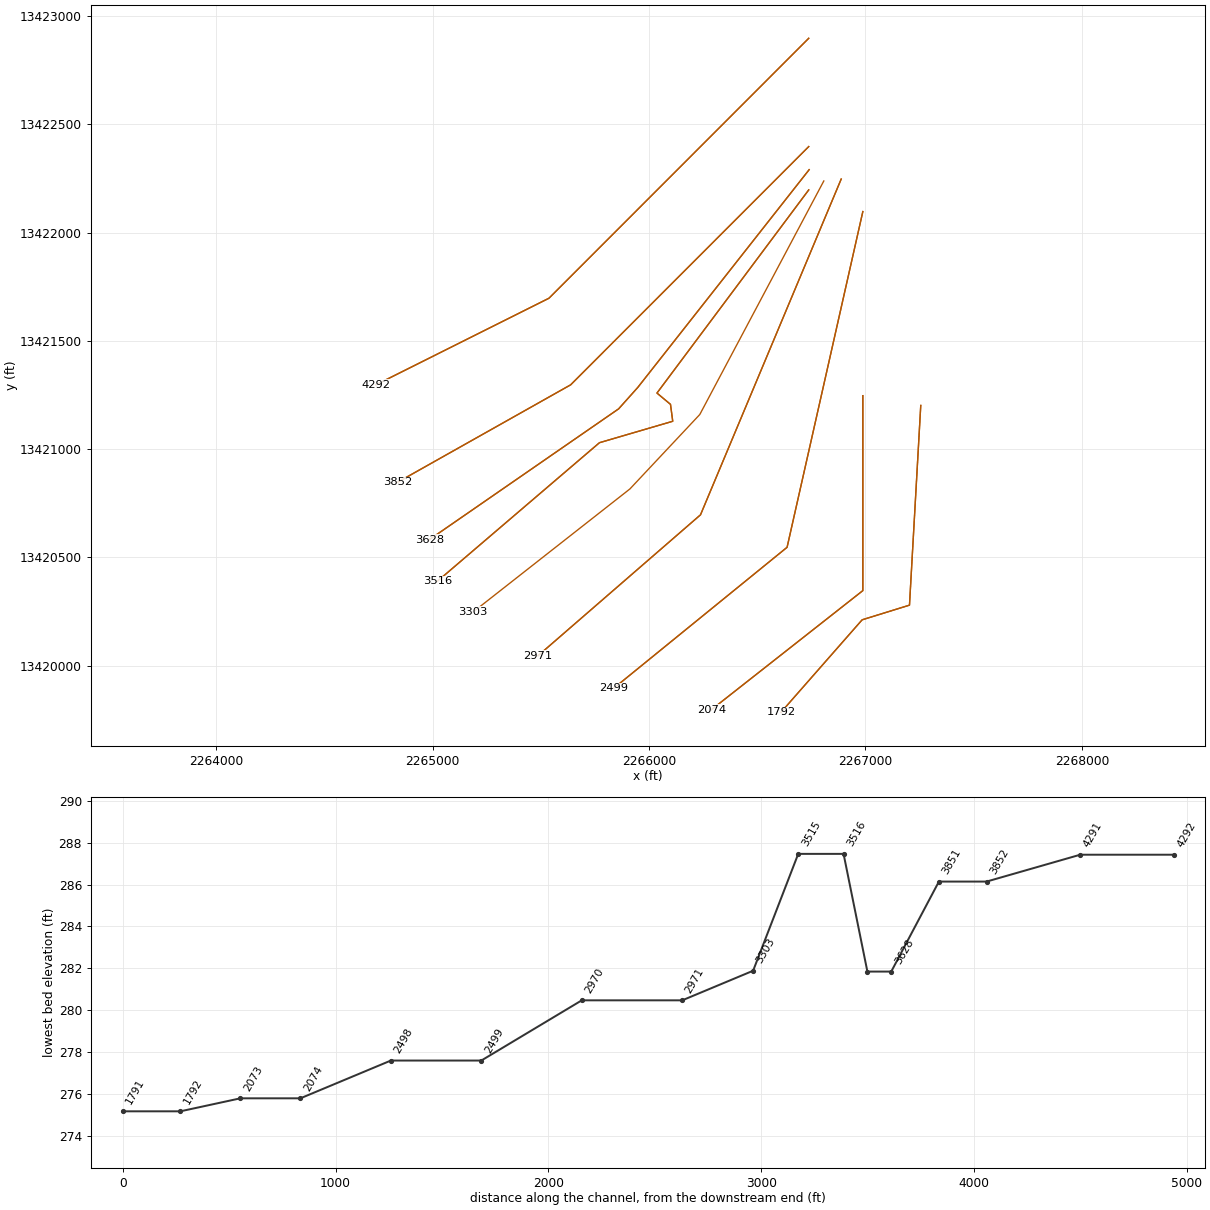
HEC-RAS study UNT039 IN SUCR.prj: UNT039 IN SUCR Base Level Engineering

--- UNT039 IN SUCR.g01 (geometry) --- (continued)

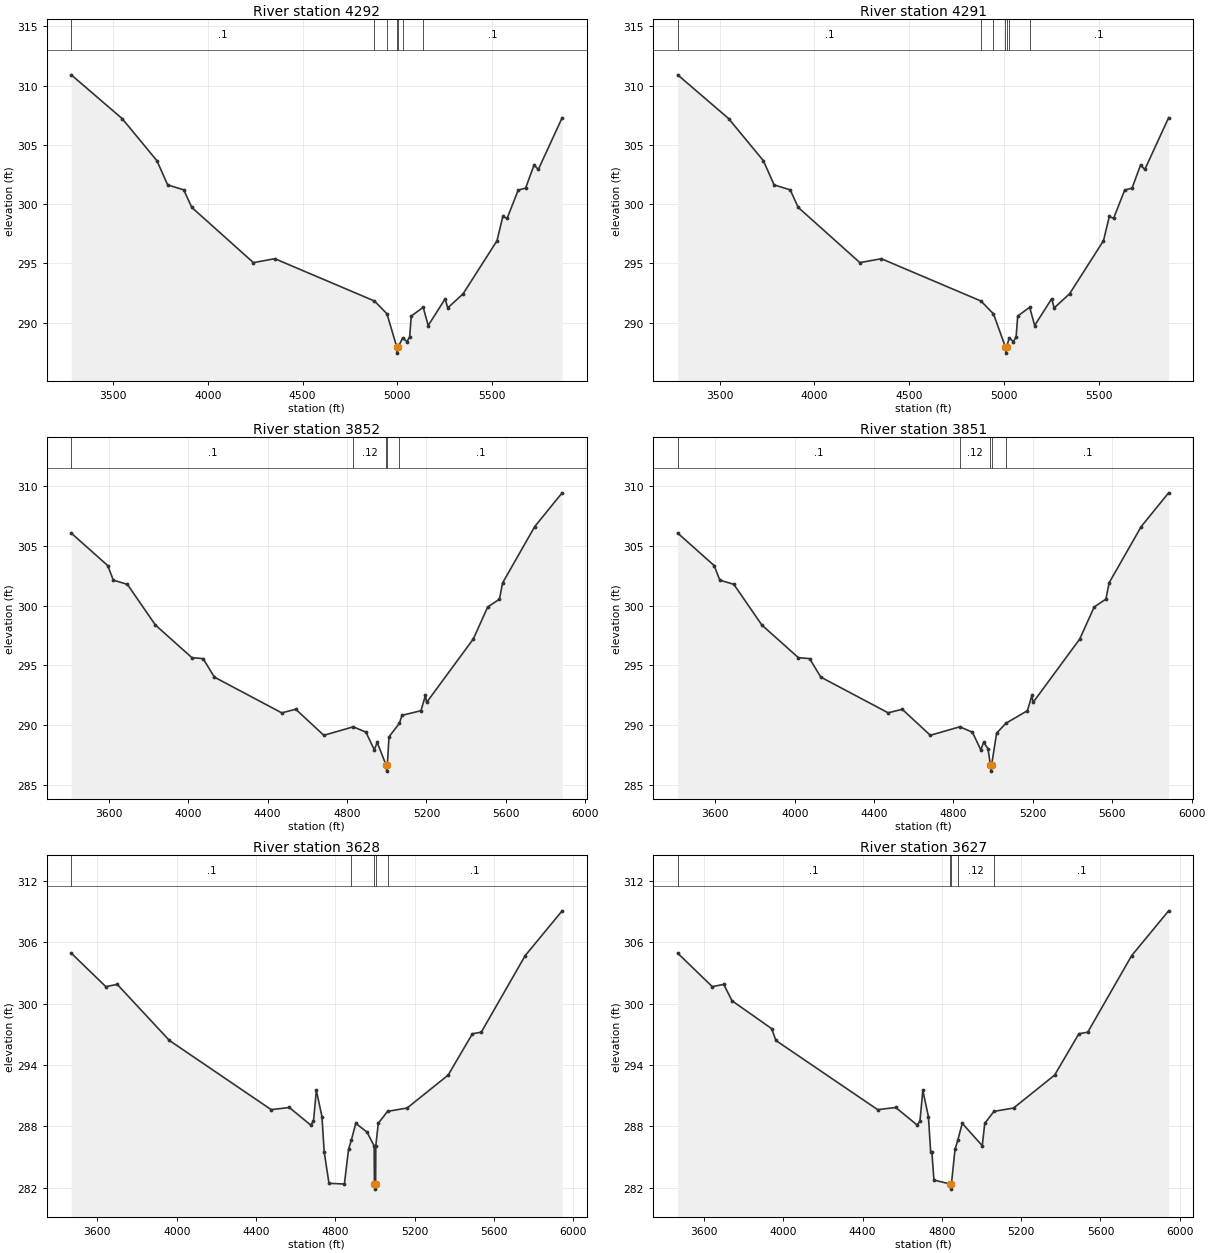
Type RM Length L Ch R = 1 ,4292    ,440,440,440
BEGIN DESCRIPTION:
UNT039 IN SUCR 8.0
END DESCRIPTION:
XS GIS Cut Line= 3
      2266737.72     13422896.85      2265537.72     13421696.85
       2264737.7     13421296.85
#Sta/Elev= 30
  3278.2  310.91  3546.9  307.22  3730.7  303.66  3787.3  301.62  3872.2   301.2
  3914.6  299.72  4239.9  295.06    4353  295.39  4878.9  291.82  4944.9  290.74
    4997  287.92  4999.8  287.42    5003  287.92    5028   288.7  5050.7  288.39
  5064.7  288.79  5073.1  290.55  5136.3  291.29  5162.5  289.75    5252     292
  5265.9  291.24    5347  292.43  5525.9  296.91  5556.6  298.96    5579  298.79
  5637.7  301.18  5676.8  301.35  5721.5   303.3  5743.9  302.92  5869.7  307.29
#Mann= 7 ,-1 , 0
  3278.2      .1       0  4878.9     .05       0  4944.9     .12       0
    4997     .07       0    5003     .12       0    5028     .08       0
  5136.3      .1       0
Bank Sta=4997,5003
XS Rating Curve= 0 ,0
Exp/Cntr=0.3,0.1

Type RM Length L Ch R = 1 ,4291    ,440,440,440
BEGIN DESCRIPTION:
UNT039 IN SUCR 8.0
END DESCRIPTION:
XS GIS Cut Line= 3
      2266737.72     13422896.85      2265537.72     13421696.85
       2264737.7     13421296.85
#Sta/Elev= 30
  3278.2  310.91  3546.9  307.22  3730.7  303.66  3787.3  301.62  3872.2   301.2
  3914.6  299.72  4239.9  295.06    4353  295.39  4878.9  291.82  4944.9  290.74
  5008.6  287.92  5011.3  287.42  5014.6  287.92    5028   288.7  5050.7  288.39
  5064.7  288.79  5073.1  290.55  5136.3  291.29  5162.5  289.75    5252     292
  5265.9  291.24    5347  292.43  5525.9  296.91  5556.6  298.96    5579  298.79
  5637.7  301.18  5676.8  301.35  5721.5   303.3  5743.9  302.92  5869.7  307.29
#Mann= 7 ,-1 , 0
  3278.2      .1       0  4878.9     .05       0  4944.9     .12       0
  5008.6     .07       0  5014.6     .12       0    5028     .08       0
  5136.3      .1       0
Bank Sta=5008.6,5014.6
XS Rating Curve= 0 ,0
Exp/Cntr=0.3,0.1

Type RM Length L Ch R = 1 ,3852    ,224,224,224
BEGIN DESCRIPTION:
UNT039 IN SUCR 7.0
END DESCRIPTION:
XS GIS Cut Line= 3
      2266737.75     13422396.88      2265637.72     13421296.85
      2264837.68     13420846.83
#Sta/Elev= 30
  3410.3  306.07  3594.2  303.35  3622.5  302.13  3693.2  301.78  3834.6  298.37
  4018.5  295.64    4075  295.56  4131.6  294.01    4471  291.02  4541.7  291.32
  4683.1  289.14  4831.7  289.85  4895.3   289.4  4937.7  287.92  4951.8  288.55
    4997  286.64  4999.8  286.14    5003  286.64  5011.5  289.01  5064.1  290.15
  5076.6  290.81  5172.5   291.2  5195.1  292.48  5200.9  291.89  5436.4  297.21
  5508.7  299.88    5568  300.54  5583.9   301.9  5745.9  306.62  5883.9  309.44
#Mann= 5 ,-1 , 0
  3410.3      .1       0  4831.7     .12       0    4997     .07       0
    5003     .12       0  5064.1      .1       0
Bank Sta=4997,5003
XS Rating Curve= 0 ,0
Exp/Cntr=0.3,0.1

Type RM Length L Ch R = 1 ,3851    ,224,224,224
BEGIN DESCRIPTION:
UNT039 IN SUCR 7.0
END DESCRIPTION:
XS GIS Cut Line= 3
      2266737.75     13422396.88      2265637.72     13421296.85
      2264837.68     13420846.83
#Sta/Elev= 30
  3410.3  306.07  3594.2  303.35  3622.5  302.13  3693.2  301.78  3834.6  298.37
  4018.5  295.64    4075  295.56  4131.6  294.01    4471  291.02  4541.7  291.32
  4683.1  289.14  4831.7  289.85  4895.3   289.4  4937.7  287.92  4951.8  288.55
  4973.9  288.02  4985.9  286.64  4988.7  286.14  4991.9  286.64  5017.3  289.32
  5064.1  290.15  5172.5   291.2  5195.1  292.48  5200.9  291.89  5436.4  297.21
  5508.7  299.88    5568  300.54  5583.9   301.9  5745.9  306.62  5883.9  309.44
#Mann= 5 ,-1 , 0
  3410.3      .1       0  4831.7     .12       0  4985.9     .07       0
  4991.9     .12       0  5064.1      .1       0
Bank Sta=4985.9,4991.9
XS Rating Curve= 0 ,0
Exp/Cntr=0.3,0.1

Type RM Length L Ch R = 1 ,3628    ,112,112,112
BEGIN DESCRIPTION:
Mapping XS 9d91971b
END DESCRIPTION:
XS GIS Cut Line= 4
      2266739.66     13422290.18        2265948.     13421284.97
      2265859.46     13421186.02      2264984.48     13420581.86
#Sta/Elev= 30
    3468  304.95  3642.5  301.67  3700.2  301.89  3963.2   296.4  4476.4  289.63
  4567.7  289.84  4675.2  288.13  4689.6  288.49  4704.1  291.51  4732.4  288.95
  4743.7   285.5  4767.8  282.42  4845.5  282.35  4866.4  285.73  4880.6  286.65
  4902.9  288.29  4959.7  287.43  4995.5  286.08    4997  282.35  4999.8  281.85
    5003  282.35  5003.9   286.1  5016.5  288.29  5062.9  289.46  5161.9  289.79
  5368.7  293.01  5491.1  297.06  5535.7  297.21  5757.4  304.71  5943.6  309.09
#Mann= 5 ,-1 , 0
    3468      .1       0  4880.6     .12       0    4997     .07       0
    5003     .12       0  5062.9      .1       0
Bank Sta=4997,5003
XS Rating Curve= 0 ,0
Exp/Cntr=0.3,0.1

Type RM Length L Ch R = 1 ,3627    ,112,112,112
BEGIN DESCRIPTION:
Mapping XS 9d91971b
END DESCRIPTION:
XS GIS Cut Line= 4
      2266739.66     13422290.18        2265948.     13421284.97
      2265859.46     13421186.02      2264984.48     13420581.86
#Sta/Elev= 30
    3468  304.95  3642.5  301.67  3700.2  301.89  3741.9  300.29  3942.4  297.55
  3963.2   296.4  4476.4  289.63  4567.7  289.84  4675.2  288.13  4689.6  288.49
  4704.1  291.51  4732.4  288.95  4743.7   285.5  4749.6   285.5  4760.3  282.74
  4842.5  282.35  4845.3  281.85  4848.5  282.35  4866.4  285.73  4880.6  286.65
  4902.9  288.29  5003.9   286.1  5016.5  288.29  5062.9  289.46  5161.9  289.79
  5368.7  293.01  5491.1  297.06  5535.7  297.21  5757.4  304.71  5943.6  309.09
#Mann= 5 ,-1 , 0
    3468      .1       0  4842.5     .07       0  4848.5      .1       0
  4880.6     .12       0  5062.9      .1       0
Bank Sta=4842.5,4848.5
XS Rating Curve= 0 ,0
Exp/Cntr=0.3,0.1

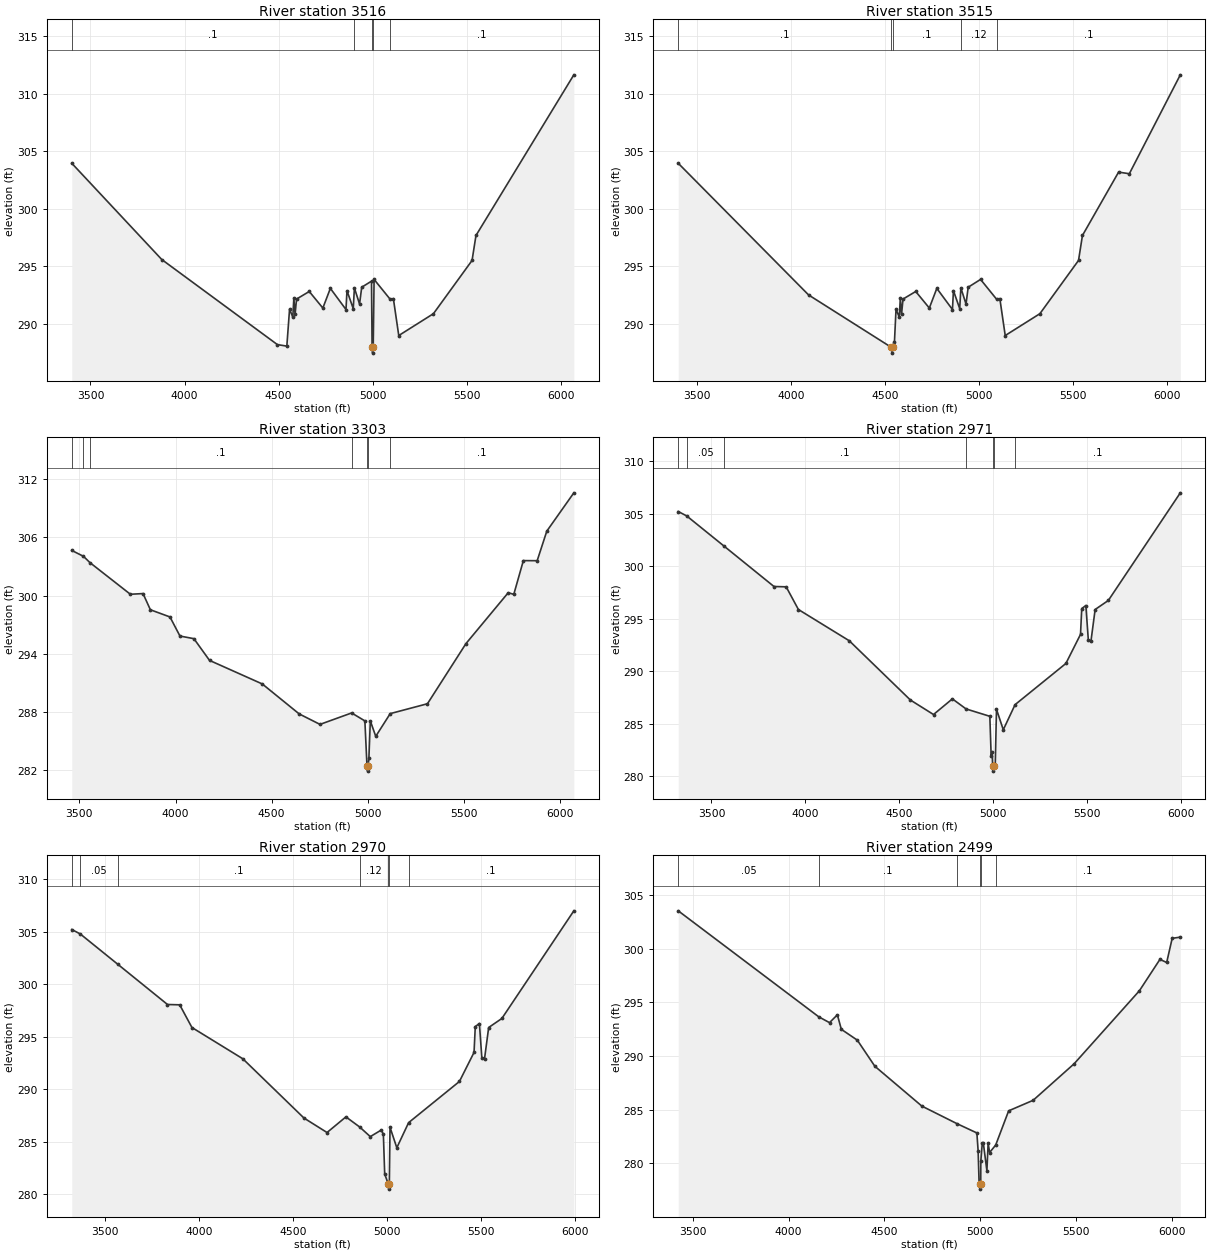
Type RM Length L Ch R = 1 ,3516    ,213,213,213
BEGIN DESCRIPTION:
UNT039 IN SUCR 6.0
END DESCRIPTION:
XS GIS Cut Line= 6
      2266737.74     13422196.87      2266036.54     13421258.93
      2266099.04     13421206.85      2266109.46     13421128.72
      2265770.92     13421029.77      2265021.84     13420389.93
#Sta/Elev= 30
  3400.5  303.97  3878.9   295.6  4493.7   288.2  4543.8  288.07  4558.3  291.28
  4575.6  290.59  4581.1  292.24  4587.6  290.82  4595.4  292.16    4663  292.82
  4735.3  291.38  4775.2  293.09  4858.3  291.25  4863.5  292.89  4896.9  291.33
    4903  293.13  4930.4  291.73  4941.9  293.19    4994  293.72    4997  287.96
  4999.8  287.46    5003  287.96  5007.7  293.87  5093.3  292.14  5110.2   292.2
  5138.8  288.99  5323.2  290.89  5528.5  295.52  5549.3  297.69  6069.6  311.66
#Mann= 5 ,-1 , 0
  3400.5      .1       0    4903     .12       0    4997     .07       0
    5003     .12       0  5093.3      .1       0
Bank Sta=4997,5003
XS Rating Curve= 0 ,0
Exp/Cntr=0.3,0.1

Type RM Length L Ch R = 1 ,3515    ,212,212,212
BEGIN DESCRIPTION:
UNT039 IN SUCR 6.0
END DESCRIPTION:
XS GIS Cut Line= 6
      2266737.74     13422196.87      2266036.54     13421258.93
      2266099.04     13421206.85      2266109.46     13421128.72
      2265770.92     13421029.77      2265021.84     13420389.93
#Sta/Elev= 30
  3400.5  303.97  4093.5  292.52  4533.7  287.96  4536.5  287.46  4539.7  287.96
    4550  288.46  4558.3  291.28  4575.6  290.59  4581.1  292.24  4587.6  290.82
  4595.4  292.16    4663  292.82  4735.3  291.38  4775.2  293.09  4858.3  291.25
  4863.5  292.89  4896.9  291.33    4903  293.13  4930.4  291.73  4941.9  293.19
  5007.7  293.87  5093.3  292.14  5110.2   292.2  5138.8  288.99  5323.2  290.89
  5528.5  295.52  5549.3  297.69  5741.5   303.2  5798.6  303.06  6069.6  311.66
#Mann= 5 ,-1 , 0
  3400.5      .1       0  4533.7     .07       0  4539.7      .1       0
    4903     .12       0  5093.3      .1       0
Bank Sta=4533.7,4539.7
XS Rating Curve= 0 ,0
Exp/Cntr=0.3,0.1

Type RM Length L Ch R = 1 ,3303    ,333,333,333
BEGIN DESCRIPTION:
Mapping XS faa772e9
END DESCRIPTION:
XS GIS Cut Line= 4
      2266807.38     13422238.12      2266234.46     13421159.97
      2265911.54     13420816.22      2265187.55     13420248.49
#Sta/Elev= 30
  3460.2  304.65  3521.2  304.04  3554.9  303.39  3765.1  300.13    3831   300.2
  3869.3  298.53  3971.2  297.79  4023.2  295.82  4095.8  295.55    4177  293.31
  4451.5  290.88  4643.6  287.79  4751.9  286.71  4916.5  287.89  4985.4  287.07
  4996.5  282.39  4999.3  281.89  5002.5  282.39  5006.4  283.27  5013.7  287.07
    5042  285.48  5117.3  287.82  5311.1  288.84  5511.7  295.05  5731.4  300.29
  5760.3  300.12  5810.1   303.6    5882  303.59  5932.1  306.64  6072.8  310.59
#Mann= 7 ,-1 , 0
  3460.2      .1       0  3521.2     .05       0  3554.9      .1       0
  4916.5     .12       0  4996.5     .07       0  5002.5     .12       0
  5117.3      .1       0
Bank Sta=4996.5,5002.5
XS Rating Curve= 0 ,0
Exp/Cntr=0.3,0.1

Type RM Length L Ch R = 1 ,2971    ,472,472,472
BEGIN DESCRIPTION:
UNT039 IN SUCR 5.0
END DESCRIPTION:
XS GIS Cut Line= 3
      2266887.72     13422246.86      2266237.72     13420696.85
      2265487.69     13420046.82
#Sta/Elev= 30
  3322.9   305.2    3368  304.78  3567.3   301.9  3832.6  298.06  3897.6  298.03
  3962.7  295.87  4233.8  292.89  4559.1  287.25  4682.1  285.87  4782.6  287.36
  4855.6   286.4    4982   285.7  4989.1  281.92  4994.5  282.31    4997  280.98
  4999.8  280.48    5003  280.98  5010.8  280.98  5017.4  286.37  5053.6  284.42
  5116.4  286.81  5386.9  290.73  5464.8   293.5  5471.4  295.96  5493.3  296.25
  5506.5  292.95  5520.8  292.91  5542.7  295.87  5612.9  296.73  5996.2  306.98
#Mann= 7 ,-1 , 0
  3322.9      .1       0    3368     .05       0  3567.3      .1       0
  4855.6     .12       0    4997     .07       0    5003     .12       0
  5116.4      .1       0
Bank Sta=4997,5003
XS Rating Curve= 0 ,0
Exp/Cntr=0.3,0.1

Type RM Length L Ch R = 1 ,2970    ,472,472,472
BEGIN DESCRIPTION:
UNT039 IN SUCR 5.0
END DESCRIPTION:
XS GIS Cut Line= 3
      2266887.72     13422246.86      2266237.72     13420696.85
      2265487.69     13420046.82
#Sta/Elev= 30
  3322.9   305.2    3368  304.78  3567.3   301.9  3832.6  298.06  3897.6  298.03
  3962.7  295.87  4233.8  292.89  4559.1  287.25  4682.1  285.87  4782.6  287.36
  4855.6   286.4  4912.3  285.48  4971.2  286.11    4982   285.7  4989.1  281.92
  5007.8  280.98  5010.6  280.48  5013.8  280.98  5017.4  286.37  5053.6  284.42
  5116.4  286.81  5386.9  290.73  5464.8   293.5  5471.4  295.96  5493.3  296.25
  5506.5  292.95  5520.8  292.91  5542.7  295.87  5612.9  296.73  5996.2  306.98
#Mann= 7 ,-1 , 0
  3322.9      .1       0    3368     .05       0  3567.3      .1       0
  4855.6     .12       0  5007.8     .07       0  5013.8     .12       0
  5116.4      .1       0
Bank Sta=5007.8,5013.8
XS Rating Curve= 0 ,0
Exp/Cntr=0.3,0.1

Type RM Length L Ch R = 1 ,2499    ,425,425,425
BEGIN DESCRIPTION:
UNT039 IN SUCR 4.0
END DESCRIPTION:
XS GIS Cut Line= 3
      2266987.72     13422096.84      2266637.72     13420546.85
      2265837.71     13419896.85
#Sta/Elev= 30
  3424.6  303.52    4158  293.65    4214  293.11    4255  293.84  4275.5  292.49
    4359  291.48  4450.5  289.05  4695.8  285.34  4878.5  283.71  4982.9  282.84
  4989.4  281.18  4994.6  278.11    4997  278.11  4999.8  277.61    5003  278.11
  5003.4  280.21    5011  281.87  5016.8  281.87  5035.2  279.32  5041.6  281.88
  5049.5  281.02  5081.2  281.72  5148.7   284.9  5276.5  285.88  5490.3  289.28
    5831  296.08  5938.1     299  5973.3  298.71    6002  300.96  6044.4  301.07
#Mann= 6 ,-1 , 0
  3424.6     .05       0    4158      .1       0  4878.5     .12       0
    4997     .07       0    5003     .12       0  5081.2      .1       0
Bank Sta=4997,5003
XS Rating Curve= 0 ,0
Exp/Cntr=0.3,0.1

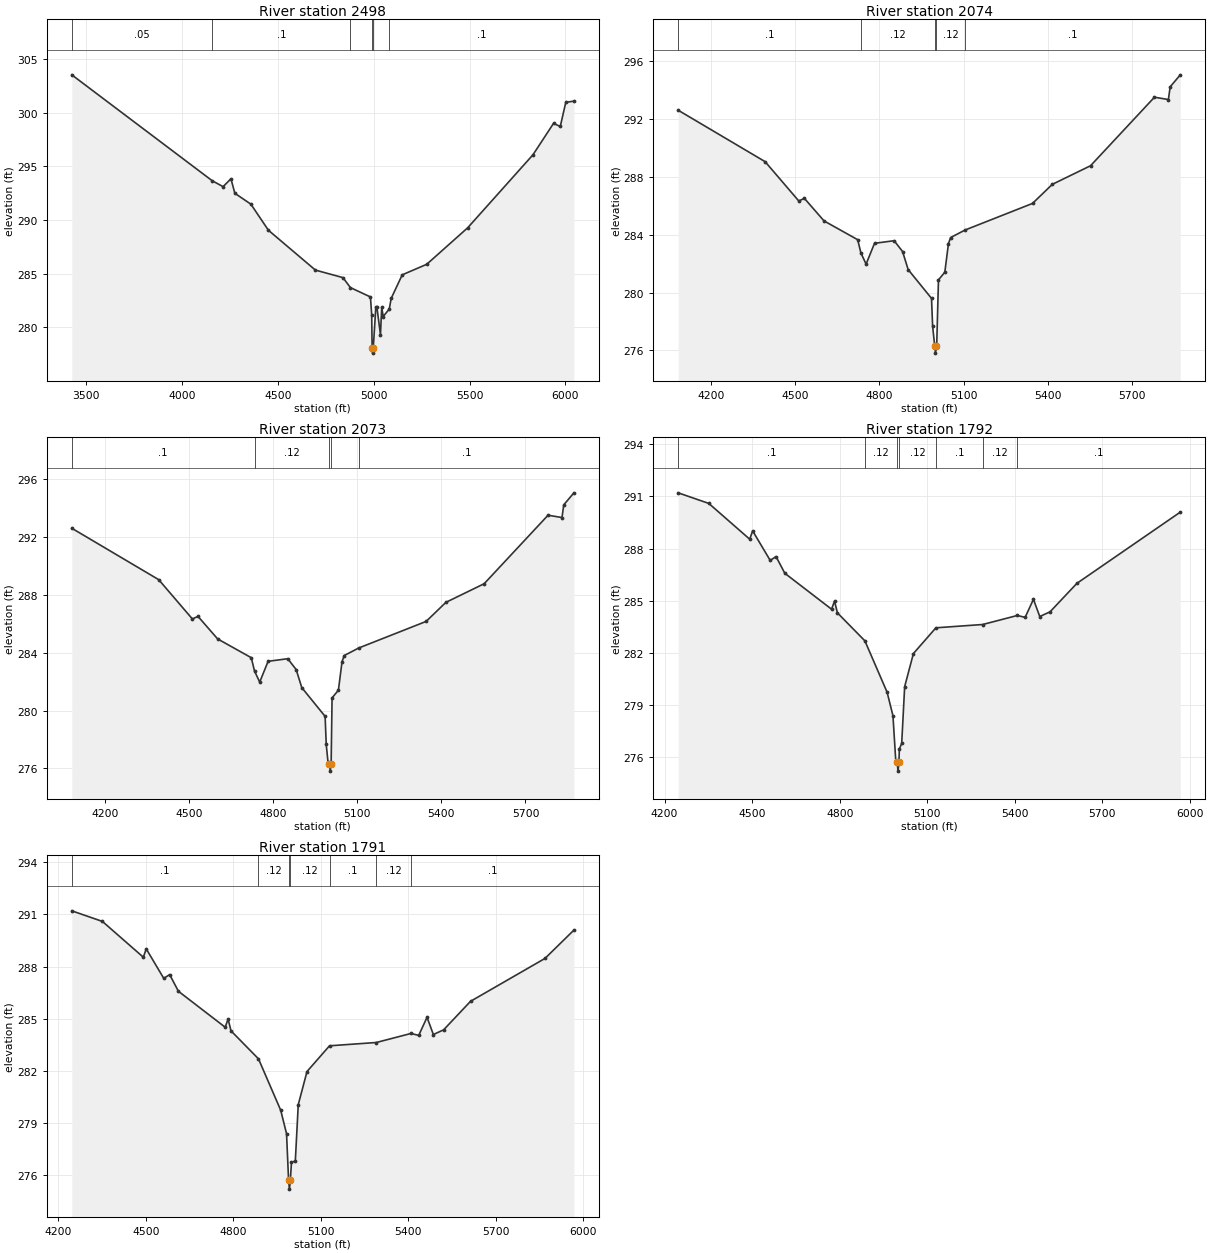
Type RM Length L Ch R = 1 ,2498    ,425,425,425
BEGIN DESCRIPTION:
UNT039 IN SUCR 4.0
END DESCRIPTION:
XS GIS Cut Line= 3
      2266987.72     13422096.84      2266637.72     13420546.85
      2265837.71     13419896.85
#Sta/Elev= 30
  3424.6  303.52    4158  293.65    4214  293.11    4255  293.84  4275.5  292.49
    4359  291.48  4450.5  289.05  4695.8  285.34  4839.3  284.64  4878.5  283.71
  4982.9  282.84  4989.4  281.18  4991.6  278.11  4994.3  277.61  4997.6  278.11
    5011  281.87  5016.8  281.87  5035.2  279.32  5041.6  281.88  5049.5  281.02
  5081.2  281.72  5091.2  282.71  5148.7   284.9  5276.5  285.88  5490.3  289.28
    5831  296.08  5938.1     299  5973.3  298.71    6002  300.96  6044.4  301.07
#Mann= 6 ,-1 , 0
  3424.6     .05       0    4158      .1       0  4878.5     .12       0
  4991.6     .07       0  4997.6     .12       0  5081.2      .1       0
Bank Sta=4991.6,4997.6
XS Rating Curve= 0 ,0
Exp/Cntr=0.3,0.1

Type RM Length L Ch R = 1 ,2074    ,282,282,282
BEGIN DESCRIPTION:
UNT039 IN SUCR 3.0
END DESCRIPTION:
XS GIS Cut Line= 3
      2266987.72     13421246.86      2266987.72     13420346.85
      2266287.74     13419796.87
#Sta/Elev= 30
  4082.4  292.62  4392.4  289.06  4512.4  286.34  4532.4  286.52  4602.4  284.96
  4722.4  283.66  4733.9  282.74  4752.4  281.97  4782.4  283.41  4852.4  283.59
  4882.4  282.84  4902.4  281.59  4985.6   279.6  4989.6  277.66    4997  276.31
  4999.8  275.81    5003  276.31  5004.1  276.31  5010.4  280.88    5033  281.41
    5046  283.39  5053.8  283.81  5105.3  284.33  5345.7  286.17  5416.2  287.49
  5552.7  288.78  5780.4  293.52  5830.1  293.36  5836.5  294.24  5872.6  295.07
#Mann= 5 ,-1 , 0
  4082.4      .1       0  4733.9     .12       0    4997     .07       0
    5003     .12       0  5105.3      .1       0
Bank Sta=4997,5003
XS Rating Curve= 0 ,0
Exp/Cntr=0.3,0.1

Type RM Length L Ch R = 1 ,2073    ,282,282,282
BEGIN DESCRIPTION:
UNT039 IN SUCR 3.0
END DESCRIPTION:
XS GIS Cut Line= 3
      2266987.72     13421246.86      2266987.72     13420346.85
      2266287.74     13419796.87
#Sta/Elev= 30
  4082.4  292.62  4392.4  289.06  4512.4  286.34  4532.4  286.52  4602.4  284.96
  4722.4  283.66  4733.9  282.74  4752.4  281.97  4782.4  283.41  4852.4  283.59
  4882.4  282.84  4902.4  281.59  4985.6   279.6  4989.6  277.66    4996  276.42
  5001.1  276.31  5003.8  275.81  5007.1  276.31  5010.4  280.88    5033  281.41
    5046  283.39  5053.8  283.81  5105.3  284.33  5345.7  286.17  5416.2  287.49
  5552.7  288.78  5780.4  293.52  5830.1  293.36  5836.5  294.24  5872.6  295.07
#Mann= 5 ,-1 , 0
  4082.4      .1       0  4733.9     .12       0  5001.1     .07       0
  5007.1     .12       0  5105.3      .1       0
Bank Sta=5001.1,5007.1
XS Rating Curve= 0 ,0
Exp/Cntr=0.3,0.1

Type RM Length L Ch R = 1 ,1792    ,271,271,271
BEGIN DESCRIPTION:
Mapping XS b7d7ea5b
END DESCRIPTION:
XS GIS Cut Line= 4
      2267255.29     13421201.68      2267203.21     13420279.77
      2266984.46     13420212.06      2266609.48       13419785.
#Sta/Elev= 30
  4246.5  291.21  4351.5   290.6  4491.7  288.54  4501.7  289.02  4561.8  287.32
  4581.9  287.54  4611.9  286.58  4772.2  284.51  4782.2  284.98  4792.2   284.3
  4886.3  282.69  4962.5  279.73  4982.5  278.38  4992.5  275.69    4997  275.69
  4999.8  275.19    5003  275.69  5004.4  276.46  5012.5  276.79  5022.6  280.05
  5052.6  281.96  5129.7  283.44  5289.9  283.63  5408.8  284.15  5435.4  284.04
  5463.9  285.08  5485.6  284.09  5520.8  284.36  5612.9     286  5967.2   290.1
#Mann= 7 ,-1 , 0
  4246.5      .1       0  4886.3     .12       0    4997     .07       0
    5003     .12       0  5129.7      .1       0  5289.9     .12       0
  5408.8      .1       0
Bank Sta=4997,5003
XS Rating Curve= 0 ,0
Exp/Cntr=0.3,0.1

Type RM Length L Ch R = 1 ,1791    ,727,727,727
BEGIN DESCRIPTION:
Mapping XS b7d7ea5b
END DESCRIPTION:
XS GIS Cut Line= 4
      2267255.29     13421201.68      2267203.21     13420279.77
      2266984.46     13420212.06      2266609.48       13419785.
#Sta/Elev= 30
  4246.5  291.21  4351.5   290.6  4491.7  288.54  4501.7  289.02  4561.8  287.32
  4581.9  287.54  4611.9  286.58  4772.2  284.51  4782.2  284.98  4792.2   284.3
  4886.3  282.69  4962.5  279.73  4982.5  278.38  4989.5  275.69  4992.3  275.19
  4995.5  275.69  4999.4  276.75  5012.5  276.79  5022.6  280.05  5052.6  281.96
  5129.7  283.44  5289.9  283.63  5408.8  284.15  5435.4  284.04  5463.9  285.08
  5485.6  284.09  5520.8  284.36  5612.9     286  5868.1  288.47  5967.2   290.1
#Mann= 7 ,-1 , 0
  4246.5      .1       0  4886.3     .12       0  4989.5     .07       0
  4995.5     .12       0  5129.7      .1       0  5289.9     .12       0
  5408.8      .1       0
Bank Sta=4989.5,4995.5
XS Rating Curve= 0 ,0
Exp/Cntr=0.3,0.1