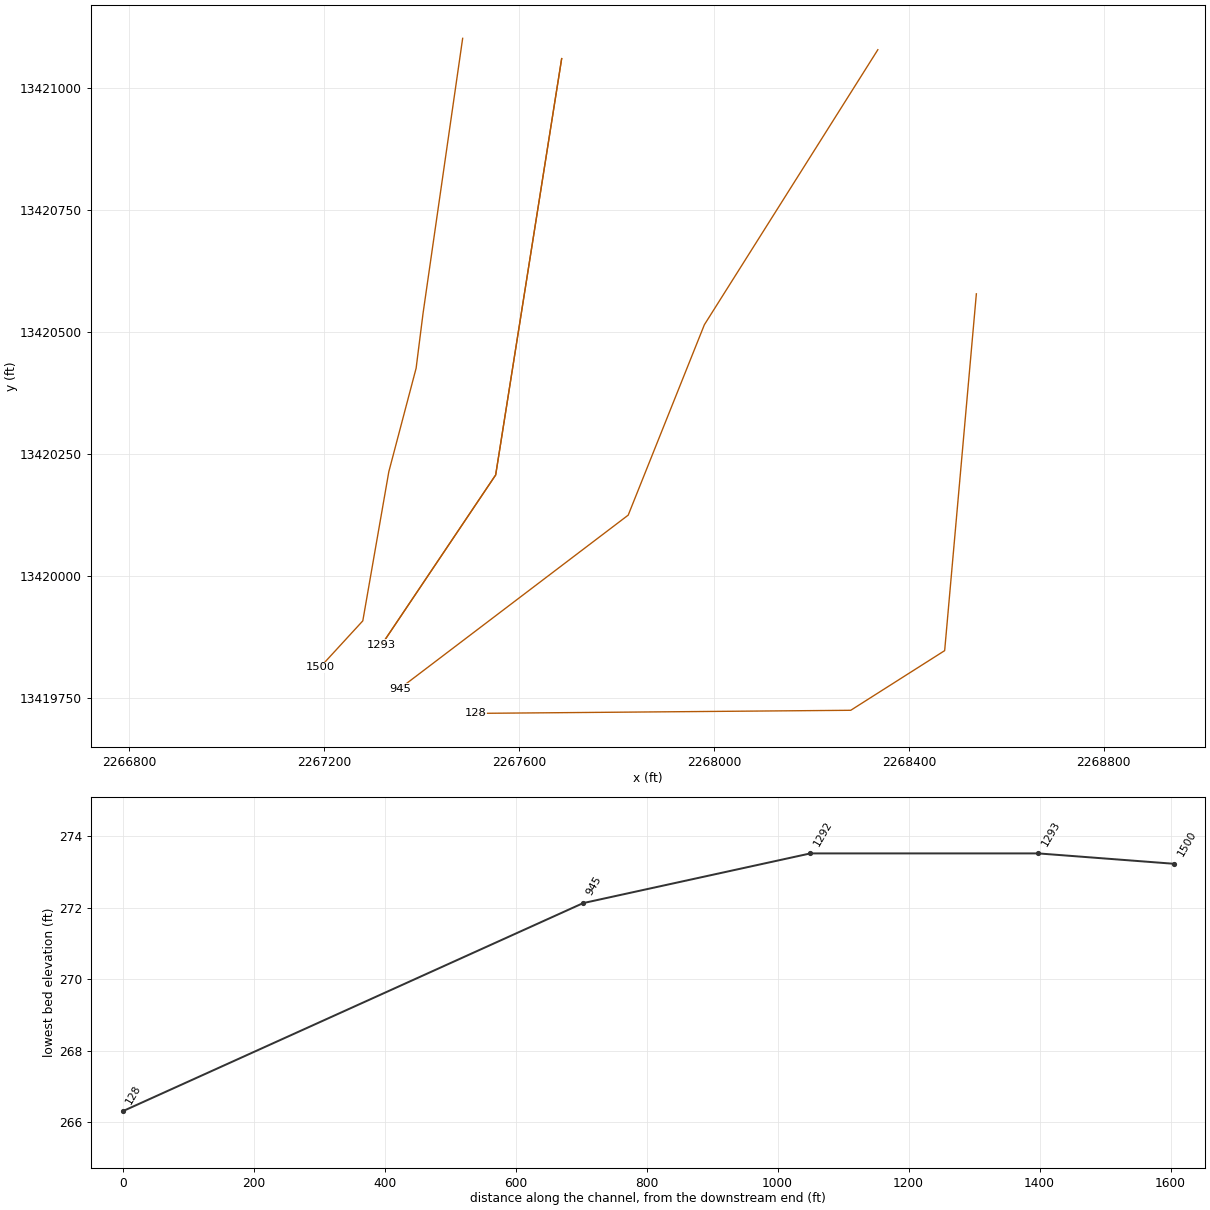
HEC-RAS study UNT039 IN SUCR.prj: UNT039 IN SUCR Base Level Engineering

--- UNT039 IN SUCR.g01 (geometry) --- (continued)

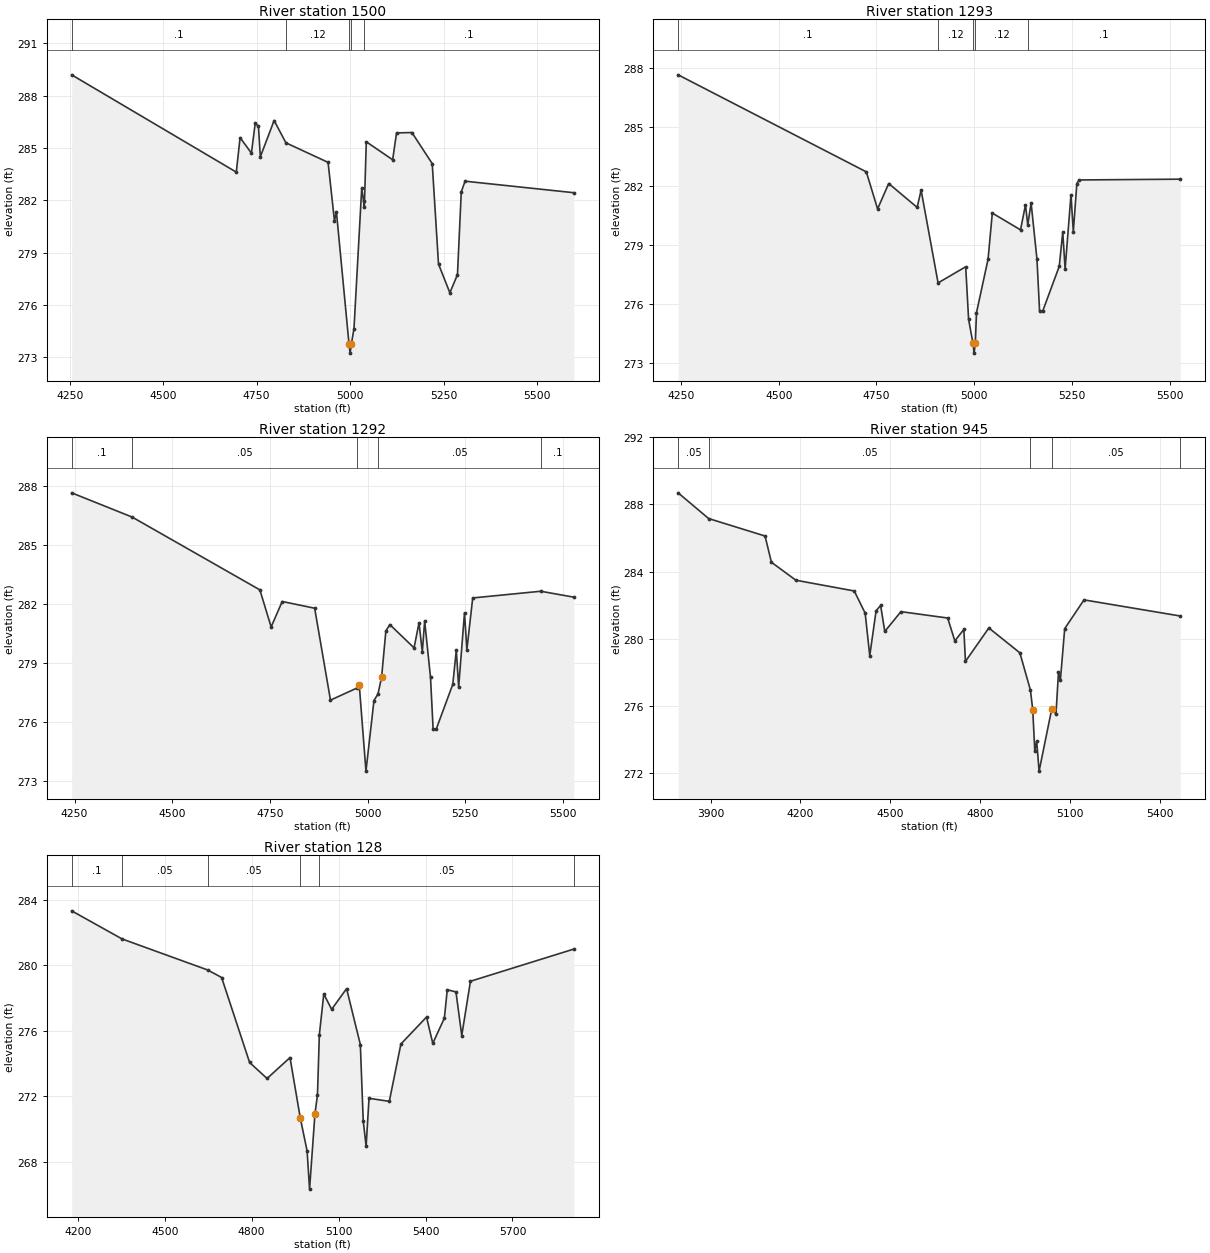
Type RM Length L Ch R = 1 ,1500    ,207,207,207
BEGIN DESCRIPTION:
Mapping XS 1898a6ce
END DESCRIPTION:
XS GIS Cut Line= 6
      2267484.46     13421102.69      2267403.26     13420539.01
      2267388.94     13420425.73      2267332.95     13420213.49
      2267279.57      13419907.5      2267192.21     13419812.44
#Sta/Elev= 30
  4255.2  289.19  4695.5  283.61  4705.6  285.59  4735.9   284.7  4746.1  286.42
  4754.7  286.24  4759.8  284.49  4796.6  286.57  4828.2  285.29  4940.9  284.17
    4958  280.81  4963.2  281.34    4997  273.73  4999.8  273.23    5003  273.73
  5010.2  274.64  5030.9   282.7  5035.9  281.93  5037.9  281.62  5043.1  285.35
  5113.6  284.32    5124  285.86  5165.1  285.88  5219.4   284.1  5236.2  278.34
  5266.6  276.69  5286.9  277.73  5297.1  282.48  5307.2  283.09  5598.1  282.43
#Mann= 5 ,-1 , 0
  4255.2      .1       0  4828.2     .12       0    4997     .07       0
    5003     .12       0  5035.9      .1       0
Bank Sta=4997,5003
XS Rating Curve= 0 ,0
Exp/Cntr=0.3,0.1

Type RM Length L Ch R = 1 ,1293    ,348,348,348
BEGIN DESCRIPTION:
UNT039 IN SUCR 2.0
END DESCRIPTION:
XS GIS Cut Line= 3
      2267687.59     13421061.05      2267552.17     13420206.85
      2267317.81     13419857.92
#Sta/Elev= 30
  4242.4  287.63  4724.1  282.71  4752.9  280.83  4781.3  282.12  4854.1  280.91
  4864.3  281.78  4907.7  277.08  4978.4   277.9  4985.8  275.23    4997  274.02
  4999.8  273.52    5003  274.02    5006  275.57  5035.6  278.28  5046.5  280.62
  5118.7  279.77  5131.4  281.04  5137.2  280.02  5145.8  281.13  5160.8  278.27
  5167.5  275.64  5175.8  275.67  5217.8  277.92  5226.8  279.66  5232.8  277.78
  5247.8  281.55  5253.8  279.67  5262.8  282.12  5268.8   282.3  5527.6  282.34
#Mann= 5 ,-1 , 0
  4242.4      .1       0  4907.7     .12       0    4997     .07       0
    5003     .12       0  5137.2      .1       0
Bank Sta=4997,5003
XS Rating Curve= 0 ,0
Exp/Cntr=0.3,0.1

Type RM Length L Ch R = 1 ,1292    ,347,347,347
BEGIN DESCRIPTION:
UNT039 IN SUCR 2.0
END DESCRIPTION:
XS GIS Cut Line= 3
      2267687.59     13421061.05      2267552.17     13420206.85
      2267317.81     13419857.92
#Sta/Elev= 30
  4242.4  287.63  4397.3   286.4  4724.1  282.71  4752.9  280.83  4781.3  282.12
  4864.3  281.78  4904.8  277.12  4973.3  277.74  4978.4   277.9  4995.6  273.52
  5016.1   277.1  5026.3  277.43  5035.6  278.28  5046.5  280.62  5056.6  280.95
  5118.7  279.77  5131.4  281.04  5139.8  279.56  5145.8  281.13  5160.8  278.27
  5167.5  275.64  5175.8  275.67  5217.8  277.92  5226.8  279.66  5232.8  277.78
  5247.8  281.55  5253.8  279.67  5268.8   282.3  5442.8  282.64  5527.6  282.34
#Mann= 5 ,-1 , 0
  4242.4      .1       0  4397.3     .05       0  4973.3     .03       0
  5026.3     .05       0  5442.8      .1       0
Bank Sta=4978.4,5035.6
XS Rating Curve= 0 ,0
Exp/Cntr=0.3,0.1

Type RM Length L Ch R = 1 ,945     ,703,703,703
BEGIN DESCRIPTION:
Mapping XS 5e69d182
END DESCRIPTION:
XS GIS Cut Line= 4
      2268336.29     13421079.31      2267980.37     13420515.05
      2267824.12     13420124.43      2267355.37     13419768.52
#Sta/Elev= 30
  3791.9  288.69  3893.8  287.16  4082.1  286.12  4103.3  284.56    4185  283.49
  4379.9  282.85  4416.3  281.53  4431.6     279  4452.8  281.67  4467.9  281.99
  4481.8  280.44  4535.7  281.62  4691.8  281.24  4715.6  279.88  4745.7  280.56
  4751.1  278.66  4829.2  280.65  4932.7  279.17    4968  276.95  4975.7  275.78
  4982.6  273.33  4988.9  273.91  4996.9  272.13  5038.8   275.8  5053.3  275.53
  5061.6     278  5067.9  277.53  5082.4  280.61  5146.9  282.32  5468.3  281.36
#Mann= 5 ,-1 , 0
  3791.9     .05       0  3893.8     .05       0    4968     .03       0
  5038.8     .05       0  5468.3      .1       0
Bank Sta=4975.7,5038.8
XS Rating Curve= 0 ,0
Exp/Cntr=0.3,0.1

Type RM Length L Ch R = 1 ,128     ,0,0,0
BEGIN DESCRIPTION:
UNT039 IN SUCR 1.0
END DESCRIPTION:
XS GIS Cut Line= 4
      2268538.43     13420578.51      2268473.38     13419846.43
      2268280.67     13419724.03      2267510.95      13419717.7
#Sta/Elev= 30
  4178.8  283.34  4352.7  281.62  4648.3  279.72  4696.3  279.26  4792.9  274.06
  4853.1  273.08  4932.3  274.36  4967.9  270.65  4991.3  268.65  4999.8  266.31
  5018.4  270.91  5027.1  272.08  5033.6  275.76  5048.9  278.25    5076  277.31
  5127.6  278.58    5175  275.16    5185  270.49    5195  268.93    5205  271.87
    5275  271.68    5315  275.19  5403.4  276.84    5425  275.23    5465  276.77
    5475  278.51    5505  278.38    5525  275.71    5555  279.03  5911.8     281
#Mann= 6 ,-1 , 0
  4178.8      .1       0  4352.7     .05       0  4648.3     .05       0
  4967.9     .03       0  5033.6     .05       0  5911.8      .1       0
Bank Sta=4967.9,5018.4
XS Rating Curve= 0 ,0
Exp/Cntr=0.3,0.1

Chan Stop Cuts=-1
Use User Specified Reach Order=0
Composite Channel Slope=5