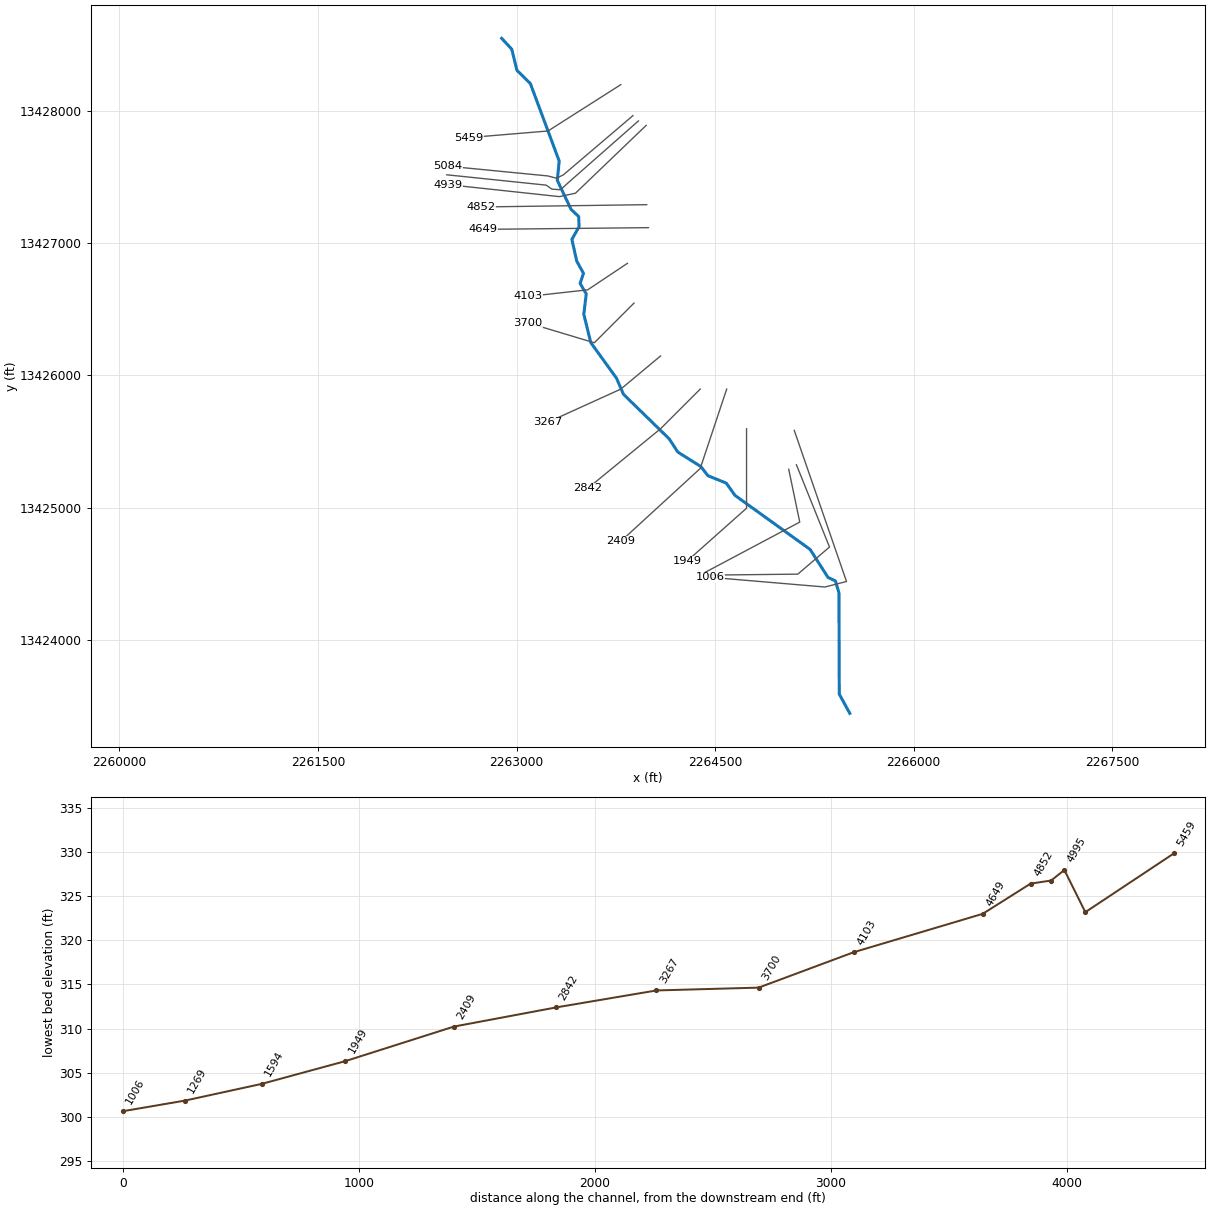
--- UNT040 IN SUCR.prj (project) ---

Proj Title=UNT040 IN SUCR Base Level Engineering
Current Plan=p01
Default Exp/Contr=0.3,0.1
English Units
Geom File=g01
Flow File=f01
Plan File=p01
Y Axis Title=Elevation
X Axis Title(PF)=Main Channel Distance
X Axis Title(XS)=Station
BEGIN DESCRIPTION:
UNT040 IN SUCR
END DESCRIPTION:
DSS Export Rating Curves= 0
DSS Export Rating Curve Sorted= 0
DSS Export Volume Flow Curves= 0
DXF OffsetX= 0
DXF OffsetY= 0
DXF ScaleX= 1
DXF ScaleY= 10

--- UNT040 IN SUCR.p01 (plan) ---

Plan Title=Multiple Run
Short Identifier=Multiple
Geom File=g01
Flow File=f01
Subcritical Flow
K Sum by GR= 0
Std Step Tol= 0.01
Critical Tol= 0.01
Num of Std Step Trials= 20
Max Error Tol= 0.3
Flow Tol Ratio= 0.001
Split Flow NTrial= 30
Split Flow Tol= 0.02
Split Flow Ratio= 0.02
Log Output Level= 0
Friction Slope Method= 1
Unsteady Friction Slope Method= 2
Unsteady Bridges Friction Slope Method= 1
Parabolic Critical Depth
Global Vel Dist=  1 , 1 , 1
Global Log Level= 0
CheckData=True
Encroach Param= -1, 0, 0, 0
BEGIN DESCRIPTION:
Multiple Run
END DESCRIPTION:

--- UNT040 IN SUCR.f01 (steady flow) ---

Flow Title=Multiple
Program Version=4.10
Number of Profiles= 7
Profile Names=10-year,25-year,50-year,1pct_min,100-year,1pct_plu,500-year
River Rch & RM=UNT040 IN SUCR,Reach-1         ,5459
      87     112     131     113     153     207     211
River Rch & RM=UNT040 IN SUCR,Reach-1         ,4649
     166     222     267     237     320     433     466
Boundary for River Rch & Prof#=UNT040 IN SUCR,Reach-1         , 1
Up Type= 0
Dn Type= 3
Dn Slope=0.0049
Boundary for River Rch & Prof#=UNT040 IN SUCR,Reach-1         , 2
Up Type= 0
Dn Type= 3
Dn Slope=0.0049
Boundary for River Rch & Prof#=UNT040 IN SUCR,Reach-1         , 3
Up Type= 0
Dn Type= 3
Dn Slope=0.0049
Boundary for River Rch & Prof#=UNT040 IN SUCR,Reach-1         , 4
Up Type= 0
Dn Type= 3
Dn Slope=0.0049
Boundary for River Rch & Prof#=UNT040 IN SUCR,Reach-1         , 5
Up Type= 0
Dn Type= 3
Dn Slope=0.0049
Boundary for River Rch & Prof#=UNT040 IN SUCR,Reach-1         , 6
Up Type= 0
Dn Type= 3
Dn Slope=0.0049
Boundary for River Rch & Prof#=UNT040 IN SUCR,Reach-1         , 7
Up Type= 0
Dn Type= 3
Dn Slope=0.0049
DSS Import GetInterval= 0
DSS Import GetPeak= 0
DSS Import FillOption= 0

--- UNT040 IN SUCR.g01 (geometry) ---

Geom Title=Existing Conditions
Program Version=4.10

River Reach=UNT040 IN SUCR  ,Reach-1
Reach XY= 30
      2262887.72     13428546.86      2262963.97     13428464.73
       2263003.3     13428304.59      2263104.38     13428205.51
      2263322.22     13427619.77      2263308.12     13427473.29
      2263412.04     13427254.76      2263469.51     13427200.62
      2263472.37     13427123.58      2263418.15     13427027.55
      2263454.47     13426864.49      2263505.97     13426771.21
      2263480.45     13426695.07      2263526.62     13426616.34
      2263508.24     13426462.52      2263560.93     13426248.27
      2263754.78     13425979.69      2263807.89     13425857.53
      2264154.09     13425520.15      2264217.76     13425421.79
       2264392.6     13425311.45      2264445.32     13425242.74
      2264584.64     13425186.51       2264650.3     13425093.98
      2265217.91     13424685.56      2265352.89     13424474.51
      2265409.35     13424446.89      2265436.06     13424356.89
      2265438.34     13423592.11      2265517.72     13423446.86

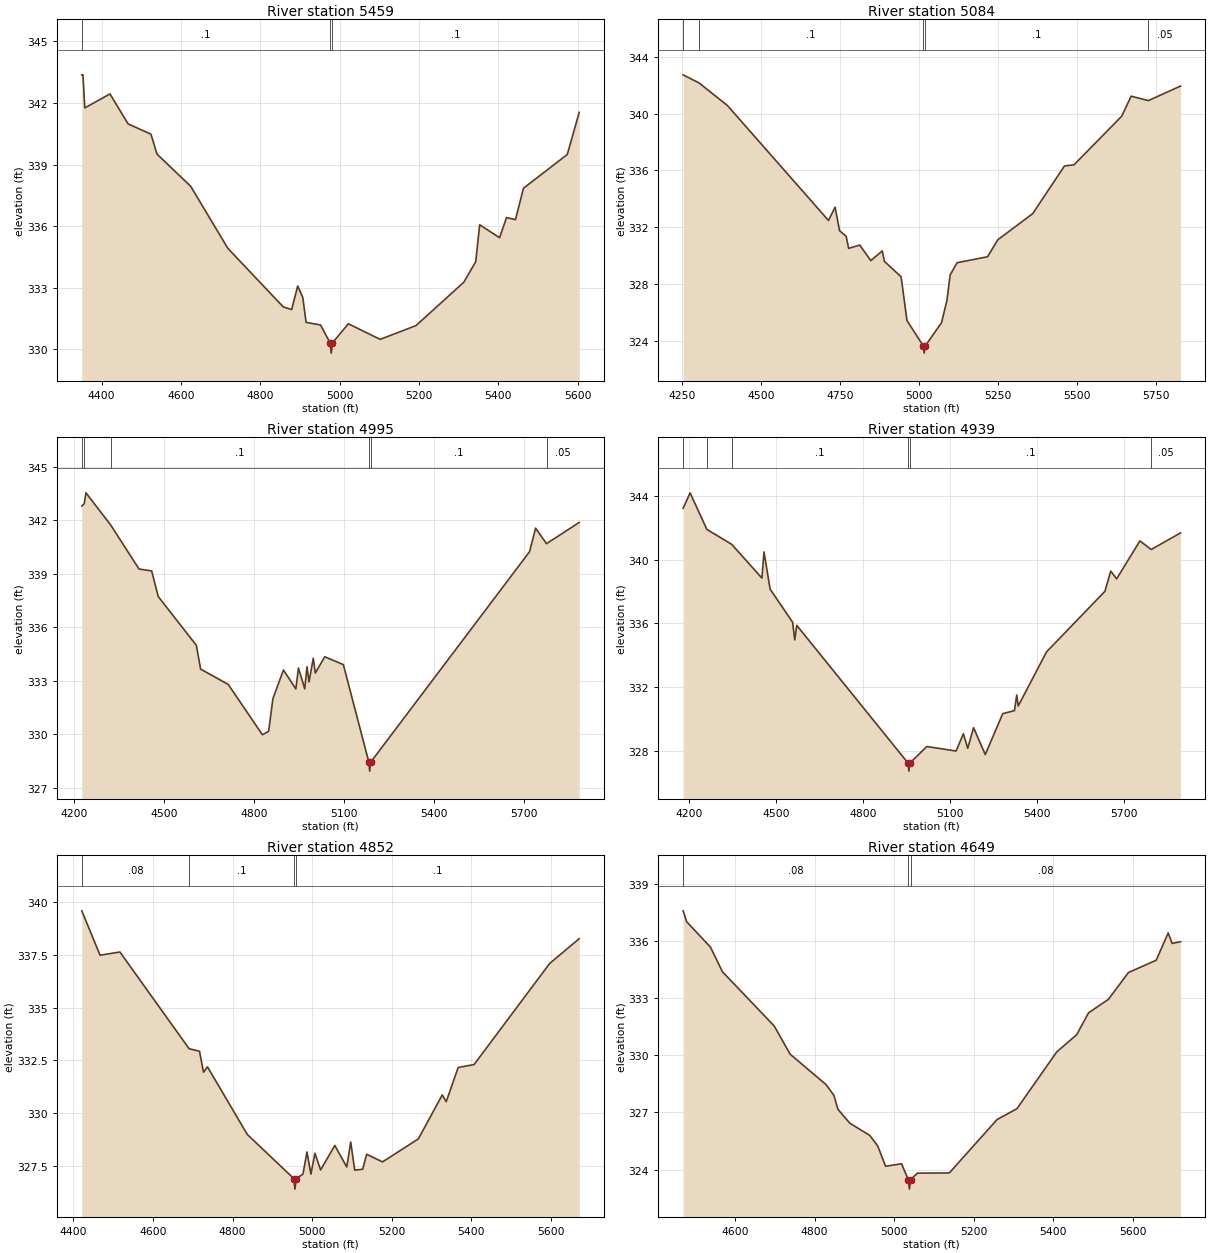
Type RM Length L Ch R = 1 ,5459    ,375,375,375
BEGIN DESCRIPTION:
UNT040 IN SUCR 10.0
END DESCRIPTION:
XS GIS Cut Line= 3
       2263787.7     13428196.84      2263237.72     13427846.85
      2262637.69     13427796.85
#Sta/Elev= 30
  4349.9  343.37  4352.8  343.37  4357.5  341.76    4421  342.44  4466.7  340.98
  4524.3  340.48  4539.5  339.51  4624.2  337.95  4718.2  334.92  4857.9  332.07
    4879  331.94  4894.3  333.09    4907  332.53  4915.4  331.32  4951.8  331.19
  4975.9  330.32  4978.7  329.82  4981.9  330.32  5021.9  331.25  5102.1  330.49
  5192.4  331.16  5312.9  333.27    5343  334.27    5353  336.07  5403.2  335.44
  5420.7  336.42  5443.3  336.32  5463.4  337.85  5573.8  339.49  5603.9  341.54
#Mann= 3 ,-1 , 0
  4349.9      .1       0  4975.9     .07       0  4981.9      .1       0
Bank Sta=4975.9,4981.9
XS Rating Curve= 0 ,0
Exp/Cntr=0.3,0.1

Type RM Length L Ch R = 1 ,5084    ,89,89,89
BEGIN DESCRIPTION:
Mapping XS 288a9d3b
END DESCRIPTION:
XS GIS Cut Line= 5
      2263879.44     13427962.94      2263354.25     13427515.88
      2263302.17     13427489.83      2263237.06      13427507.2
      2262482.27     13427580.94
#Sta/Elev= 30
  4254.2  342.72  4304.7  342.15  4394.5  340.56  4714.1  332.49    4735  333.42
  4749.2  331.77  4770.1  331.38  4777.8  330.53  4812.9  330.76  4848.1  329.67
  4884.3  330.35  4890.9  329.62  4943.9  328.53  4962.4  325.46  5014.1  323.67
  5016.8  323.17  5020.1  323.67  5071.7  325.31    5089  326.89    5099  328.66
  5120.8  329.52  5217.4  329.94  5249.7  331.13  5360.2  332.97  5460.7  336.32
  5490.9   336.4  5641.6  339.81  5671.7  341.22    5726  340.91  5827.9  341.93
#Mann= 5 ,-1 , 0
  4254.2     .08       0  4304.7      .1       0  5014.1     .07       0
  5020.1      .1       0    5726     .05       0
Bank Sta=5014.1,5020.1
XS Rating Curve= 0 ,0
Exp/Cntr=0.3,0.1

Type RM Length L Ch R = 1 ,4995    ,56,56,56
BEGIN DESCRIPTION:
UNT040 IN SUCR 9.0
END DESCRIPTION:
XS GIS Cut Line= 6
      2263920.97     13427922.91      2263384.63     13427450.77
      2263332.55     13427403.03      2263267.44     13427407.37
      2263224.04     13427437.75      2262473.12     13427515.88
#Sta/Elev= 30
  4225.9   342.8    4234  342.93  4239.8  343.54  4322.1  341.74  4416.7  339.27
  4458.9  339.16  4480.7  337.73  4607.9  334.99  4622.1  333.66  4714.2   332.8
    4828  329.98  4848.9  330.17  4863.1     332  4898.2  333.61  4939.6  332.55
  4948.3  333.72  4969.3  332.55  4976.7  333.79  4983.5  332.94  4997.7  334.27
  5004.5  333.44    5036  334.35    5098  333.91    5183  328.44  5185.7  327.94
    5189  328.44  5718.8  340.24  5738.9  341.56  5775.3  340.69  5884.3  341.88
#Mann= 6 ,-1 , 0
  4225.9      .1       0    4234     .08       0  4322.1      .1       0
    5183     .07       0    5189      .1       0  5775.3     .05       0
Bank Sta=5183,5189
XS Rating Curve= 0 ,0
Exp/Cntr=0.3,0.1

Type RM Length L Ch R = 1 ,4939    ,87,87,87
BEGIN DESCRIPTION:
Mapping XS 67b9a0c9
END DESCRIPTION:
XS GIS Cut Line= 4
      2263979.27     13427889.16      2263445.39     13427376.99
      2263323.87     13427350.95      2262478.57     13427441.98
#Sta/Elev= 30
  4179.9  343.21  4203.9  344.18  4261.7  341.89  4347.6  340.95  4451.4  338.84
  4458.6  340.48  4479.7  338.15  4557.4  336.07  4564.6  334.97  4571.5  335.88
  4955.3  327.25    4958  326.75  4961.3  327.25  5019.6  328.29  5120.6  328.01
  5145.8  329.09  5160.8  328.18  5180.9  329.47  5221.2  327.79  5281.5  330.35
  5321.8  330.54  5329.7  331.52  5334.8  330.83  5432.4  334.22  5633.5  338.01
  5653.7  339.28  5673.8  338.79  5754.2  341.17  5793.1  340.63  5894.2  341.67
#Mann= 6 ,-1 , 0
  4179.9      .1       0  4261.7     .08       0  4347.6      .1       0
  4955.3     .07       0  4961.3      .1       0  5793.1     .05       0
Bank Sta=4955.3,4961.3
XS Rating Curve= 0 ,0
Exp/Cntr=0.3,0.1

Type RM Length L Ch R = 1 ,4852    ,203,203,203
BEGIN DESCRIPTION:
Mapping XS b9bc8e23
END DESCRIPTION:
XS GIS Cut Line= 2
      2263983.57     13427290.18      2262733.59     13427272.82
#Sta/Elev= 30
    4421  339.58  4466.9  337.48  4516.9  337.63  4690.7  333.05  4716.9  332.93
  4726.9  331.94  4736.9  332.19  4836.9  328.99  4953.9   326.9  4956.6   326.4
  4959.9   326.9  4976.9  327.11  4986.9  328.16  4996.9  327.11  5006.9   328.1
  5021.2  327.31  5056.9  328.47  5086.9  327.45  5096.9  328.63  5106.9   327.3
  5126.9  327.34  5136.9  328.05  5176.9  327.69  5266.9  328.78  5326.9  330.86
  5336.9  330.54  5366.9  332.16  5406.9   332.3    5597  337.09  5671.1  338.26
#Mann= 4 ,-1 , 0
    4421     .08       0  4690.7      .1       0  4953.9     .07       0
  4959.9      .1       0
Bank Sta=4953.9,4959.9
XS Rating Curve= 0 ,0
Exp/Cntr=0.3,0.1

Type RM Length L Ch R = 1 ,4649    ,546,546,546
BEGIN DESCRIPTION:
UNT040 IN SUCR 8.0
END DESCRIPTION:
XS GIS Cut Line= 2
      2263996.64     13427116.57      2262746.61     13427103.55
#Sta/Elev= 30
  4469.4  337.58  4478.3  337.01  4538.3  335.67  4568.3  334.38  4698.3  331.54
  4738.3  330.06  4828.3  328.47  4848.3   327.9  4858.3  327.17  4888.3  326.44
  4938.3   325.8  4958.3  325.25  4978.3  324.18  5018.3  324.31  5035.3  323.48
  5038.1  322.98  5041.3  323.48  5058.3  323.82  5138.4  323.83  5258.4  326.63
  5308.4   327.2  5408.4  330.18  5458.4  331.08  5488.4  332.23  5538.4  332.94
  5588.4  334.34  5658.4  334.99  5688.4  336.42  5698.4  335.87  5719.5  335.96
#Mann= 3 ,-1 , 0
  4469.4     .08       0  5035.3     .07       0  5041.3     .08       0
Bank Sta=5035.3,5041.3
XS Rating Curve= 0 ,0
Exp/Cntr=0.3,0.1

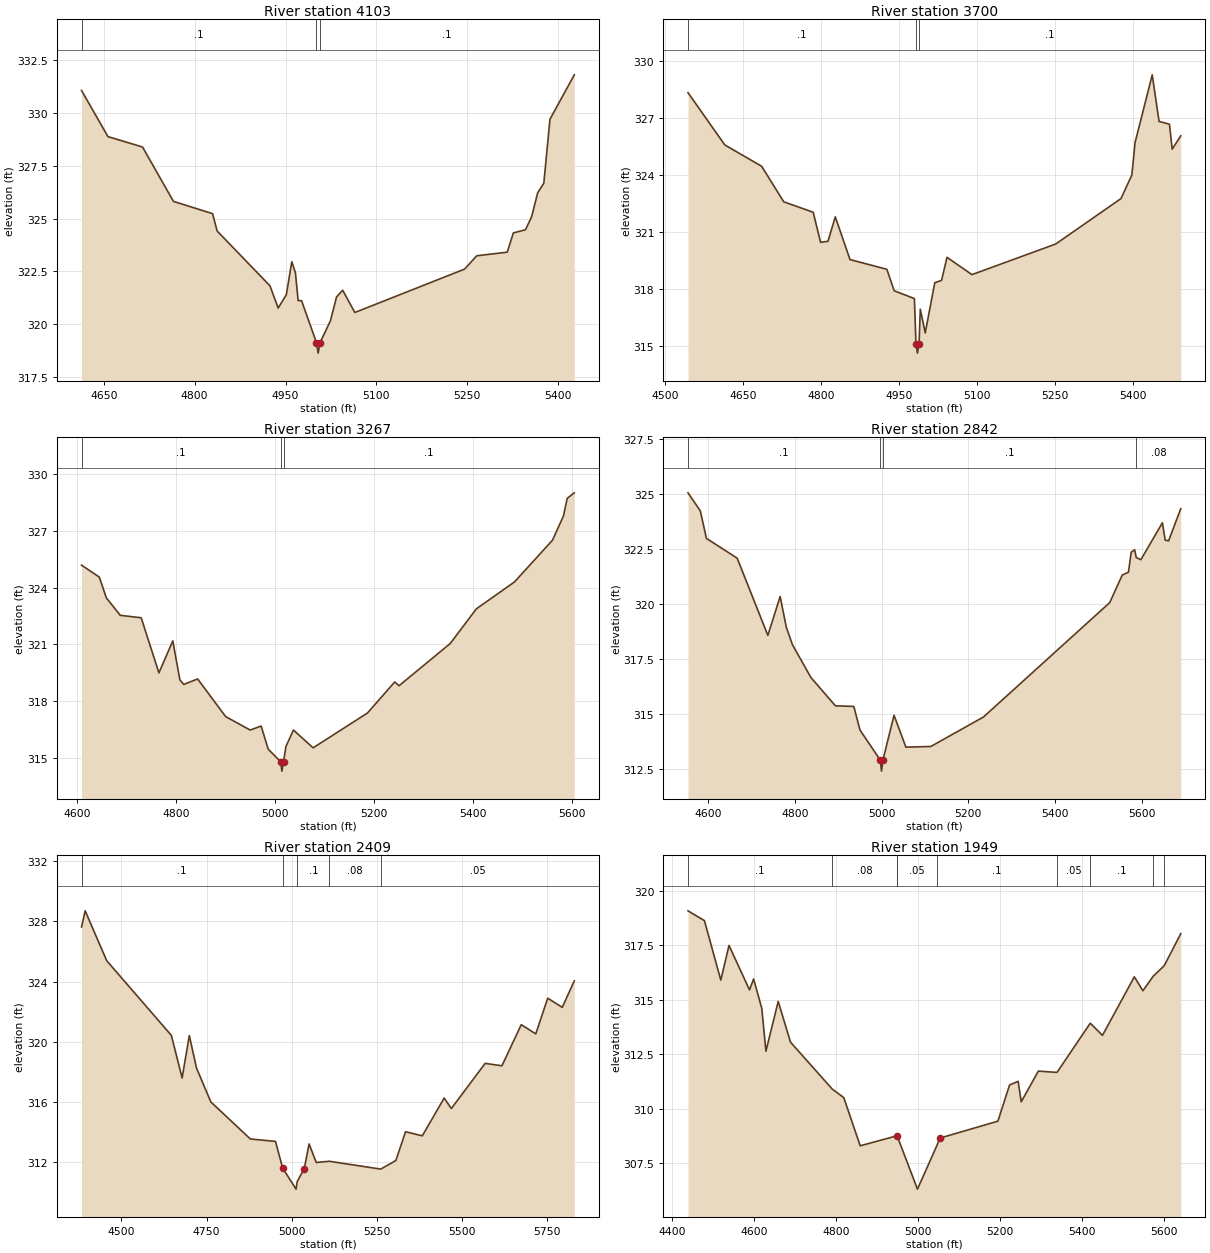
Type RM Length L Ch R = 1 ,4103    ,403,403,403
BEGIN DESCRIPTION:
UNT040 IN SUCR 7.0
END DESCRIPTION:
XS GIS Cut Line= 3
      2263837.71     13426846.85      2263537.72     13426646.85
      2263087.73     13426596.86
#Sta/Elev= 30
  4613.3  331.05  4656.9  328.87  4713.9  328.38    4765  325.81  4829.6  325.23
  4837.1  324.41  4924.3  321.82  4937.8  320.77  4951.3   321.4  4960.3  322.96
  4966.3  322.44  4970.8  321.12  4976.4  321.12    5001  319.14  5003.8  318.64
    5007  319.14  5024.1  320.17  5034.2   321.3  5044.3  321.61  5064.4  320.56
  5245.5  322.61  5265.6  323.24  5315.9  323.41    5326  324.32  5346.1  324.47
  5356.2  325.09  5366.2  326.22  5376.3  326.67  5386.4  329.69  5426.6  331.79
#Mann= 3 ,-1 , 0
  4613.3      .1       0    5001     .07       0    5007      .1       0
Bank Sta=5001,5007
XS Rating Curve= 0 ,0
Exp/Cntr=0.3,0.1

Type RM Length L Ch R = 1 ,3700    ,433,433,433
BEGIN DESCRIPTION:
UNT040 IN SUCR 6.0
END DESCRIPTION:
XS GIS Cut Line= 3
      2263887.69     13426546.82      2263587.72     13426246.85
      2263087.75     13426396.85
#Sta/Elev= 30
  4544.8  328.33  4615.5  325.58  4686.2  324.46  4728.6  322.59  4785.2  322.04
  4799.3  320.46  4813.5  320.51  4827.6   321.8  4855.9  319.55  4926.6  319.04
  4940.7  317.91  4979.5   317.5  4982.5  315.13  4985.3  314.63  4988.5  315.13
  4990.8  316.94  5000.3  315.69  5018.6  318.33  5031.7  318.46  5042.1  319.67
    5090  318.76  5250.9  320.37  5376.2  322.76  5397.1     324  5403.2   325.7
  5436.2  329.27  5449.3  326.82  5469.3  326.67  5474.5  325.36    5491  326.06
#Mann= 3 ,-1 , 0
  4544.8      .1       0  4982.5     .07       0  4988.5      .1       0
Bank Sta=4982.5,4988.5
XS Rating Curve= 0 ,0
Exp/Cntr=0.3,0.1

Type RM Length L Ch R = 1 ,3267    ,425,425,425
BEGIN DESCRIPTION:
UNT040 IN SUCR 5.0
END DESCRIPTION:
XS GIS Cut Line= 3
      2264087.71     13426146.85      2263787.72     13425896.85
      2263237.68     13425646.84
#Sta/Elev= 30
  4609.4  325.19  4645.2  324.56  4659.5  323.46  4687.5  322.54  4729.8  322.41
  4765.6   319.5  4793.6  321.19  4807.9  319.13  4815.7  318.89  4843.7  319.18
  4900.3  317.19  4949.8  316.48  4971.9  316.69  4986.2  315.47  5011.2  314.81
  5013.9  314.31  5017.2  314.81  5021.9  315.61  5037.2  316.48  5076.8  315.54
  5186.6  317.38  5241.6  319.02  5250.3  318.82  5353.6  321.05  5406.3  322.88
  5483.2   324.3  5560.1  326.51  5582.1  327.78  5589.8  328.72  5604.1  329.01
#Mann= 3 ,-1 , 0
  4609.4      .1       0  5011.2     .07       0  5017.2      .1       0
Bank Sta=5011.2,5017.2
XS Rating Curve= 0 ,0
Exp/Cntr=0.3,0.1

Type RM Length L Ch R = 1 ,2842    ,433,433,433
BEGIN DESCRIPTION:
UNT040 IN SUCR 4.0
END DESCRIPTION:
XS GIS Cut Line= 3
      2264387.74     13425896.87      2264087.72     13425596.85
      2263537.74     13425146.87
#Sta/Elev= 30
  4554.3  325.04  4582.6  324.22  4596.7  322.97  4667.5  322.07  4738.2  318.56
  4766.5  320.33  4780.6  318.94  4794.7  318.14  4837.2  316.65  4893.7  315.36
  4936.2  315.33  4950.3  314.26  4997.1  312.89  4999.9  312.39  5003.1  312.89
  5028.8  314.93  5056.1  313.48  5113.5  313.51  5234.8  314.85  5525.6  320.05
  5554.3   321.3  5568.6  321.43  5575.1  322.34    5583  322.45  5586.6   322.1
  5597.3     322  5646.9  323.68  5653.3  322.89  5661.2  322.86  5689.2  324.32
#Mann= 4 ,-1 , 0
  4554.3      .1       0  4997.1     .07       0  5003.1      .1       0
  5586.6     .08       0
Bank Sta=4997.1,5003.1
XS Rating Curve= 0 ,0
Exp/Cntr=0.3,0.1

Type RM Length L Ch R = 1 ,2409    ,460,460,460
BEGIN DESCRIPTION:
UNT040 IN SUCR 3.0
END DESCRIPTION:
XS GIS Cut Line= 3
      2264587.73     13425896.89      2264387.72     13425296.85
      2263787.74     13424746.88
#Sta/Elev= 30
  4382.9  327.63  4393.5   328.7  4456.7  325.39  4646.5  320.43  4678.1   317.6
  4699.2  320.42  4720.2  318.27  4762.4  316.01  4878.4  313.55  4952.1  313.39
  4973.2  311.62  5012.5  310.22  5015.8  310.72  5036.7  311.58  5050.8  313.22
  5071.8  311.99  5110.2  312.07  5261.1  311.55  5305.5  312.12  5333.9  314.03
  5383.2  313.76  5447.3  316.27  5468.3  315.57  5567.6  318.57  5616.9  318.41
  5673.6  321.14  5716.2  320.53  5751.3   322.9  5793.9  322.29  5829.3  324.05
#Mann= 5 ,-1 , 0
  4382.9      .1       0  4973.2     .07       0  5015.8      .1       0
  5110.2     .08       0  5261.1     .05       0
Bank Sta=4973.2,5036.7
XS Rating Curve= 0 ,0
Exp/Cntr=0.3,0.1

Type RM Length L Ch R = 1 ,1949    ,355,355,355
BEGIN DESCRIPTION:
UNT040 IN SUCR 2.0
END DESCRIPTION:
XS GIS Cut Line= 3
      2264737.72     13425596.82      2264737.72     13424996.85
      2264287.75     13424596.88
#Sta/Elev= 30
  4439.7  319.09  4479.7  318.64  4519.7  315.91  4539.7   317.5  4589.7  315.46
  4599.7  315.96  4619.7  314.61  4629.7  312.64  4659.7  314.93  4689.7  313.06
  4791.2  310.91  4819.7  310.51  4859.7   308.3  4949.7  308.76  4999.4  306.31
  5046.8  308.31  5053.5  308.65  5195.6  309.43    5224  311.09    5245  311.26
  5252.5  310.32  5294.3  311.73  5339.8  311.67  5420.9  313.93  5450.7  313.37
  5528.4  316.06  5549.3  315.42  5574.6  316.09  5601.3  316.57  5641.7  318.04
#Mann= 9 ,-1 , 0
  4439.7      .1       0  4791.2     .08       0  4949.7      .1       0
  4949.7     .05       0  5046.8      .1       0  5339.8     .05       0
  5420.9      .1       0  5574.6     .05       0  5601.3      .1       0
Bank Sta=4949.7,5053.5
XS Rating Curve= 0 ,0
Exp/Cntr=0.3,0.1

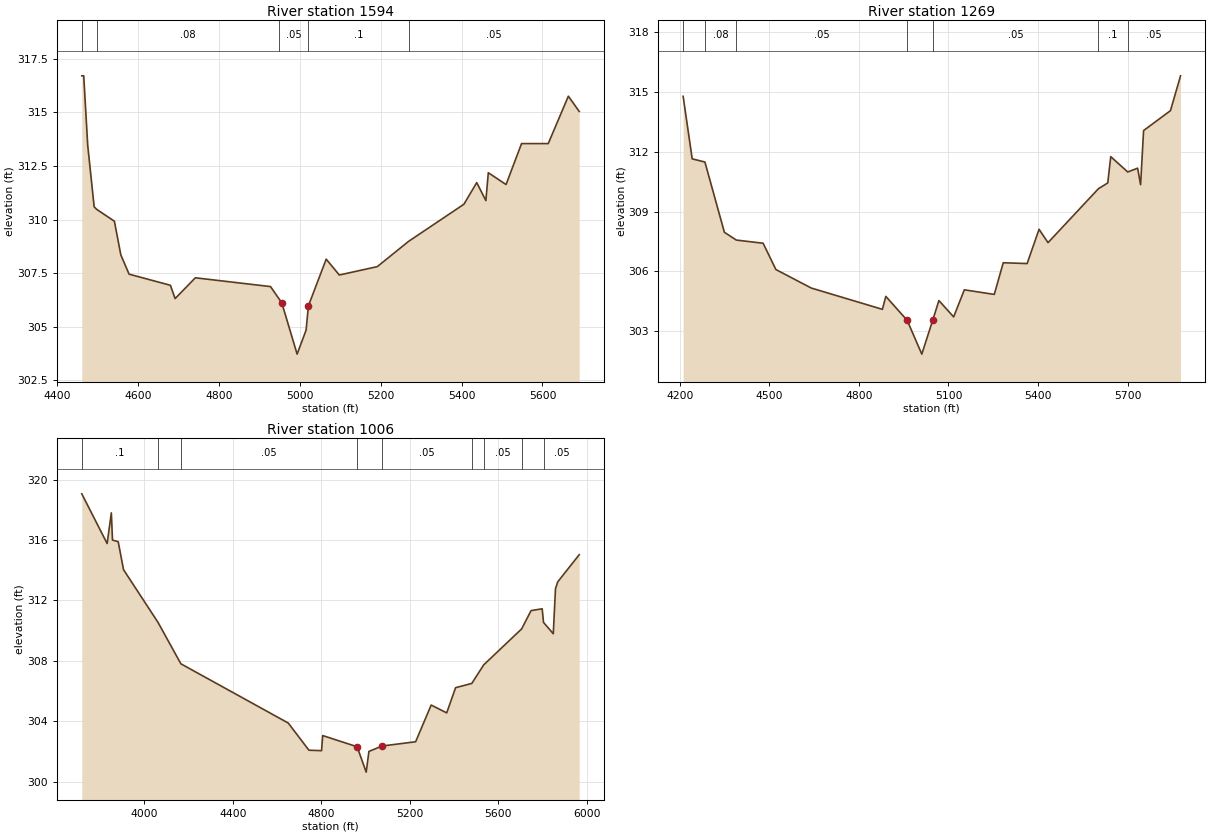
Type RM Length L Ch R = 1 ,1594    ,325,325,325
BEGIN DESCRIPTION:
Mapping XS c878
END DESCRIPTION:
XS GIS Cut Line= 3
      2265056.36     13425291.29       2265139.7     13424891.97
      2264414.02     13424506.56
#Sta/Elev= 30
  4461.2  316.71    4466  316.71  4475.9  313.46  4491.8   310.6  4498.2  310.48
  4541.8  309.93  4557.7  308.36  4578.1  307.46  4680.3  306.94  4691.9  306.32
  4741.9  307.29  4927.8  306.88  4949.8  306.28  4955.5  306.13  4993.5  303.73
  5015.7  304.85  5021.4  305.98  5065.4  308.16  5097.8  307.42  5191.6  307.81
  5269.1  308.99  5405.8  310.72  5437.5  311.73  5460.1  310.89  5466.1  312.19
    5510  311.64  5548.3  313.55  5614.3  313.55    5664  315.76  5690.8  315.05
#Mann= 5 ,-1 , 0
  4461.2      .1       0  4498.2     .08       0  4949.8     .05       0
  5021.4      .1       0  5269.1     .05       0
Bank Sta=4955.5,5021.4
XS Rating Curve= 0 ,0
Exp/Cntr=0.3,0.1

Type RM Length L Ch R = 1 ,1269    ,263,263,263
BEGIN DESCRIPTION:
Mapping XS c878a8bf
END DESCRIPTION:
XS GIS Cut Line= 4
      2265114.54     13425325.09      2265364.53     13424703.61
      2265124.94     13424498.74      2264443.89     13424491.44
#Sta/Elev= 30
  4211.1  314.79  4241.5  311.65  4284.1  311.49  4349.3  307.96  4389.2  307.57
  4479.1  307.41  4521.8  306.09  4640.3  305.16  4878.6  304.09  4890.1  304.74
  4961.5  303.54  5010.6  301.84  5047.1  303.54  5067.9  304.53  5117.3  303.71
  5153.1  305.07  5253.4  304.84  5283.4  306.43  5363.4  306.39  5403.4  308.11
  5433.4  307.44  5602.3  310.15  5633.5  310.44  5643.5  311.76  5700.5  310.99
  5733.5  311.18  5743.5  310.35  5753.5  313.07  5843.5  314.07  5877.3  315.82
#Mann= 7 ,-1 , 0
  4211.1      .1       0  4284.1     .08       0  4389.2     .05       0
  4961.5    .035       0  5047.1     .05       0  5602.3      .1       0
  5700.5     .05       0
Bank Sta=4961.5,5047.1
XS Rating Curve= 0 ,0
Exp/Cntr=0.3,0.1

Type RM Length L Ch R = 1 ,1006    ,0,0,0
BEGIN DESCRIPTION:
UNT040 IN SUCR 1.0
END DESCRIPTION:
XS GIS Cut Line= 4
      2265098.06     13425585.17        2265493.     13424443.19
       2265329.8     13424401.52       2264460.9     13424475.15
#Sta/Elev= 30
  3716.8  319.06  3831.4  315.77  3850.4   317.8  3855.7     316  3881.5  315.89
  3905.5  314.04  4061.5  310.55  4164.8  307.81  4650.2  303.89  4743.7  302.09
  4800.8  302.06    4806  303.06  4961.6  302.32  5002.6  300.64  5014.9  302.01
  5075.1  302.37  5226.1  302.65  5296.4  305.08  5366.6  304.56  5406.8  306.23
  5479.9  306.51  5533.9  307.74  5705.4  310.12    5748  311.33  5798.2  311.45
  5804.3  310.55  5848.4   309.8  5858.4  312.78  5868.4  313.23  5965.6  315.03
#Mann= 9 ,-1 , 0
  3716.8      .1       0  4061.5     .08       0  4164.8     .05       0
  4961.6     .03       0  5075.1     .05       0  5479.9      .1       0
  5533.9     .05       0  5705.4      .1       0  5804.3     .05       0
Bank Sta=4961.6,5075.1
XS Rating Curve= 0 ,0
Exp/Cntr=0.3,0.1

Chan Stop Cuts=-1
Use User Specified Reach Order=0
Composite Channel Slope=5