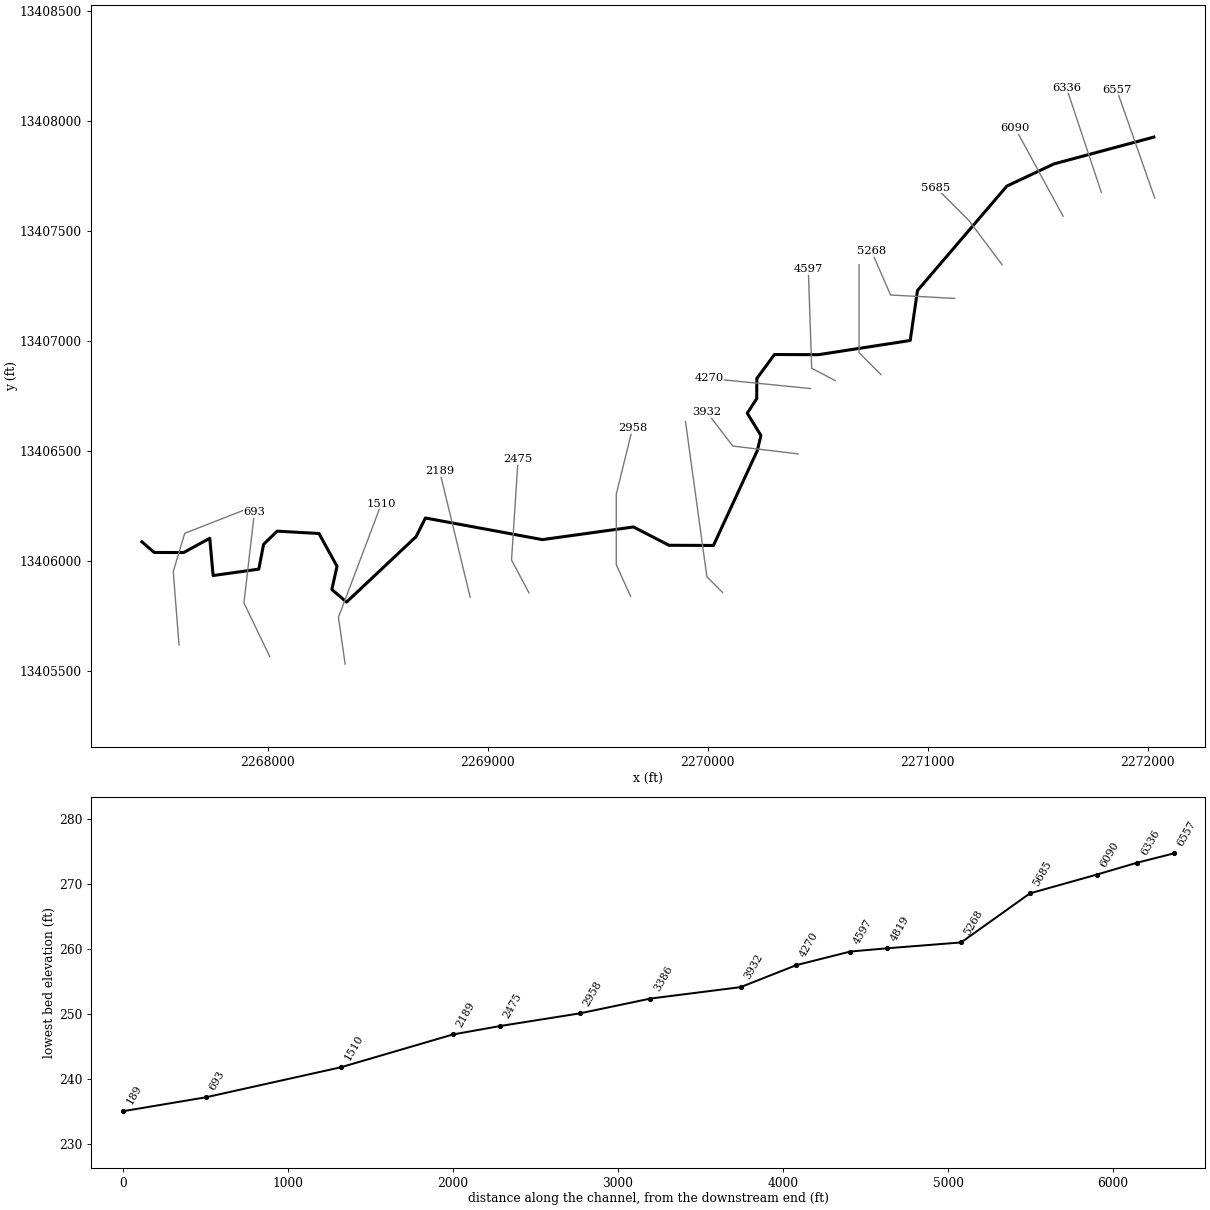
--- UNT041 IN SUCR.prj (project) ---

Proj Title=UNT041 IN SUCR Base Level Engineering
Current Plan=p01
Default Exp/Contr=0.3,0.1
English Units
Geom File=g01
Flow File=f01
Plan File=p01
BEGIN DESCRIPTION:
UNT041 IN SUCR
END DESCRIPTION:

--- UNT041 IN SUCR.p01 (plan) ---

Plan Title=Multiple Run
Short Identifier=Multiple
Geom File=g01
Flow File=f01
Subcritical Flow
K Sum by GR= 0
Std Step Tol= 0.01
Critical Tol= 0.01
Num of Std Step Trials= 20
Max Error Tol= 0.3
Flow Tol Ratio= 0.001
Split Flow NTrial= 30
Split Flow Tol= 0.02
Split Flow Ratio= 0.02
Log Output Level= 0
Friction Slope Method= 1
Unsteady Friction Slope Method= 2
Unsteady Bridges Friction Slope Method= 1
Parabolic Critical Depth
Global Vel Dist=  1 , 1 , 1
Global Log Level= 0
CheckData=True
Encroach Param= -1, 0, 0, 0
BEGIN DESCRIPTION:
Multiple Run
END DESCRIPTION:

--- UNT041 IN SUCR.f01 (steady flow) ---

Flow Title=Multiple
Number of Profiles=7
Profile Names=10-year,25-year,50-year,1pct_min,100-year,1pct_plu,500-year
River Rch & RM= UNT041 IN SUCR,Reach-1,6557
     263     363     446     402     544     736     824
Boundary for River Rch & Prof#=UNT041 IN SUCR,Reach-1,1
Up Type=0
Dn Type=3
Dn Slope=0.005
Boundary for River Rch & Prof#=UNT041 IN SUCR,Reach-1,2
Up Type=0
Dn Type=3
Dn Slope=0.005
Boundary for River Rch & Prof#=UNT041 IN SUCR,Reach-1,3
Up Type=0
Dn Type=3
Dn Slope=0.005
Boundary for River Rch & Prof#=UNT041 IN SUCR,Reach-1,4
Up Type=0
Dn Type=3
Dn Slope=0.005
Boundary for River Rch & Prof#=UNT041 IN SUCR,Reach-1,5
Up Type=0
Dn Type=3
Dn Slope=0.005
Boundary for River Rch & Prof#=UNT041 IN SUCR,Reach-1,6
Up Type=0
Dn Type=3
Dn Slope=0.005
Boundary for River Rch & Prof#=UNT041 IN SUCR,Reach-1,7
Up Type=0
Dn Type=3
Dn Slope=0.005

--- UNT041 IN SUCR.g01 (geometry) ---

Geom Title=Existing Conditions

River Reach=UNT041 IN SUCR,Reach-1
Reach XY= 30
      2272027.72     13407926.85      2271573.63     13407804.92
      2271359.64     13407704.16      2270953.22     13407229.18
      2270920.26     13407002.21      2270502.83     13406937.63
      2270303.23     13406938.45      2270222.93     13406829.35
      2270222.49     13406737.90      2270179.46     13406671.61
      2270241.41     13406570.54      2270225.45     13406502.26
      2270025.76     13406070.42      2269823.40     13406071.35
      2269662.29     13406154.51      2269247.84     13406097.00
      2268716.25     13406195.33      2268674.07     13406110.66
      2268358.01     13405813.01      2268291.05     13405870.19
      2268314.62     13405975.77      2268232.52     13406124.80
      2268042.29     13406135.48      2267980.74     13406075.64
      2267959.01     13405962.89      2267751.29     13405933.71
      2267736.16     13406103.17      2267617.51     13406038.26
      2267483.55     13406038.59      2267427.72     13406086.85

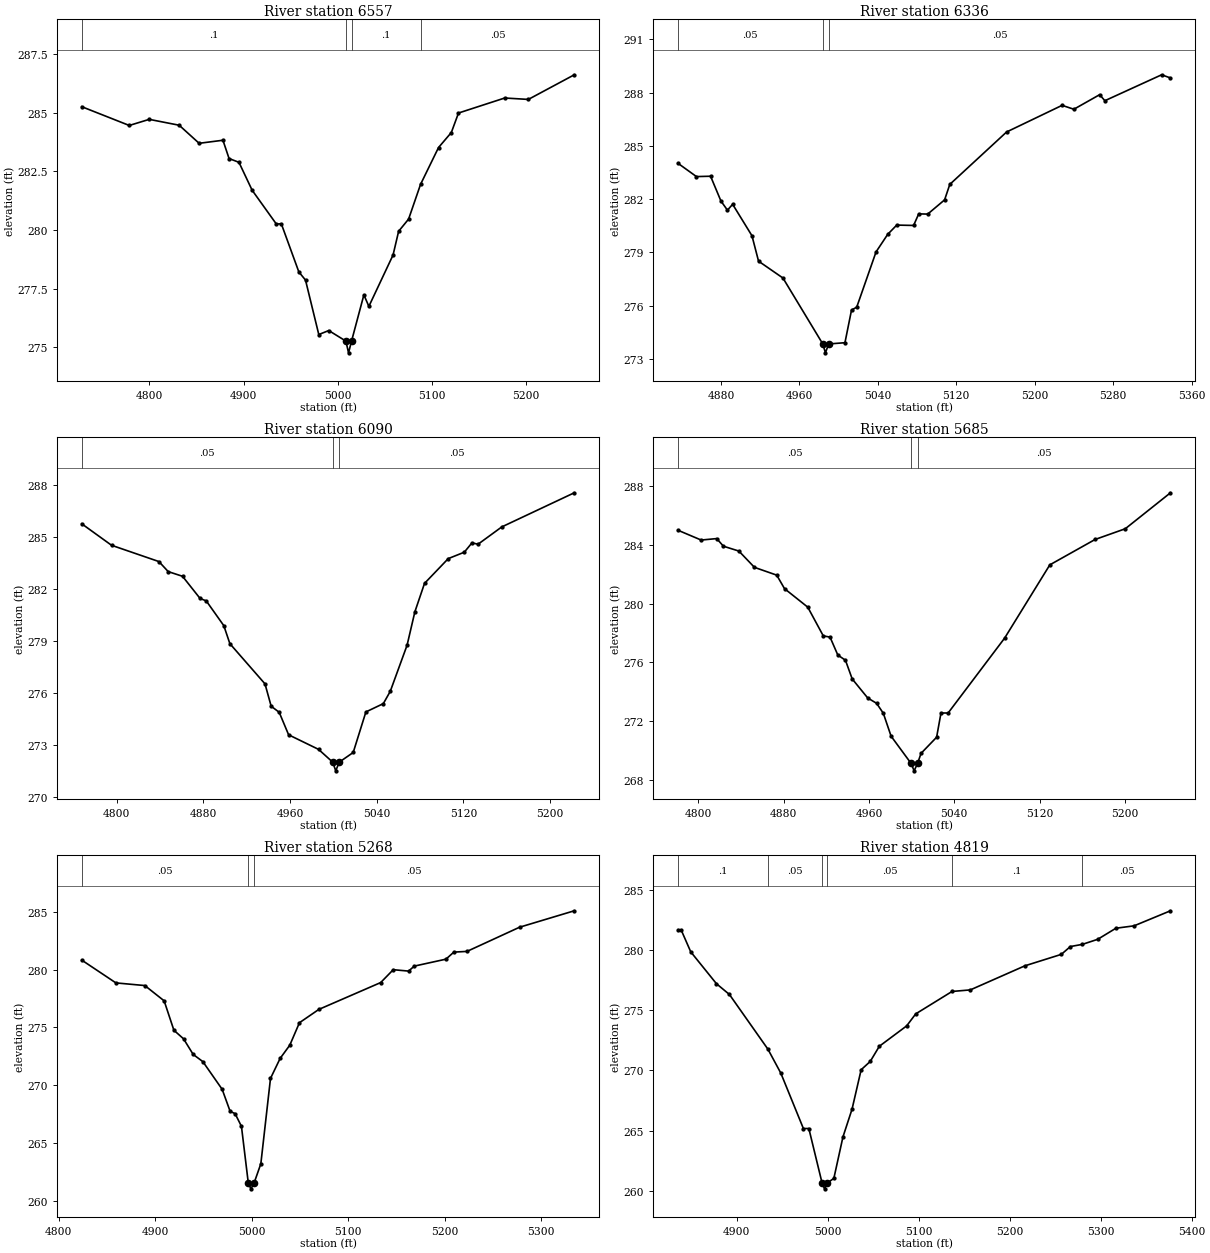
Type RM Length L Ch R = 1,6557,221,221,221
BEGIN DESCRIPTION:
UNT041 IN SUCR 10.0
END DESCRIPTION:
XS GIS Cut Line= 2
      2272031.98     13407649.23      2271858.75     13408142.92
#Sta/Elev= 30
  4728.1  285.26  4778.6  284.46  4799.8  284.72  4831.6  284.47  4852.8  283.70
  4878.1  283.83  4884.6  283.05  4895.1  282.89  4909.1  281.70  4934.8  280.26
  4940.1  280.27  4958.7  278.22  4965.8  277.87  4979.9  275.55  4990.5  275.72
  5008.7  275.27  5011.5  274.77  5014.7  275.27  5027.8  277.24  5033.1  276.75
  5058.8  278.94  5064.7  279.95  5075.3  280.47  5088.0  281.95  5107.1  283.52
  5120.7  284.16  5128.3  284.99  5177.4  285.63  5202.5  285.57  5251.3  286.62
#Mann=4,-1,0
  4728.1     0.1       0  5008.7    0.07       0  5014.7     0.1       0
  5088.0    0.05       0
Bank Sta=5008.7,5014.7
Exp/Cntr=0.3,0.1

Type RM Length L Ch R = 1,6336,246,246,246
BEGIN DESCRIPTION:
Mapping XS 32342dff
END DESCRIPTION:
XS GIS Cut Line= 2
      2271789.14     13407675.25      2271630.33     13408151.68
#Sta/Elev= 30
  4836.2  284.02  4855.1  283.27  4869.5  283.29  4880.1  281.89  4886.7  281.38
  4892.0  281.71  4911.7  279.94  4918.4  278.51  4943.3  277.56  4983.9  273.85
  4986.6  273.35  4989.9  273.85  5006.5  273.92  5013.2  275.76  5018.5  275.92
  5038.2  279.03  5050.1  280.02  5059.3  280.54  5076.5  280.52  5081.7  281.17
  5090.9  281.16  5108.1  281.96  5113.4  282.83  5171.3  285.78  5227.9  287.28
  5239.9  287.06  5266.2  287.88  5271.5  287.54  5329.4  289.00  5338.4  288.82
#Mann=3,-1,0
  4836.2    0.05       0  4983.9   0.035       0  4989.9    0.05       0
Bank Sta=4983.9,4989.9
Exp/Cntr=0.3,0.1

Type RM Length L Ch R = 1,6090,405,405,405
BEGIN DESCRIPTION:
Mapping XS cf0f085b
END DESCRIPTION:
XS GIS Cut Line= 2
      2271615.32     13407566.74      2271398.29     13407966.07
#Sta/Elev= 30
  4767.9  285.77  4795.4  284.53  4839.1  283.59  4847.7  283.01  4860.9  282.74
  4877.1  281.46  4882.8  281.32  4899.0  279.89  4904.6  278.85  4937.0  276.53
  4942.7  275.24  4950.1  274.89  4958.8  273.59  4986.4  272.75  4999.5  272.01
  5002.3  271.51  5005.5  272.01  5018.4  272.57  5030.1  274.91  5046.2  275.39
  5052.6  276.10  5068.1  278.76  5075.3  280.69  5084.2  282.33  5106.1  283.76
  5120.9  284.13  5128.0  284.67  5133.6  284.59  5155.5  285.59  5222.4  287.56
#Mann=3,-1,0
  4767.9    0.05       0  4999.5   0.035       0  5005.5    0.05       0
Bank Sta=4999.5,5005.5
Exp/Cntr=0.3,0.1

Type RM Length L Ch R = 1,5685,417,417,417
BEGIN DESCRIPTION:
UNT041 IN SUCR 9.0
END DESCRIPTION:
XS GIS Cut Line= 3
      2271337.69     13407346.89      2271187.72     13407546.85
      2271037.71     13407696.87
#Sta/Elev= 30
  4780.7  285.01  4802.5  284.34  4817.1  284.44  4823.4  283.92  4837.9  283.59
  4852.5  282.48  4873.4  281.95  4880.7  281.03  4902.5  279.77  4917.1  277.81
  4923.4  277.73  4930.7  276.51  4937.9  276.15  4944.2  274.88  4958.8  273.58
  4967.1  273.22  4973.4  272.54  4980.7  270.98  4999.5  269.12  5002.3  268.62
  5005.5  269.12  5008.8  269.81  5023.4  270.91  5027.5  272.56  5034.2  272.56
  5087.2  277.66  5129.6  282.65  5172.1  284.38  5200.4  285.11  5242.8  287.56
#Mann=3,-1,0
  4780.7    0.05       0  4999.5   0.035       0  5005.5    0.05       0
Bank Sta=4999.5,5005.5
Exp/Cntr=0.3,0.1

Type RM Length L Ch R = 1,5268,449,449,449
BEGIN DESCRIPTION:
UNT041 IN SUCR 8.0
END DESCRIPTION:
XS GIS Cut Line= 3
      2271123.04     13407193.59      2270831.04     13407208.96
      2270743.93     13407408.80
#Sta/Elev= 30
  4823.8  280.82  4859.2  278.85  4889.2  278.62  4909.2  277.30  4919.3  274.76
  4929.3  274.02  4939.3  272.67  4949.3  272.05  4969.3  269.66  4977.6  267.75
  4982.7  267.56  4989.3  266.46  4996.4  261.56  4999.1  261.06  5002.4  261.56
  5009.4  263.23  5019.4  270.60  5029.4  272.33  5039.4  273.47  5049.4  275.41
  5069.5  276.56  5133.6  278.88  5146.6  279.99  5162.5  279.87  5168.4  280.30
  5201.2  280.90  5209.4  281.51  5223.0  281.57  5277.5  283.66  5334.2  285.08
#Mann=3,-1,0
  4823.8    0.05       0  4996.4   0.035       0  5002.4    0.05       0
Bank Sta=4996.4,5002.4
Exp/Cntr=0.3,0.1

Type RM Length L Ch R = 1,4819,222,222,222
BEGIN DESCRIPTION:
UNT041 IN SUCR 7.0
END DESCRIPTION:
XS GIS Cut Line= 3
      2270787.72     13406846.86      2270687.72     13406946.85
      2270687.72     13407346.84
#Sta/Elev= 30
  4835.3  281.67  4838.8  281.67  4849.4  279.84  4877.7  277.19  4891.9  276.30
  4934.2  271.76  4948.4  269.77  4973.2  265.17  4979.2  265.17  4993.7  260.66
  4996.5  260.16  4999.7  260.66  5006.7  261.03  5016.7  264.47  5026.7  266.78
  5036.7  270.05  5046.7  270.74  5056.7  272.00  5086.7  273.69  5096.7  274.69
  5136.6  276.55  5156.7  276.68  5216.7  278.68  5256.7  279.63  5266.7  280.28
  5279.8  280.46  5296.7  280.88  5316.7  281.80  5336.7  282.00  5376.7  283.25
#Mann=6,-1,0
  4835.3     0.1       0  4934.2    0.05       0  4993.7   0.035       0
  4999.7    0.05       0  5136.6     0.1       0  5279.8    0.05       0
Bank Sta=4993.7,4999.7
Exp/Cntr=0.3,0.1

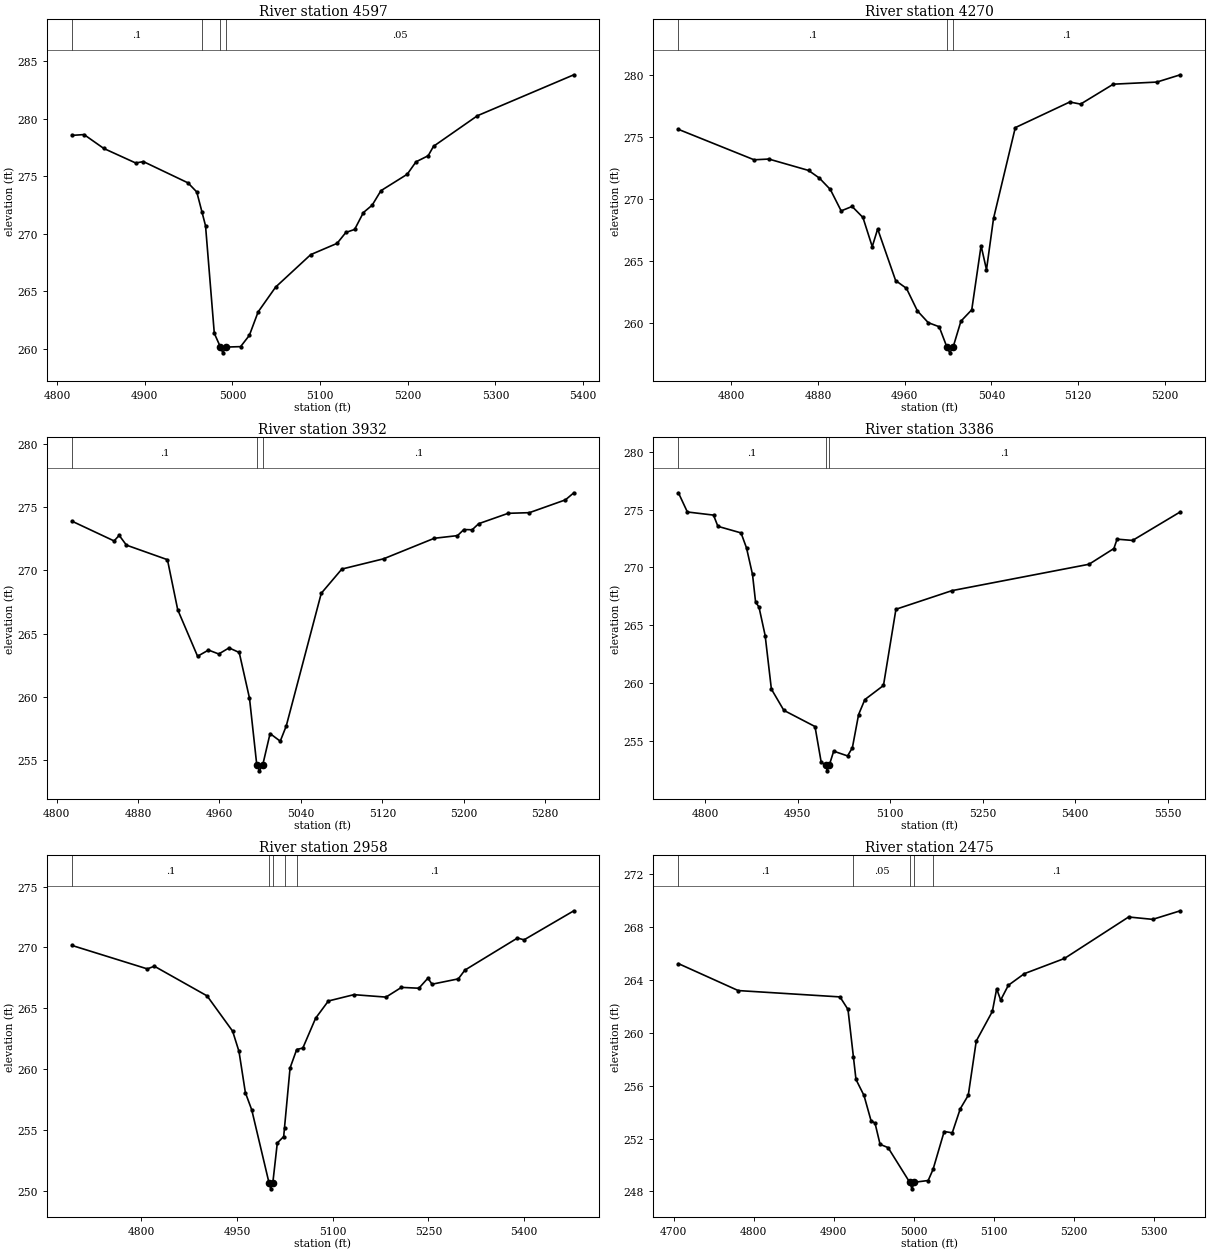
Type RM Length L Ch R = 1,4597,327,327,327
BEGIN DESCRIPTION:
Mapping XS bd65dfd5
END DESCRIPTION:
XS GIS Cut Line= 3
      2270579.96     13406819.58      2270472.39     13406875.93
      2270457.02     13407326.84
#Sta/Elev= 30
  4816.9  278.57  4830.7  278.64  4853.3  277.43  4889.6  276.17  4898.4  276.29
  4949.3  274.44  4959.3  273.65  4965.3  271.89  4969.3  270.71  4979.3  261.36
  4986.3  260.16  4989.0  259.66  4992.3  260.16  5009.3  260.20  5019.3  261.18
  5029.3  263.22  5049.3  265.38  5089.3  268.20  5119.4  269.18  5129.4  270.13
  5139.4  270.39  5149.4  271.86  5159.4  272.50  5169.4  273.76  5199.4  275.19
  5209.4  276.27  5223.3  276.80  5229.4  277.62  5279.5  280.28  5389.5  283.84
#Mann=4,-1,0
  4816.9     0.1       0  4965.3    0.05       0  4986.3   0.035       0
  4992.3    0.05       0
Bank Sta=4986.3,4992.3
Exp/Cntr=0.3,0.1

Type RM Length L Ch R = 1,4270,338,338,338
BEGIN DESCRIPTION:
UNT041 IN SUCR 6.0
END DESCRIPTION:
XS GIS Cut Line= 2
      2270467.30     13406783.70      2270006.10     13406829.82
#Sta/Elev= 30
  4751.0  275.63  4820.9  273.17  4834.5  273.23  4871.2  272.31  4881.2  271.69
  4891.3  270.77  4901.3  269.04  4911.4  269.40  4921.4  268.51  4930.0  266.15
  4935.0  267.58  4951.6  263.41  4961.6  262.78  4971.7  260.96  4981.7  260.01
  4991.8  259.68  4998.8  258.07  5001.6  257.57  5004.8  258.07  5011.9  260.13
  5021.9  261.05  5030.5  266.23  5035.5  264.29  5042.0  268.43  5062.1  275.77
  5112.4  277.84  5122.4  277.67  5152.6  279.28  5192.8  279.45  5214.5  280.04
#Mann=3,-1,0
  4751.0     0.1       0  4998.8    0.07       0  5004.8     0.1       0
Bank Sta=4998.8,5004.8
Exp/Cntr=0.3,0.1

Type RM Length L Ch R = 1,3932,546,546,546
BEGIN DESCRIPTION:
UNT041 IN SUCR 5.0
END DESCRIPTION:
XS GIS Cut Line= 3
      2270410.87     13406486.54      2270113.74     13406522.40
      2269995.88     13406676.13
#Sta/Elev= 30
  4815.1  273.88  4856.5  272.32  4861.5  272.76  4868.6  271.99  4908.9  270.84
  4919.0  266.89  4938.5  263.22  4949.2  263.71  4959.3  263.40  4969.4  263.88
  4979.4  263.52  4989.5  259.91  4996.6  254.68  4999.3  254.18  5002.6  254.68
  5009.7  257.12  5019.7  256.52  5025.6  257.72  5060.0  268.19  5080.2  270.10
  5121.2  270.91  5171.0  272.53  5193.8  272.74  5200.1  273.22  5208.2  273.20
  5214.6  273.68  5243.6  274.50  5264.4  274.55  5299.8  275.56  5308.1  276.12
#Mann=3,-1,0
  4815.1     0.1       0  4996.6    0.07       0  5002.6     0.1       0
Bank Sta=4996.6,5002.6
Exp/Cntr=0.3,0.1

Type RM Length L Ch R = 1,3386,428,428,428
BEGIN DESCRIPTION:
UNT041 IN SUCR 4.0
END DESCRIPTION:
XS GIS Cut Line= 3
      2270067.66     13405856.30      2269995.89     13405928.06
      2269898.77     13406633.52
#Sta/Elev= 30
  4756.7  276.46  4771.2  274.80  4813.6  274.53  4820.7  273.56  4858.2  272.99
  4867.1  271.69  4876.8  269.40  4881.8  267.01  4887.3  266.58  4897.3  264.12
  4907.4  259.49  4927.6  257.65  4978.1  256.25  4988.2  253.15  4995.3  252.92
  4998.0  252.42  5001.3  252.92  5008.4  254.12  5030.9  253.71  5038.7  254.42
  5048.8  257.29  5058.9  258.58  5089.1  259.80  5109.3  266.39  5200.2  268.00
  5422.3  270.28  5462.6  271.64  5467.8  272.45  5492.9  272.34  5570.3  274.81
#Mann=3,-1,0
  4756.7     0.1       0  4995.3    0.07       0  5001.3     0.1       0
Bank Sta=4995.3,5001.3
Exp/Cntr=0.3,0.1

Type RM Length L Ch R = 1,2958,483,483,483
BEGIN DESCRIPTION:
UNT041 IN SUCR 3.0
END DESCRIPTION:
XS GIS Cut Line= 4
      2269649.18     13405839.30      2269584.07     13405982.54
      2269584.07     13406303.72      2269657.69     13406602.56
#Sta/Elev= 30
  4691.5  270.16  4809.6  268.23  4820.6  268.45  4903.2  266.01  4943.2  263.11
  4953.2  261.44  4963.2  258.05  4973.2  256.63  5000.2  250.64  5002.9  250.14
  5006.2  250.64  5013.2  253.91  5023.2  254.44  5024.5  255.17  5033.2  260.08
  5043.6  261.60  5053.2  261.72  5073.2  264.17  5093.2  265.59  5133.2  266.11
  5183.5  265.91  5207.7  266.71  5235.0  266.64  5249.2  267.47  5255.6  266.97
  5296.8  267.41  5307.1  268.13  5389.5  270.77  5399.8  270.62  5477.8  273.01
#Mann=5,-1,0
  4691.5     0.1       0  5000.2    0.07       0  5006.2     0.1       0
  5024.5    0.05       0  5043.6     0.1       0
Bank Sta=5000.2,5006.2
Exp/Cntr=0.3,0.1

Type RM Length L Ch R = 1,2475,286,286,286
BEGIN DESCRIPTION:
UNT041 IN SUCR 2.0
END DESCRIPTION:
XS GIS Cut Line= 3
      2269187.33     13405854.95      2269107.81     13406004.07
      2269137.63     13406461.30
#Sta/Elev= 30
  4705.9  265.24  4780.6  263.20  4907.8  262.72  4917.8  261.77  4924.6  258.17
  4927.8  256.47  4937.8  255.26  4946.6  253.35  4951.6  253.16  4957.9  251.56
  4967.9  251.31  4994.9  248.69  4997.7  248.19  5000.9  248.69  5018.0  248.82
  5024.1  249.66  5038.0  252.53  5048.1  252.43  5058.1  254.25  5068.1  255.27
  5078.1  259.38  5098.2  261.62  5103.6  263.33  5108.6  262.48  5118.2  263.60
  5138.2  264.48  5188.3  265.63  5268.5  268.77  5298.6  268.59  5333.1  269.24
#Mann=5,-1,0
  4705.9     0.1       0  4924.6    0.05       0  4994.9   0.035       0
  5000.9    0.05       0  5024.1     0.1       0
Bank Sta=4994.9,5000.9
Exp/Cntr=0.3,0.1

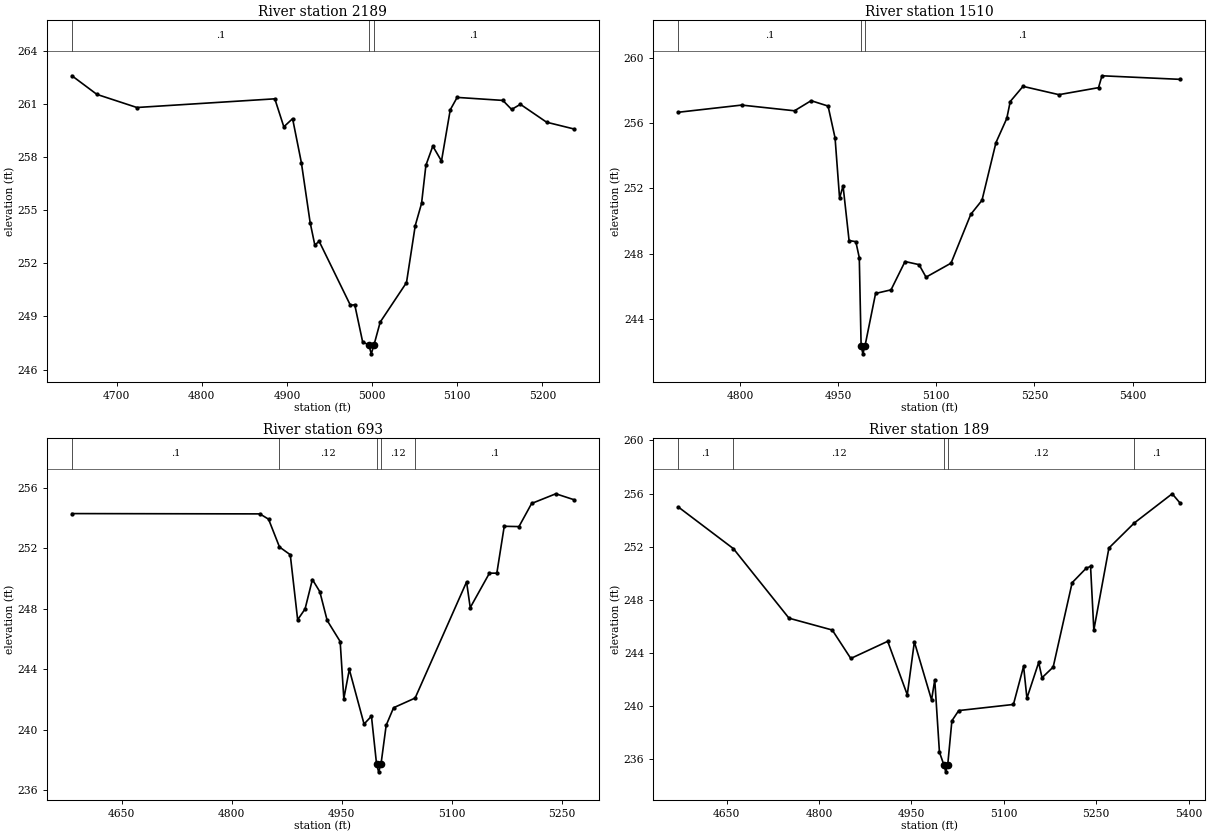
Type RM Length L Ch R = 1,2189,679,679,679
BEGIN DESCRIPTION:
Mapping XS fb8fc3c2
END DESCRIPTION:
XS GIS Cut Line= 2
      2268920.01     13405834.93      2268781.10     13406407.93
#Sta/Elev= 30
  4647.4  262.58  4676.7  261.53  4723.7  260.79  4885.7  261.28  4896.3  259.70
  4906.6  260.16  4916.9  257.68  4927.2  254.30  4932.7  253.03  4937.8  253.24
  4974.5  249.63  4979.6  249.66  4988.9  247.56  4996.2  247.39  4999.0  246.89
  5002.2  247.39  5009.5  248.68  5040.4  250.91  5050.7  254.13  5058.1  255.38
  5063.2  257.53  5071.3  258.61  5081.5  257.77  5091.8  260.66  5099.9  261.36
  5153.6  261.19  5163.9  260.68  5174.2  260.97  5205.0  259.96  5237.0  259.58
#Mann=3,-1,0
  4647.4     0.1       0  4996.2    0.07       0  5002.2     0.1       0
Bank Sta=4996.2,5002.2
Exp/Cntr=0.3,0.1

Type RM Length L Ch R = 1,1510,817,817,817
BEGIN DESCRIPTION:
Mapping XS 875a6854
END DESCRIPTION:
XS GIS Cut Line= 3
      2268351.42     13405531.20      2268321.05     13405743.83
      2268516.37     13406260.35
#Sta/Elev= 30
  4705.9  256.68  4802.5  257.12  4883.3  256.77  4908.7  257.39  4934.6  257.06
  4945.3  255.10  4952.2  251.40  4957.5  252.16  4966.7  248.80  4977.0  248.73
  4982.3  247.75  4985.1  242.34  4987.8  241.84  4991.1  242.34  5007.2  245.55
  5030.8  245.77  5052.2  247.51  5073.6  247.32  5084.3  246.55  5122.5  247.41
  5152.7  250.41  5169.8  251.27  5191.2  254.82  5207.7  256.30  5213.0  257.34
  5232.5  258.27  5287.4  257.76  5347.9  258.19  5353.2  258.92  5472.9  258.70
#Mann=3,-1,0
  4705.9     0.1       0  4985.1    0.07       0  4991.1     0.1       0
Bank Sta=4985.1,4991.1
Exp/Cntr=0.3,0.1

Type RM Length L Ch R = 1,693,504,504,504
BEGIN DESCRIPTION:
Mapping XS 491b31be
END DESCRIPTION:
XS GIS Cut Line= 3
      2268008.54     13405565.89      2267891.36     13405808.93
      2267939.10     13406221.26
#Sta/Elev= 30
  4581.9  254.30  4838.3  254.28  4850.2  253.93  4865.1  252.09  4879.8  251.58
  4889.9  247.28  4900.0  247.99  4910.0  249.94  4920.1  249.14  4930.2  247.23
  4947.9  245.84  4952.9  242.06  4960.4  243.99  4980.5  240.38  4990.6  240.90
  4997.6  237.72  5000.4  237.22  5003.6  237.72  5010.7  240.30  5020.8  241.46
  5050.2  242.10  5120.4  249.78  5125.4  248.08  5151.6  250.36  5161.7  250.36
  5171.8  253.46  5191.9  253.44  5209.2  254.97  5242.2  255.61  5266.8  255.22
#Mann=5,-1,0
  4581.9     0.1       0  4865.1    0.12       0  4997.6    0.07       0
  5003.6    0.12       0  5050.2     0.1       0
Bank Sta=4997.6,5003.6
Exp/Cntr=0.3,0.1

Type RM Length L Ch R = 1,189,0,0,0
BEGIN DESCRIPTION:
UNT041 IN SUCR 1.0
END DESCRIPTION:
XS GIS Cut Line= 4
      2267596.22     13405617.92      2267570.18     13405952.16
      2267622.26     13406125.77      2267900.02     13406234.27
#Sta/Elev= 30
  4571.8  254.99  4661.1  251.86  4751.3  246.63  4821.5  245.74  4851.6  243.60
  4911.5  244.89  4943.3  240.87  4954.8  244.85  4982.7  240.48  4987.9  241.99
  4995.5  236.55  5002.9  235.57  5005.7  235.07  5008.9  235.57  5015.7  238.91
  5026.8  239.68  5115.6  240.14  5132.1  243.01  5137.5  240.61  5156.6  243.30
  5162.0  242.15  5180.1  242.95  5210.9  249.30  5233.7  250.39  5240.8  250.53
  5246.1  245.74  5270.6  251.91  5311.7  253.79  5373.3  255.99  5386.5  255.27
#Mann=5,-1,0
  4571.8     0.1       0  4661.1    0.12       0  5002.9    0.07       0
  5008.9    0.12       0  5311.7     0.1       0
Bank Sta=5002.9,5008.9
Exp/Cntr=0.3,0.1

Chan Stop Cuts=-1