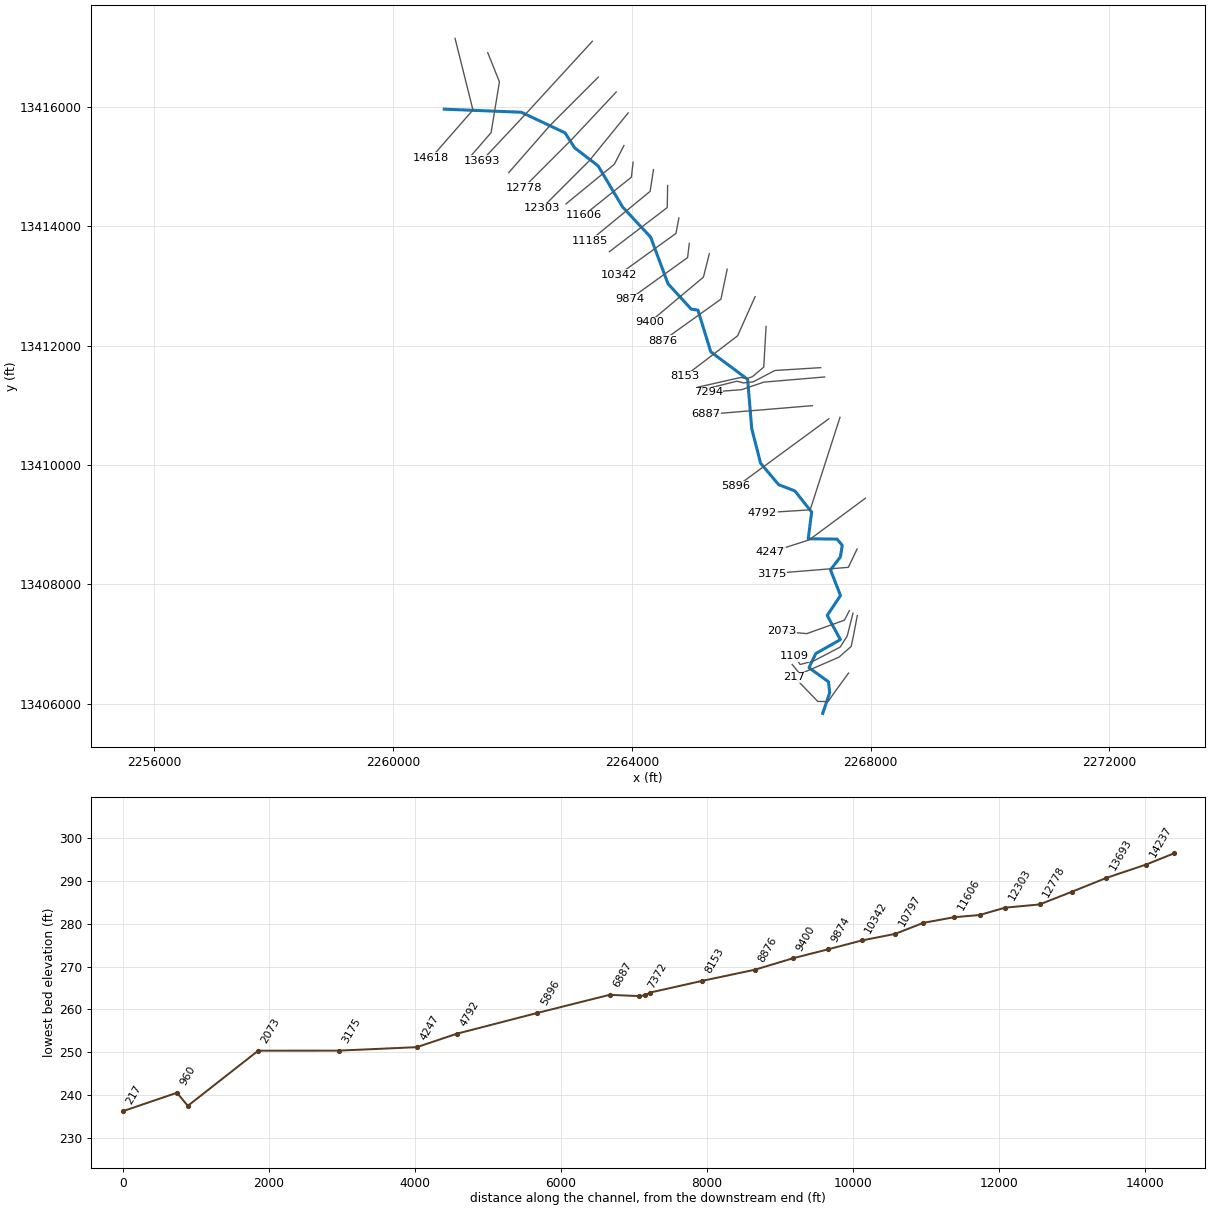
--- UNT042 IN SUCR.prj (project) ---

Proj Title=UNT042 IN SUCR Base Level Engineering
Current Plan=p01
Default Exp/Contr=0.3,0.1
English Units
Geom File=g01
Flow File=f01
Plan File=p01
BEGIN DESCRIPTION:
UNT042 IN SUCR
END DESCRIPTION:

--- UNT042 IN SUCR.p01 (plan) ---

Plan Title=Multiple Run
Short Identifier=Multiple
Geom File=g01
Flow File=f01
Subcritical Flow
K Sum by GR= 0
Std Step Tol= 0.01
Critical Tol= 0.01
Num of Std Step Trials= 20
Max Error Tol= 0.3
Flow Tol Ratio= 0.001
Split Flow NTrial= 30
Split Flow Tol= 0.02
Split Flow Ratio= 0.02
Log Output Level= 0
Friction Slope Method= 1
Unsteady Friction Slope Method= 2
Unsteady Bridges Friction Slope Method= 1
Parabolic Critical Depth
Global Vel Dist=  1 , 1 , 1
Global Log Level= 0
CheckData=True
Encroach Param= -1, 0, 0, 0
BEGIN DESCRIPTION:
Multiple Run
END DESCRIPTION:

--- UNT042 IN SUCR.f01 (steady flow) ---

Flow Title=Multiple
Number of Profiles=7
Profile Names=10-year,25-year,50-year,1pct_min,100-year,1pct_plu,500-year
River Rch & RM= UNT042 IN SUCR,Reach-1,14618
     293     408     503     457     618     836     945
River Rch & RM= UNT042 IN SUCR,Reach-1,11185
     337     471     584     531     718     972    1105
River Rch & RM= UNT042 IN SUCR,Reach-1,4792
     406     574     715     654     885    1197    1377
River Rch & RM= UNT042 IN SUCR,Reach-1,4247
     427     604     754     690     933    1262    1454
Boundary for River Rch & Prof#=UNT042 IN SUCR,Reach-1,1
Up Type=0
Dn Type=3
Dn Slope=0.005
Boundary for River Rch & Prof#=UNT042 IN SUCR,Reach-1,2
Up Type=0
Dn Type=3
Dn Slope=0.005
Boundary for River Rch & Prof#=UNT042 IN SUCR,Reach-1,3
Up Type=0
Dn Type=3
Dn Slope=0.005
Boundary for River Rch & Prof#=UNT042 IN SUCR,Reach-1,4
Up Type=0
Dn Type=3
Dn Slope=0.005
Boundary for River Rch & Prof#=UNT042 IN SUCR,Reach-1,5
Up Type=0
Dn Type=3
Dn Slope=0.005
Boundary for River Rch & Prof#=UNT042 IN SUCR,Reach-1,6
Up Type=0
Dn Type=3
Dn Slope=0.005
Boundary for River Rch & Prof#=UNT042 IN SUCR,Reach-1,7
Up Type=0
Dn Type=3
Dn Slope=0.005

--- UNT042 IN SUCR.g01 (geometry) ---

Geom Title=Existing Conditions

River Reach=UNT042 IN SUCR,Reach-1
Reach XY= 30
      2260856.98     13415959.97      2262148.21     13415908.69
      2262881.05     13415563.20      2263040.87     13415313.29
      2263434.69     13415010.19      2263845.94     13414320.32
      2264315.13     13413815.39      2264605.81     13413034.99
      2264994.52     13412610.27      2265107.58     13412592.60
      2265322.78     13411894.20      2265939.72     13411433.01
      2266008.87     13410606.25      2266157.72     13410026.85
      2266459.36     13409669.54      2266732.98     13409562.57
      2267012.28     13409209.35      2266955.35     13408761.78
      2267437.72     13408756.85      2267525.65     13408651.18
      2267494.12     13408458.45      2267328.39     13408241.78
      2267495.81     13407811.44      2267273.37     13407477.24
      2267493.91     13407072.81      2267082.18     13406839.08
      2266967.84     13406601.31      2267294.90     13406365.80
      2267315.01     13406181.43      2267197.72     13405836.85

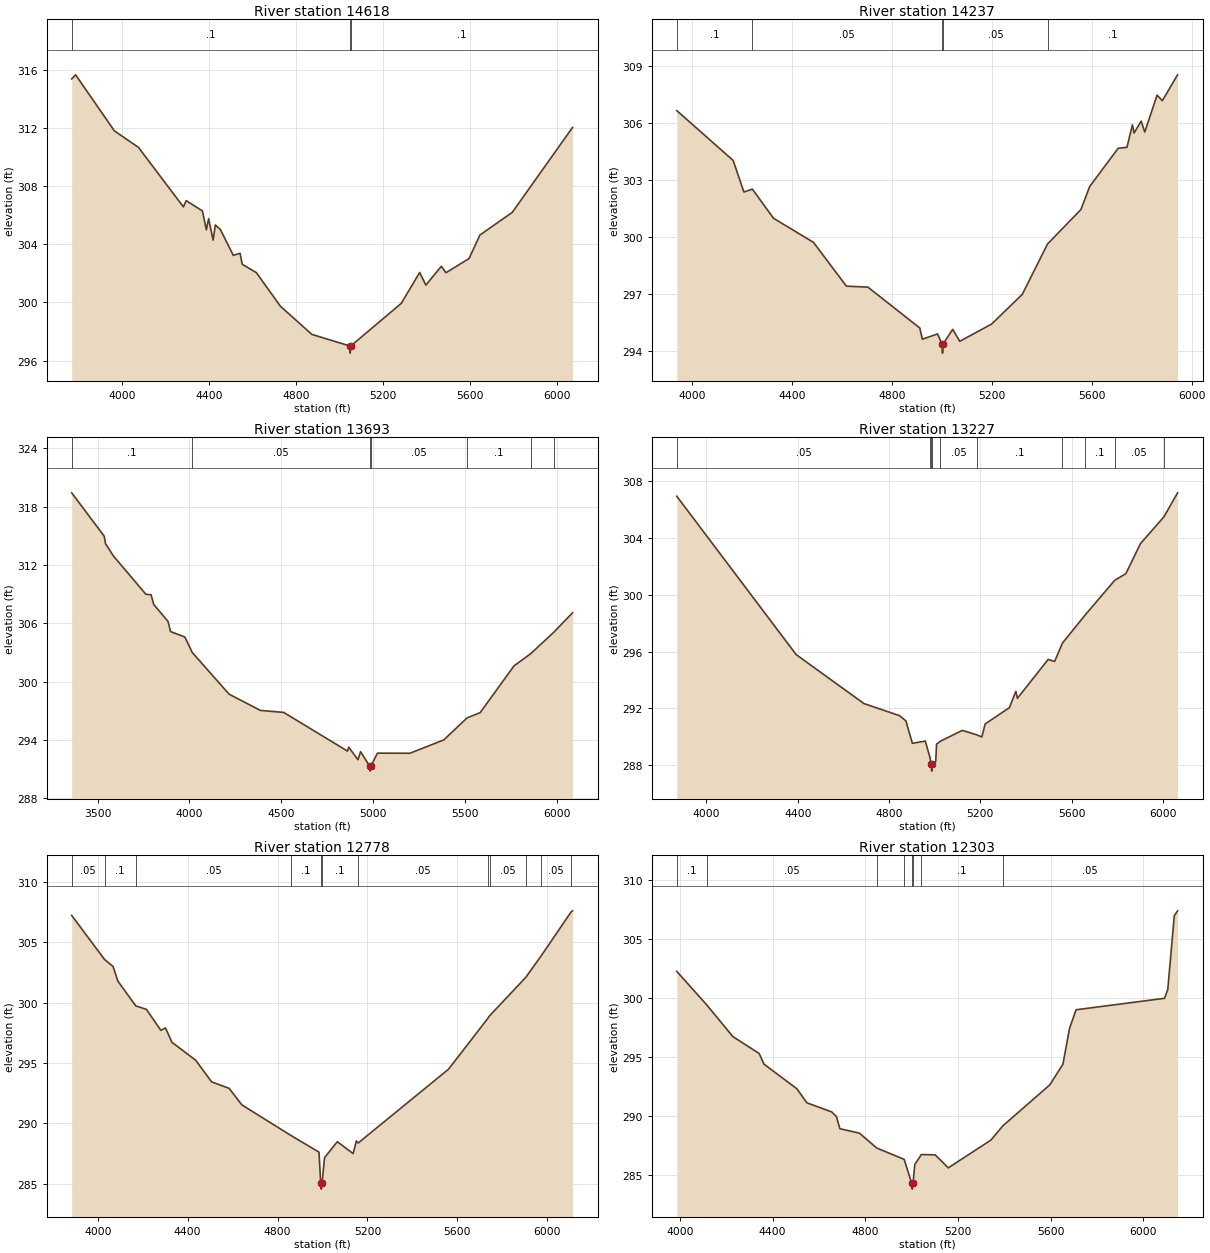
Type RM Length L Ch R = 1,14618,381,381,381
BEGIN DESCRIPTION:
UNT042 IN SUCR 21.0
END DESCRIPTION:
XS GIS Cut Line= 3
      2261037.73     13417146.83      2261337.72     13415946.85
      2260637.74     13415146.87
#Sta/Elev= 30
  3769.4  315.41  3787.4  315.69  3965.2  311.83  4076.0  310.69  4282.2  306.59
  4295.1  307.02  4369.8  306.31  4387.8  305.01  4398.2  305.78  4418.8  304.30
  4429.1  305.34  4452.3  305.03  4511.5  303.25  4542.5  303.39  4552.8  302.63
  4617.2  302.06  4728.0  299.74  4872.3  297.80  5045.5  297.01  5048.3  296.51
  5051.5  297.01  5283.0  299.94  5367.5  302.07  5395.9  301.20  5467.1  302.50
  5488.0  302.05  5594.3  303.03  5644.1  304.65  5792.7  306.21  6069.3  312.06
#Mann=3,-1,0
  3769.4     0.1       0  5045.5    0.07       0  5051.5     0.1       0
Bank Sta=5045.5,5051.5
Exp/Cntr=0.3,0.1

Type RM Length L Ch R = 1,14237,544,544,544
BEGIN DESCRIPTION:
UNT042 IN SUCR 20.0
END DESCRIPTION:
XS GIS Cut Line= 4
      2261586.09     13416906.42      2261781.41     13416418.12
      2261641.88     13415567.02      2261238.24     13415100.74
#Sta/Elev= 30
  3938.6  306.65  4164.3  304.03  4207.4  302.37  4241.4  302.52  4325.9  300.99
  4486.1  299.72  4617.8  297.42  4703.8  297.37  4911.7  295.22  4921.8  294.63
  4982.6  294.91  4999.9  294.40  5002.6  293.90  5005.9  294.40  5043.4  295.15
  5071.6  294.52  5199.3  295.43  5321.9  296.99  5423.2  299.64  5556.8  301.45
  5591.9  302.66  5705.9  304.67  5741.0  304.72  5762.9  305.90  5769.5  305.47
  5798.0  306.10  5812.3  305.52  5861.7  307.46  5882.7  307.17  5943.7  308.53
#Mann=5,-1,0
  3938.6     0.1       0  4241.4    0.05       0  4999.9    0.03       0
  5005.9    0.05       0  5423.2     0.1       0
Bank Sta=4999.9,5005.9
Exp/Cntr=0.3,0.1

Type RM Length L Ch R = 1,13693,466,466,466
BEGIN DESCRIPTION:
UNT042 IN SUCR 19.0
END DESCRIPTION:
XS GIS Cut Line= 3
      2263337.71     13417096.85      2262237.72     13415896.85
      2261487.69     13415096.82
#Sta/Elev= 30
  3359.4  319.42  3536.1  314.96  3543.5  314.19  3586.0  312.93  3763.0  308.98
  3791.3  308.93  3805.5  307.94  3883.2  306.19  3897.4  305.14  3975.1  304.58
  4015.2  302.99  4215.6  298.70  4385.8  297.03  4512.8  296.82  4859.9  292.84
  4866.7  293.24  4916.7  291.95  4930.9  292.78  4980.9  291.28  4983.6  290.78
  4986.9  291.28  5022.7  292.63  5199.5  292.62  5383.6  293.99  5510.3  296.26
  5581.5  296.80  5765.6  301.61  5856.8  302.87  5981.3  305.06  6083.9  307.07
#Mann=7,-1,0
  3359.4     0.1       0  4015.2    0.05       0  4980.9    0.03       0
  4986.9    0.05       0  5510.3     0.1       0  5856.8    0.05       0
  5981.3     0.1       0
Bank Sta=4980.9,4986.9
Exp/Cntr=0.3,0.1

Type RM Length L Ch R = 1,13227,449,449,449
BEGIN DESCRIPTION:
UNT042 IN SUCR 18.0
END DESCRIPTION:
XS GIS Cut Line= 3
      2263437.69     13416496.82      2262637.72     13415696.85
      2261937.75     13414896.88
#Sta/Elev= 30
  3869.9  306.95  4393.1  295.79  4690.1  292.34  4845.7  291.49  4873.9  291.12
  4902.2  289.54  4958.8  289.70  4979.6  288.53  4984.1  288.08  4986.8  287.58
  4990.1  288.08  5004.5  288.26  5008.3  289.48  5025.0  289.69  5121.3  290.45
  5183.4  290.14  5206.7  289.99  5220.9  290.90  5327.2  292.05  5355.7  293.20
  5362.4  292.71  5497.1  295.45  5525.6  295.31  5559.7  296.60  5660.2  298.60
  5788.6  301.02  5837.9  301.50  5901.5  303.61  6004.4  305.50  6064.2  307.19
#Mann=10,-1,0
  3869.9    0.05       0  4979.6     0.1       0  4984.1    0.07       0
  4990.1     0.1       0  5025.0    0.05       0  5183.4     0.1       0
  5559.7    0.05       0  5660.2     0.1       0  5788.6    0.05       0
  6004.4     0.1       0
Bank Sta=4984.1,4990.1
Exp/Cntr=0.3,0.1

Type RM Length L Ch R = 1,12778,475,475,475
BEGIN DESCRIPTION:
UNT042 IN SUCR 17.0
END DESCRIPTION:
XS GIS Cut Line= 3
      2263737.70     13416246.83      2262987.72     13415446.85
      2262187.74     13414646.87
#Sta/Elev= 30
  3884.2  307.21  4030.2  303.57  4068.1  302.99  4089.5  301.78  4169.1  299.73
  4216.6  299.44  4280.5  297.71  4301.6  297.90  4329.9  296.72  4435.9  295.23
  4506.7  293.44  4584.4  292.91  4641.0  291.54  4860.2  289.00  4984.3  287.63
  4991.9  285.07  4994.6  284.57  4997.9  285.07  5009.0  287.17  5065.6  288.49
  5136.3  287.51  5150.5  288.55  5159.0  288.39  5560.6  294.49  5734.0  298.66
  5743.4  298.91  5904.0  302.08  5974.0  303.90  6105.1  307.48  6112.1  307.59
#Mann=12,-1,0
  3884.2    0.05       0  4030.2     0.1       0  4169.1    0.05       0
  4860.2     0.1       0  4991.9    0.07       0  4997.9     0.1       0
  5159.0    0.05       0  5734.0     0.1       0  5743.4    0.05       0
  5904.0     0.1       0  5974.0    0.05       0  6105.1     0.1       0
Bank Sta=4991.9,4997.9
Exp/Cntr=0.3,0.1

Type RM Length L Ch R = 1,12303,345,345,345
BEGIN DESCRIPTION:
UNT042 IN SUCR 16.0
END DESCRIPTION:
XS GIS Cut Line= 3
      2263937.74     13415896.88      2263287.72     13415096.85
      2262487.71     13414296.84
#Sta/Elev= 30
  3986.3  302.25  4115.0  299.43  4228.4  296.73  4341.9  295.30  4362.7  294.40
  4504.9  292.31  4548.1  291.12  4655.1  290.35  4675.9  289.95  4690.3  288.93
  4775.0  288.55  4849.8  287.29  4968.1  286.33  5000.5  284.31  5003.2  283.81
  5006.5  284.31  5013.9  285.89  5042.3  286.74  5102.0  286.71  5158.5  285.61
  5342.4  287.96  5394.1  289.17  5596.9  292.64  5653.5  294.39  5681.8  297.40
  5710.1  299.00  6091.9  299.97  6106.1  300.70  6134.3  306.96  6148.5  307.38
#Mann=8,-1,0
  3986.3     0.1       0  4115.0    0.05       0  4849.8     0.1       0
  4968.1    0.05       0  5000.5    0.03       0  5006.5    0.05       0
  5042.3     0.1       0  5394.1    0.05       0
Bank Sta=5000.5,5006.5
Exp/Cntr=0.3,0.1

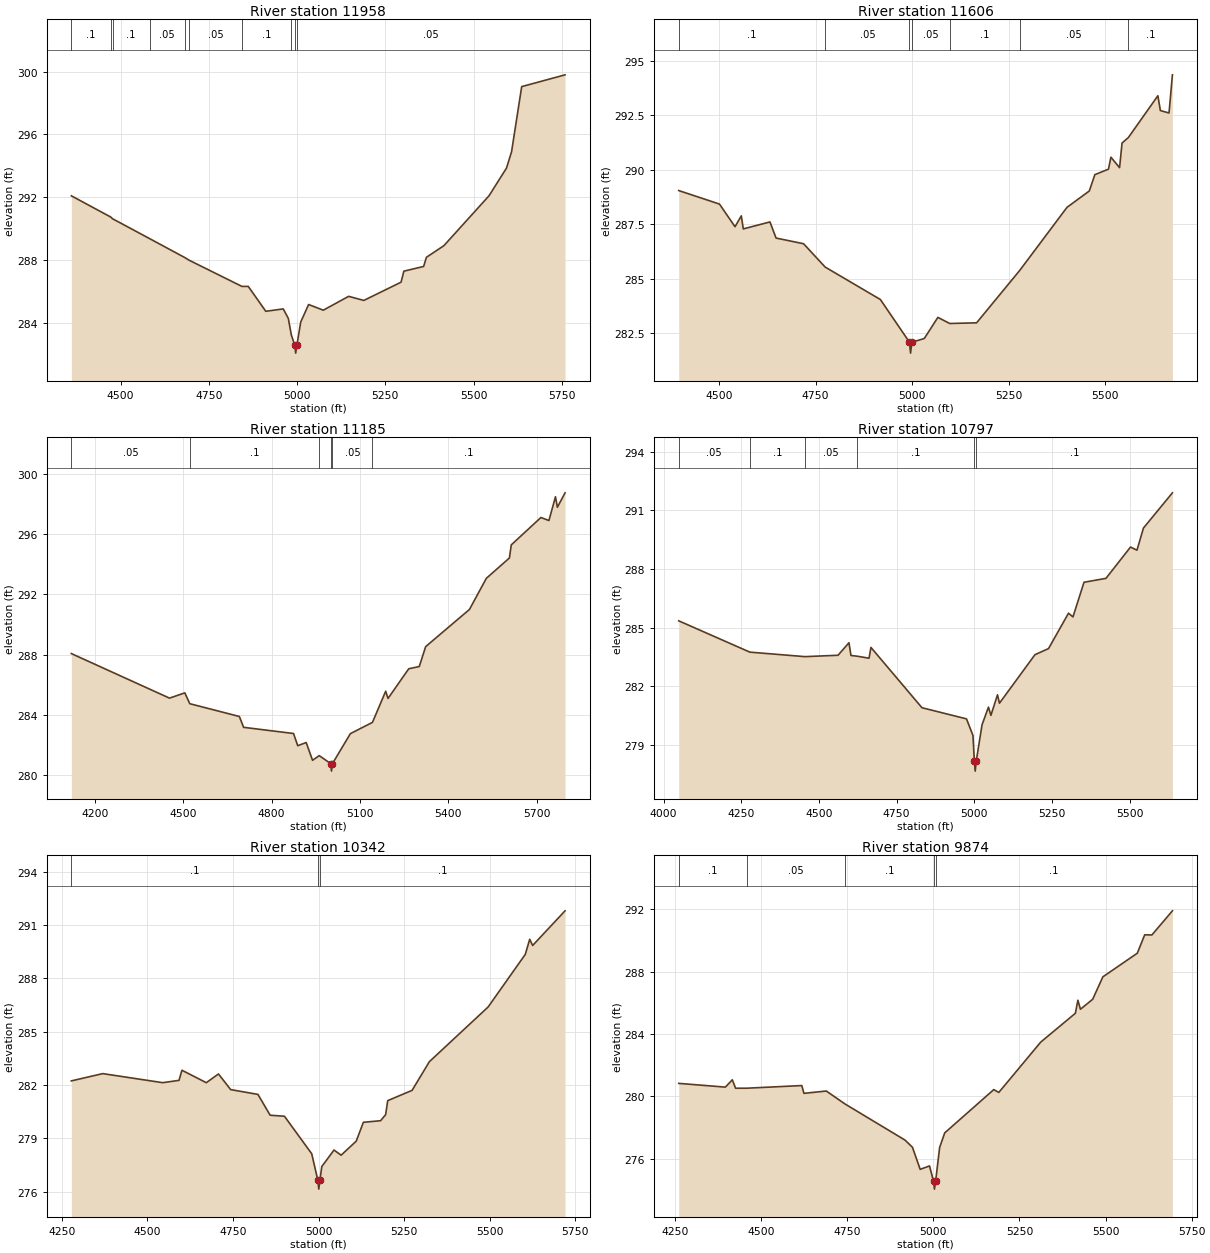
Type RM Length L Ch R = 1,11958,352,352,352
BEGIN DESCRIPTION:
UNT042 IN SUCR 15.0
END DESCRIPTION:
XS GIS Cut Line= 3
      2263867.28     13415350.74      2263706.84     13415036.83
      2262897.61     13414374.11
#Sta/Elev= 30
  4360.5  292.10  4472.1  290.75  4477.4  290.64  4582.1  289.38  4681.4  288.18
  4694.6  288.00  4843.8  286.34  4861.7  286.34  4911.3  284.76  4960.8  284.91
  4975.1  284.31  4983.6  283.26  4993.3  282.60  4996.0  282.10  4999.3  282.60
  5010.3  284.08  5032.6  285.19  5074.2  284.83  5146.0  285.71  5189.0  285.45
  5294.5  286.61  5302.4  287.31  5358.4  287.61  5366.3  288.19  5415.8  288.93
  5543.6  292.10  5593.1  293.86  5607.5  294.90  5636.2  299.04  5759.0  299.79
#Mann=10,-1,0
  4360.5     0.1       0  4472.1    0.05       0  4477.4     0.1       0
  4582.1    0.05       0  4681.4     0.1       0  4694.6    0.05       0
  4843.8     0.1       0  4983.6    0.05       0  4993.3    0.03       0
  4999.3    0.05       0
Bank Sta=4993.3,4999.3
Exp/Cntr=0.3,0.1

Type RM Length L Ch R = 1,11606,421,421,421
BEGIN DESCRIPTION:
UNT042 IN SUCR 14.0
END DESCRIPTION:
XS GIS Cut Line= 3
      2264020.77     13415071.73      2263992.86     13414820.57
      2263191.69     13414179.64
#Sta/Elev= 30
  4395.3  289.04  4500.8  288.42  4541.1  287.38  4557.4  287.88  4562.5  287.28
  4631.6  287.60  4647.4  286.86  4718.6  286.60  4774.5  285.53  4917.6  284.04
  4993.0  282.08  4995.8  281.58  4999.0  282.08  5031.3  282.25  5066.5  283.22
  5097.2  282.94  5166.8  282.97  5278.3  285.37  5401.0  288.27  5458.7  289.02
  5473.1  289.77  5508.3  290.02  5514.7  290.57  5537.1  290.09  5543.5  291.22
  5559.8  291.47  5636.3  293.39  5642.8  292.71  5665.2  292.60  5674.0  294.35
#Mann=7,-1,0
  4395.3     0.1       0  4774.5    0.05       0  4993.0    0.03       0
  4999.0    0.05       0  5097.2     0.1       0  5278.3    0.05       0
  5559.8     0.1       0
Bank Sta=4993,4999
Exp/Cntr=0.3,0.1

Type RM Length L Ch R = 1,11185,388,388,388
BEGIN DESCRIPTION:
UNT042 IN SUCR 13.0
END DESCRIPTION:
XS GIS Cut Line= 3
      2264362.59     13414946.09      2264306.79     13414583.38
      2263295.22     13413753.19
#Sta/Elev= 30
  4120.2  288.07  4453.3  285.11  4505.4  285.46  4522.1  284.74  4690.5  283.89
  4704.8  283.17  4874.2  282.76  4888.6  281.95  4917.3  282.16  4938.8  280.98
  4961.5  281.29  5000.4  280.76  5003.1  280.26  5006.4  280.76  5067.2  282.75
  5142.2  283.50  5187.1  285.57  5195.0  285.09  5265.3  287.06  5301.0  287.21
  5322.7  288.53  5471.3  291.00  5528.7  293.07  5606.9  294.42  5613.3  295.29
  5713.8  297.11  5741.1  296.91  5763.3  298.49  5769.8  297.79  5795.8  298.75
#Mann=6,-1,0
  4120.2    0.05       0  4522.1     0.1       0  4961.5    0.05       0
  5000.4    0.04       0  5006.4    0.05       0  5142.2     0.1       0
Bank Sta=5000.4,5006.4
Exp/Cntr=0.3,0.1

Type RM Length L Ch R = 1,10797,455,455,455
BEGIN DESCRIPTION:
UNT042 IN SUCR 12.0
END DESCRIPTION:
XS GIS Cut Line= 3
      2264599.79     13414681.04      2264592.81     13414311.31
      2263623.10     13413571.82
#Sta/Elev= 30
  4048.7  285.35  4277.7  283.75  4454.8  283.52  4561.5  283.59  4596.8  284.23
  4603.1  283.58  4624.1  283.54  4661.3  283.44  4667.5  283.99  4831.7  280.91
  4975.1  280.34  4995.9  279.49  5000.4  278.17  5003.1  277.67  5006.4  278.17
  5025.0  280.03  5045.8  280.94  5053.7  280.52  5074.9  281.57  5081.2  281.14
  5195.5  283.62  5239.1  283.93  5303.5  285.74  5317.8  285.55  5353.4  287.32
  5424.1  287.52  5503.1  289.12  5523.9  288.96  5544.7  290.09  5638.0  291.89
#Mann=6,-1,0
  4048.7    0.05       0  4277.7     0.1       0  4454.8    0.05       0
  4624.1     0.1       0  5000.4    0.07       0  5006.4     0.1       0
Bank Sta=5000.4,5006.4
Exp/Cntr=0.3,0.1

Type RM Length L Ch R = 1,10342,468,468,468
BEGIN DESCRIPTION:
UNT042 IN SUCR 11.0
END DESCRIPTION:
XS GIS Cut Line= 3
      2264788.14     13414136.89      2264739.31     13413878.79
      2263783.61     13413188.17
#Sta/Elev= 30
  4278.2  282.23  4369.8  282.64  4545.0  282.13  4592.6  282.26  4601.2  282.83
  4672.3  282.13  4707.9  282.62  4743.5  281.74  4823.2  281.47  4858.7  280.30
  4900.6  280.24  4980.2  278.13  4998.1  276.64  5000.8  276.14  5004.1  276.64
  5009.6  277.41  5045.2  278.34  5066.1  278.05  5110.2  278.84  5131.0  279.90
  5181.3  279.99  5196.0  280.33  5202.2  281.12  5273.4  281.70  5323.7  283.31
  5495.4  286.39  5603.9  289.35  5616.8  290.20  5625.4  289.85  5720.0  291.80
#Mann=3,-1,0
  4278.2     0.1       0  4998.1    0.07       0  5004.1     0.1       0
Bank Sta=4998.1,5004.1
Exp/Cntr=0.3,0.1

Type RM Length L Ch R = 1,9874,474,474,474
BEGIN DESCRIPTION:
UNT042 IN SUCR 10.0
END DESCRIPTION:
XS GIS Cut Line= 3
      2264962.55     13413711.31      2264934.65     13413474.17
      2263964.99     13412776.57
#Sta/Elev= 30
  4260.9  280.83  4396.3  280.59  4416.4  281.06  4426.0  280.52  4457.9  280.52
  4618.2  280.69  4624.4  280.19  4689.4  280.34  4743.5  279.51  4917.8  277.19
  4939.4  276.73  4961.9  275.31  4989.0  275.53  5000.7  274.54  5003.4  274.04
  5006.7  274.54  5018.4  276.72  5033.1  277.65  5175.5  280.43  5190.2  280.25
  5311.8  283.48  5412.4  285.33  5419.8  286.17  5427.1  285.59  5462.7  286.23
  5492.2  287.67  5592.3  289.19  5613.7  290.37  5634.6  290.36  5694.2  291.91
#Mann=5,-1,0
  4260.9     0.1       0  4457.9    0.05       0  4743.5     0.1       0
  5000.7    0.07       0  5006.7     0.1       0
Bank Sta=5000.7,5006.7
Exp/Cntr=0.3,0.1

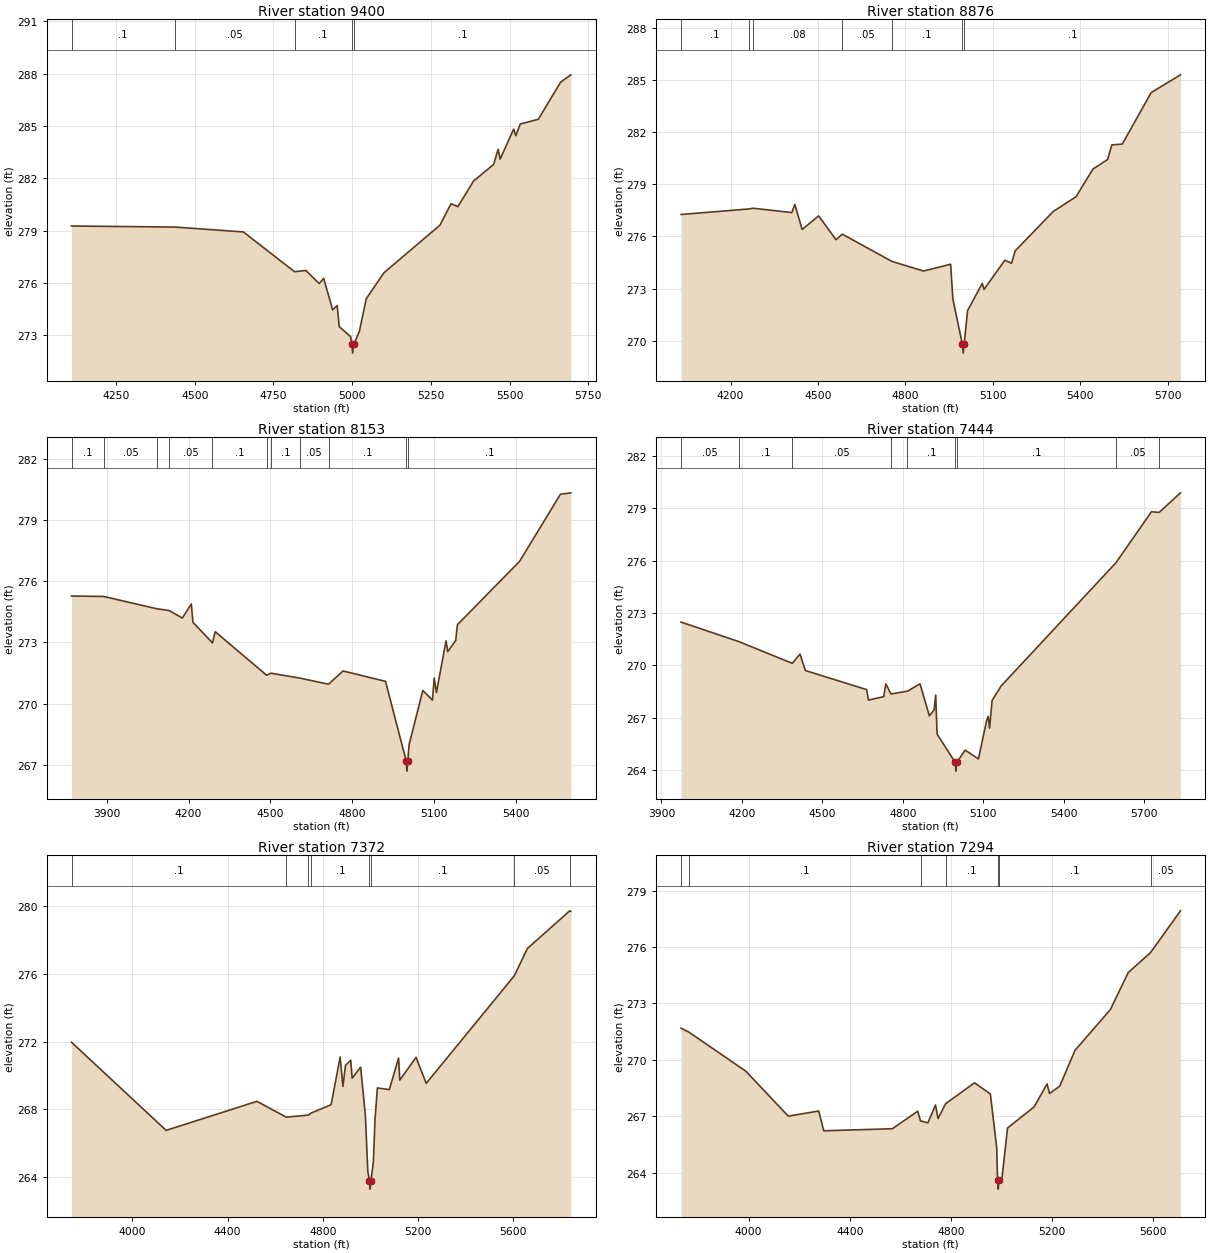
Type RM Length L Ch R = 1,9400,524,524,524
BEGIN DESCRIPTION:
UNT042 IN SUCR 9.0
END DESCRIPTION:
XS GIS Cut Line= 3
      2265297.40     13413536.91      2265199.74     13413146.29
      2264292.80     13412385.85
#Sta/Elev= 30
  4108.4  279.27  4436.6  279.21  4654.4  278.93  4816.9  276.65  4853.0  276.72
  4895.1  275.97  4909.4  276.27  4938.0  274.46  4952.3  274.71  4958.8  273.50
  4995.2  272.92  4998.7  272.48  5001.5  271.98  5004.7  272.48  5022.6  273.21
  5044.7  275.10  5100.9  276.59  5278.8  279.32  5314.0  280.55  5335.8  280.38
  5385.5  281.85  5449.3  282.80  5463.6  283.67  5470.1  283.11  5513.0  284.83
  5519.6  284.45  5533.9  285.12  5591.1  285.39  5662.1  287.52  5694.6  287.94
#Mann=5,-1,0
  4108.4     0.1       0  4436.6    0.05       0  4816.9     0.1       0
  4998.7    0.07       0  5004.7     0.1       0
Bank Sta=4998.7,5004.7
Exp/Cntr=0.3,0.1

Type RM Length L Ch R = 1,8876,723,723,723
BEGIN DESCRIPTION:
UNT042 IN SUCR 8.0
END DESCRIPTION:
XS GIS Cut Line= 3
      2265597.39     13413278.86      2265492.74     13412776.55
      2264516.10     13412078.95
#Sta/Elev= 30
  4030.1  277.26  4263.6  277.58  4278.1  277.62  4410.1  277.37  4420.3  277.84
  4445.5  276.40  4502.0  277.18  4561.7  275.81  4583.1  276.13  4753.9  274.56
  4861.9  274.01  4954.9  274.40  4962.6  272.40  4995.3  269.79  4998.0  269.29
  5001.3  269.79  5013.0  271.73  5063.4  273.30  5069.5  272.95  5140.8  274.63
  5163.8  274.46  5176.4  275.17  5306.7  277.43  5385.0  278.28  5443.1  279.87
  5493.5  280.42  5507.9  281.26  5543.9  281.31  5643.1  284.27  5743.4  285.29
#Mann=7,-1,0
  4030.1     0.1       0  4263.6    0.05       0  4278.1    0.08       0
  4583.1    0.05       0  4753.9     0.1       0  4995.3    0.07       0
  5001.3     0.1       0
Bank Sta=4995.3,5001.3
Exp/Cntr=0.3,0.1

Type RM Length L Ch R = 1,8153,709,709,709
BEGIN DESCRIPTION:
UNT042 IN SUCR 7.0
END DESCRIPTION:
XS GIS Cut Line= 3
      2266064.78     13412818.38      2265771.79     13412162.64
      2264885.78     13411485.93
#Sta/Elev= 30
  3770.1  275.28  3888.2  275.26  4084.9  274.65  4128.1  274.57  4177.0  274.20
  4209.9  274.89  4215.9  273.99  4287.6  272.98  4297.5  273.53  4486.4  271.39
  4501.7  271.49  4608.2  271.25  4713.5  270.95  4766.8  271.60  4922.8  271.09
  4998.7  267.18  5001.4  266.68  5004.7  267.18  5009.3  267.98  5059.7  270.64
  5095.2  270.17  5101.5  271.25  5109.7  270.54  5145.0  273.08  5151.3  272.55
  5180.4  273.10  5186.7  273.87  5415.3  276.99  5564.9  280.28  5603.2  280.35
#Mann=11,-1,0
  3770.1     0.1       0  3888.2    0.05       0  4084.9     0.1       0
  4128.1    0.05       0  4287.6     0.1       0  4486.4    0.05       0
  4501.7     0.1       0  4608.2    0.05       0  4713.5     0.1       0
  4998.7    0.07       0  5004.7     0.1       0
Bank Sta=4998.7,5004.7
Exp/Cntr=0.3,0.1

Type RM Length L Ch R = 1,7444,72,72,72
BEGIN DESCRIPTION:
Mapping XS 86d2e2f0
END DESCRIPTION:
XS GIS Cut Line= 6
      2266249.00     13412319.72      2266209.93     13411638.27
      2266018.96     13411477.68      2265927.82     13411447.30
      2265823.65     13411464.66      2265112.30     13411304.17
#Sta/Elev= 30
  3973.1  272.48  4189.4  271.36  4387.9  270.12  4416.7  270.65  4437.0  269.71
  4665.4  268.62  4671.9  268.02  4729.1  268.22  4736.9  268.95  4756.1  268.37
  4817.5  268.53  4864.4  268.95  4899.5  267.12  4917.0  267.46  4923.0  268.31
  4928.2  266.08  4995.7  264.46  4998.4  263.96  5001.7  264.46  5032.9  265.16
  5082.5  264.66  5112.9  266.85  5118.8  267.09  5124.0  266.42  5133.4  268.00
  5167.2  268.83  5595.8  275.88  5728.0  278.79  5756.7  278.75  5836.1  279.87
#Mann=9,-1,0
  3973.1    0.05       0  4189.4     0.1       0  4387.9    0.05       0
  4756.1    0.08       0  4817.5     0.1       0  4995.7    0.07       0
  5001.7     0.1       0  5595.8    0.05       0  5756.7     0.1       0
Bank Sta=4995.7,5001.7
Exp/Cntr=0.3,0.1

Type RM Length L Ch R = 1,7372,78,78,78
BEGIN DESCRIPTION:
UNT042 IN SUCR 6.0
END DESCRIPTION:
XS GIS Cut Line= 6
      2267164.84     13411629.59      2266396.57     13411581.85
      2266031.98     13411390.88      2265867.05     13411373.52
      2265762.04     13411402.94      2265137.68     13411246.84
#Sta/Elev= 30
  3743.7  271.96  4141.6  266.77  4523.4  268.48  4646.6  267.55  4739.8  267.67
  4751.0  267.79  4835.3  268.28  4873.4  271.09  4885.1  269.36  4895.8  270.60
  4917.9  270.90  4923.6  269.84  4959.5  270.49  4979.6  267.62  4989.6  264.36
  4996.7  263.81  4999.4  263.31  5002.7  263.81  5013.0  264.90  5019.8  267.38
  5029.9  269.27  5080.1  269.17  5119.0  271.03  5124.2  269.73  5192.4  271.07
  5235.3  269.54  5606.0  275.88  5660.5  277.48  5838.8  279.70  5843.5  279.67
#Mann=8,-1,0
  3743.7     0.1       0  4646.6    0.05       0  4739.8    0.08       0
  4751.0     0.1       0  4996.7    0.07       0  5002.7     0.1       0
  5606.0    0.05       0  5838.8     0.1       0
Bank Sta=4996.7,5002.7
Exp/Cntr=0.3,0.1

Type RM Length L Ch R = 1,7294,407,407,407
BEGIN DESCRIPTION:
Mapping XS 531e5e79
END DESCRIPTION:
XS GIS Cut Line= 4
      2267229.92     13411473.34      2266209.93     13411386.54
      2265841.01     13411260.67      2265281.87     13411217.32
#Sta/Elev= 30
  3733.4  271.68  3763.7  271.48  3989.2  269.40  4157.1  267.01  4277.6  267.28
  4297.6  266.23  4568.6  266.34  4669.0  267.27  4680.0  266.76  4709.1  266.65
  4739.2  267.60  4749.3  266.88  4779.3  267.67  4893.5  268.78  4956.1  268.19
  4981.3  265.33  4984.5  263.63  4987.2  263.13  4990.5  263.63  5002.4  263.75
  5024.1  266.38  5129.2  267.50  5180.3  268.72  5190.3  268.21  5230.4  268.60
  5290.6  270.50  5431.0  272.68  5501.2  274.64  5589.4  275.70  5707.7  277.92
#Mann=7,-1,0
  3733.4    0.05       0  3763.7     0.1       0  4680.0    0.08       0
  4779.3     0.1       0  4984.5    0.07       0  4990.5     0.1       0
  5589.4    0.05       0
Bank Sta=4984.5,4990.5
Exp/Cntr=0.3,0.1

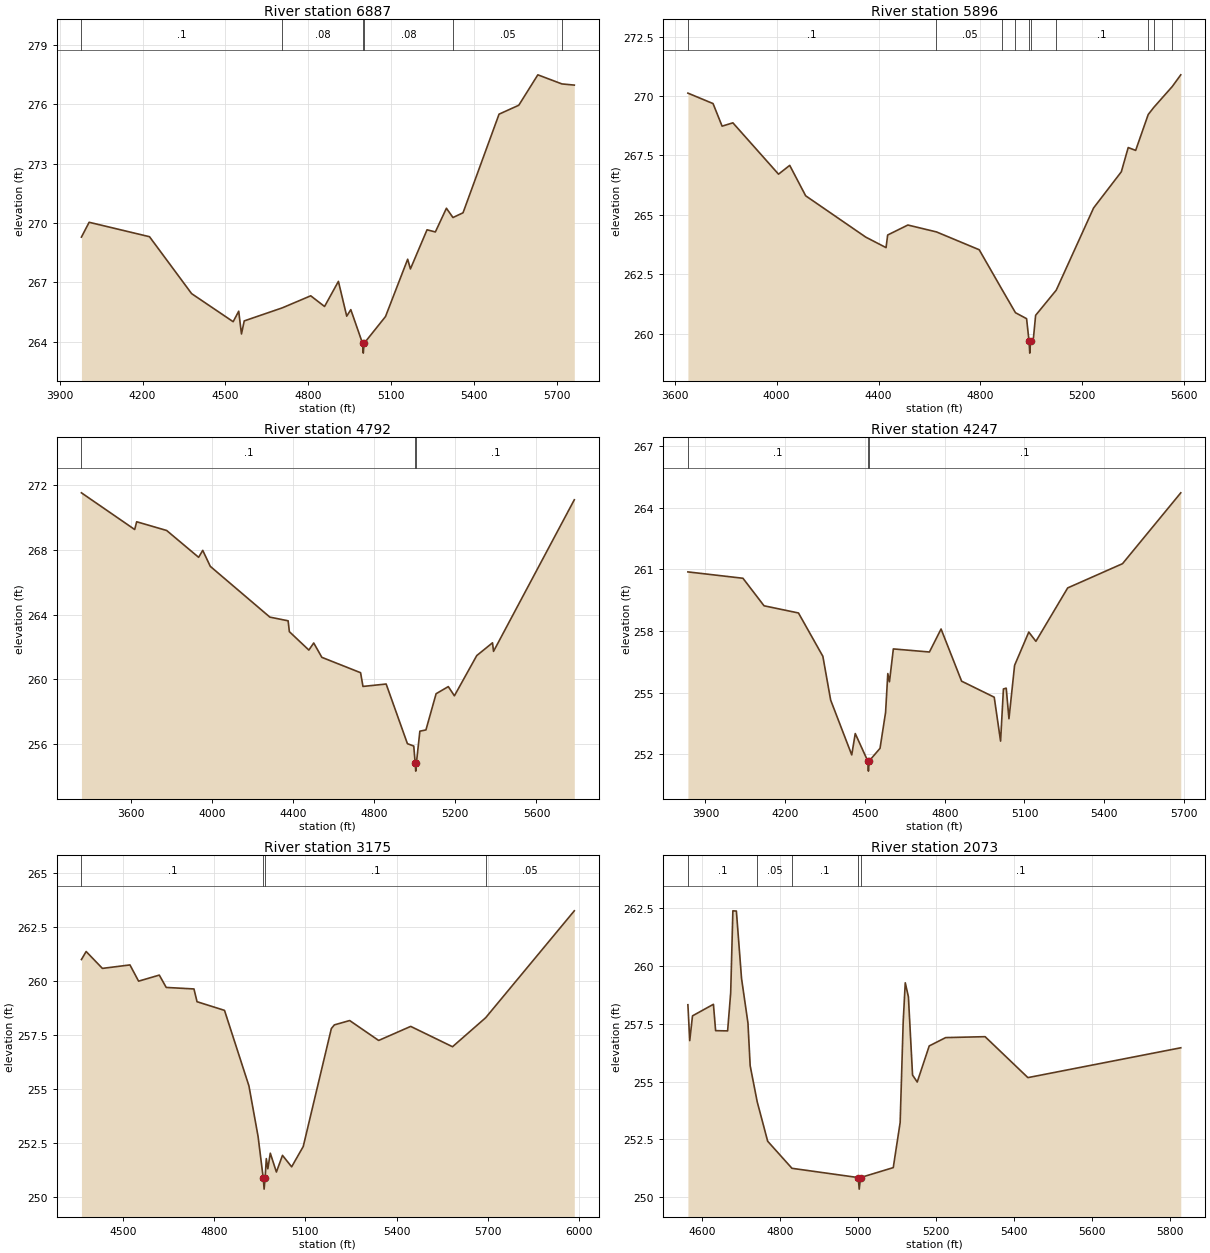
Type RM Length L Ch R = 1,6887,991,991,991
BEGIN DESCRIPTION:
UNT042 IN SUCR 5.0
END DESCRIPTION:
XS GIS Cut Line= 2
      2267025.53     13410992.48      2265246.04     13410844.91
#Sta/Elev= 30
  3978.5  269.29  4006.4  270.04  4225.1  269.31  4377.7  266.43  4528.2  265.01
  4548.3  265.54  4558.3  264.39  4568.3  265.05  4706.1  265.71  4809.2  266.32
  4859.3  265.78  4909.5  267.05  4939.6  265.29  4954.4  265.62  4996.8  263.92
  4999.6  263.42  5002.8  263.92  5080.1  265.27  5160.4  268.17  5170.4  267.68
  5230.6  269.66  5260.7  269.55  5300.8  270.75  5324.5  270.28  5361.0  270.52
  5491.5  275.51  5562.9  275.96  5632.0  277.50  5719.2  277.04  5764.1  276.98
#Mann=6,-1,0
  3978.5     0.1       0  4706.1    0.08       0  4996.8    0.07       0
  5002.8    0.08       0  5324.5    0.05       0  5719.2     0.1       0
Bank Sta=4996.8,5002.8
Exp/Cntr=0.3,0.1

Type RM Length L Ch R = 1,5896,1104,1104,1104
BEGIN DESCRIPTION:
Mapping XS 4a9a123c
END DESCRIPTION:
XS GIS Cut Line= 3
      2267300.18     13410771.93      2265814.10     13409681.67
      2265731.74     13409640.49
#Sta/Elev= 30
  3651.5  270.12  3750.3  269.68  3785.8  268.73  3828.2  268.87  4007.3  266.71
  4051.3  267.08  4113.9  265.80  4350.0  264.06  4429.5  263.62  4435.9  264.15
  4515.2  264.57  4627.5  264.28  4795.3  263.53  4886.3  261.83  4937.7  260.88
  4981.3  260.63  4991.0  259.68  4993.8  259.18  4997.0  259.68  5008.3  259.82
  5016.8  260.77  5097.8  261.83  5244.5  265.29  5353.3  266.81  5380.3  267.83
  5409.6  267.71  5458.9  269.22  5480.8  269.52  5553.5  270.40  5586.7  270.89
#Mann=10,-1,0
  3651.5     0.1       0  4627.5    0.05       0  4886.3     0.1       0
  4937.7    0.05       0  4991.0   0.035       0  4997.0    0.05       0
  5097.8     0.1       0  5458.9    0.05       0  5480.8     0.1       0
  5553.5    0.05       0
Bank Sta=4991,4997
Exp/Cntr=0.3,0.1

Type RM Length L Ch R = 1,4792,545,545,545
BEGIN DESCRIPTION:
UNT042 IN SUCR 4.0
END DESCRIPTION:
XS GIS Cut Line= 3
      2267487.71     13410796.81      2266987.72     13409246.85
      2266187.68     13409196.85
#Sta/Elev= 30
  3356.5  271.53  3619.1  269.26  3628.9  269.74  3776.7  269.20  3934.4  267.54
  3954.6  267.97  3991.9  266.98  4285.6  263.84  4375.7  263.61  4381.7  262.94
  4477.9  261.80  4501.8  262.24  4542.0  261.35  4732.9  260.40  4744.7  259.55
  4859.0  259.70  4963.8  256.01  4995.1  255.86  5002.1  254.81  5004.9  254.31
  5008.1  254.81  5025.2  256.78  5055.2  256.86  5105.3  259.10  5165.5  259.54
  5195.5  258.97  5305.7  261.46  5383.4  262.25  5388.4  261.72  5786.7  271.10
#Mann=3,-1,0
  3356.5     0.1       0  5002.1    0.07       0  5008.1     0.1       0
Bank Sta=5002.1,5008.1
Exp/Cntr=0.3,0.1

Type RM Length L Ch R = 1,4247,1072,1072,1072
BEGIN DESCRIPTION:
Mapping XS 676bd3cd
END DESCRIPTION:
XS GIS Cut Line= 3
      2267913.47     13409441.92      2266971.69     13408744.31
      2266322.92     13408535.03
#Sta/Elev= 30
  3834.2  260.88  4041.3  260.57  4120.6  259.23  4250.1  258.88  4341.8  256.77
  4371.1  254.64  4450.4  251.97  4463.6  253.01  4510.4  251.68  4513.1  251.18
  4516.4  251.68  4556.8  252.29  4577.7  254.04  4586.1  255.93  4592.3  255.53
  4606.9  257.13  4742.6  256.98  4786.4  258.10  4863.6  255.56  4986.3  254.78
  5010.2  252.64  5020.9  255.18  5031.4  255.22  5041.7  253.73  5062.9  256.33
  5116.3  257.95  5143.1  257.50  5262.6  260.10  5468.8  261.28  5687.9  264.73
#Mann=3,-1,0
  3834.2     0.1       0  4510.4    0.07       0  4516.4     0.1       0
Bank Sta=4510.4,4516.4
Exp/Cntr=0.3,0.1

Type RM Length L Ch R = 1,3175,1102,1102,1102
BEGIN DESCRIPTION:
Mapping XS 3b77f041
END DESCRIPTION:
XS GIS Cut Line= 3
      2267773.95     13408590.83      2267627.45     13408283.88
      2266351.75     13408179.31
#Sta/Elev= 30
  4363.7  260.98  4379.2  261.35  4432.6  260.57  4523.2  260.73  4551.6  259.98
  4619.7  260.26  4642.4  259.69  4733.6  259.62  4743.7  259.03  4834.0  258.63
  4914.3  255.14  4944.4  252.80  4961.4  250.87  4964.2  250.37  4967.4  250.87
  4971.4  251.78  4976.4  251.31  4984.5  252.03  5004.6  251.16  5024.6  251.93
  5054.7  251.40  5092.8  252.34  5185.2  257.79  5195.2  257.96  5245.4  258.16
  5340.7  257.24  5446.0  257.89  5583.5  256.95  5692.4  258.29  5983.8  263.23
#Mann=4,-1,0
  4363.7     0.1       0  4961.4    0.07       0  4967.4     0.1       0
  5692.4    0.05       0
Bank Sta=4961.4,4967.4
Exp/Cntr=0.3,0.1

Type RM Length L Ch R = 1,2073,964,964,964
BEGIN DESCRIPTION:
UNT042 IN SUCR 3.0
END DESCRIPTION:
XS GIS Cut Line= 4
      2267644.16     13407557.36      2267562.18     13407398.54
      2266931.98     13407173.10      2266516.97     13407208.96
#Sta/Elev= 30
  4563.4  258.32  4568.1  256.77  4575.2  257.84  4628.9  258.34  4634.5  257.20
  4665.3  257.19  4673.2  258.84  4678.8  262.38  4687.8  262.37  4701.0  259.46
  4717.5  257.53  4723.2  255.68  4741.3  254.12  4768.1  252.42  4830.4  251.25
  5000.3  250.85  5003.0  250.35  5006.3  250.85  5090.3  251.28  5108.0  253.23
  5115.8  257.58  5121.1  259.27  5129.2  258.66  5139.8  255.28  5151.8  254.98
  5182.6  256.54  5224.8  256.90  5325.9  256.94  5435.8  255.17  5828.0  256.46
#Mann=5,-1,0
  4563.4     0.1       0  4741.3    0.05       0  4830.4     0.1       0
  5000.3    0.07       0  5006.3     0.1       0
Bank Sta=5000.3,5006.3
Exp/Cntr=0.3,0.1

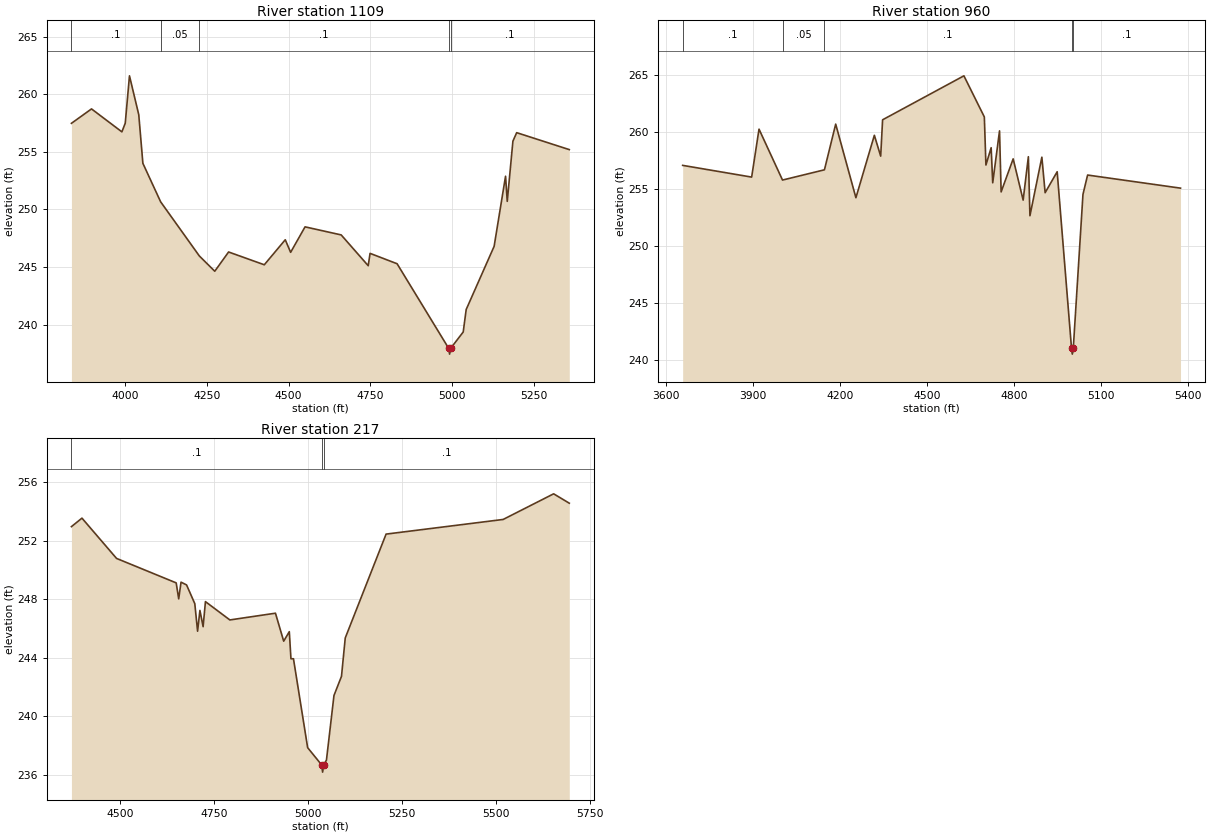
Type RM Length L Ch R = 1,1109,149,149,149
BEGIN DESCRIPTION:
UNT042 IN SUCR 2.0
END DESCRIPTION:
XS GIS Cut Line= 6
      2267705.63     13407516.33      2267608.29     13407132.11
      2267490.45     13406947.66      2267049.82     13406717.10
      2266819.26     13406655.61      2266727.04     13406799.06
#Sta/Elev= 30
  3836.0  257.47  3897.4  258.72  3990.2  256.73  4000.5  257.48  4013.4  261.59
  4041.8  258.22  4054.4  254.00  4108.7  250.66  4227.1  245.96  4274.1  244.64
  4316.4  246.31  4425.5  245.20  4489.6  247.37  4506.0  246.28  4550.1  248.49
  4660.5  247.79  4743.1  245.12  4748.8  246.19  4831.4  245.29  4989.1  237.95
  4991.9  237.45  4995.1  237.95  5033.5  239.37  5042.6  241.32  5128.0  246.80
  5162.9  252.88  5168.1  250.70  5185.4  255.92  5196.9  256.66  5357.7  255.19
#Mann=5,-1,0
  3836.0     0.1       0  4108.7    0.05       0  4227.1     0.1       0
  4989.1    0.07       0  4995.1     0.1       0
Bank Sta=4989.1,4995.1
Exp/Cntr=0.3,0.1

Type RM Length L Ch R = 1,960,743,743,743
BEGIN DESCRIPTION:
Mapping XS 87b8f532
END DESCRIPTION:
XS GIS Cut Line= 6
      2267777.37     13407475.36      2267710.77     13407126.99
      2267674.90     13406957.91      2267469.96     13406778.58
      2266819.26     13406496.78      2266686.07     13406655.58
#Sta/Elev= 30
  3658.5  257.08  3896.3  256.05  3921.7  260.26  4002.7  255.79  4147.2  256.69
  4186.0  260.70  4255.7  254.24  4319.3  259.72  4341.1  257.89  4347.7  261.08
  4628.0  264.94  4698.4  261.33  4703.9  257.11  4721.9  258.63  4727.3  255.55
  4750.8  260.11  4756.3  254.75  4797.8  257.65  4832.2  254.03  4850.2  257.84
  4855.6  252.66  4896.7  257.80  4908.0  254.68  4949.5  256.52  4999.0  241.01
  5001.7  240.51  5005.0  241.01  5038.4  254.53  5054.4  256.23  5374.7  255.08
#Mann=5,-1,0
  3658.5     0.1       0  4002.7    0.05       0  4147.2     0.1       0
  4999.0    0.07       0  5005.0     0.1       0
Bank Sta=4999,5005
Exp/Cntr=0.3,0.1

Type RM Length L Ch R = 1,217,0,0,0
BEGIN DESCRIPTION:
UNT042 IN SUCR 1.0
END DESCRIPTION:
XS GIS Cut Line= 5
      2267630.96     13406512.08      2267374.87     13406160.49
      2267288.06     13406034.63      2267114.73     13406036.97
      2266724.21     13406442.21
#Sta/Elev= 30
  4371.0  252.95  4399.0  253.53  4491.0  250.78  4649.6  249.11  4656.3  248.02
  4662.5  249.16  4677.2  248.97  4699.1  247.69  4706.5  245.81  4712.7  247.23
  4721.2  246.12  4727.4  247.83  4792.3  246.58  4913.6  247.04  4935.5  245.13
  4950.4  245.78  4954.8  243.93  4961.5  243.93  4999.2  237.86  5036.2  236.69
  5039.0  236.19  5042.2  236.69  5049.2  237.01  5069.2  241.42  5089.2  242.73
  5099.2  245.35  5207.8  252.44  5519.1  253.44  5653.4  255.19  5695.0  254.55
#Mann=3,-1,0
  4371.0     0.1       0  5036.2    0.07       0  5042.2     0.1       0
Bank Sta=5036.2,5042.2
Exp/Cntr=0.3,0.1

Chan Stop Cuts=-1