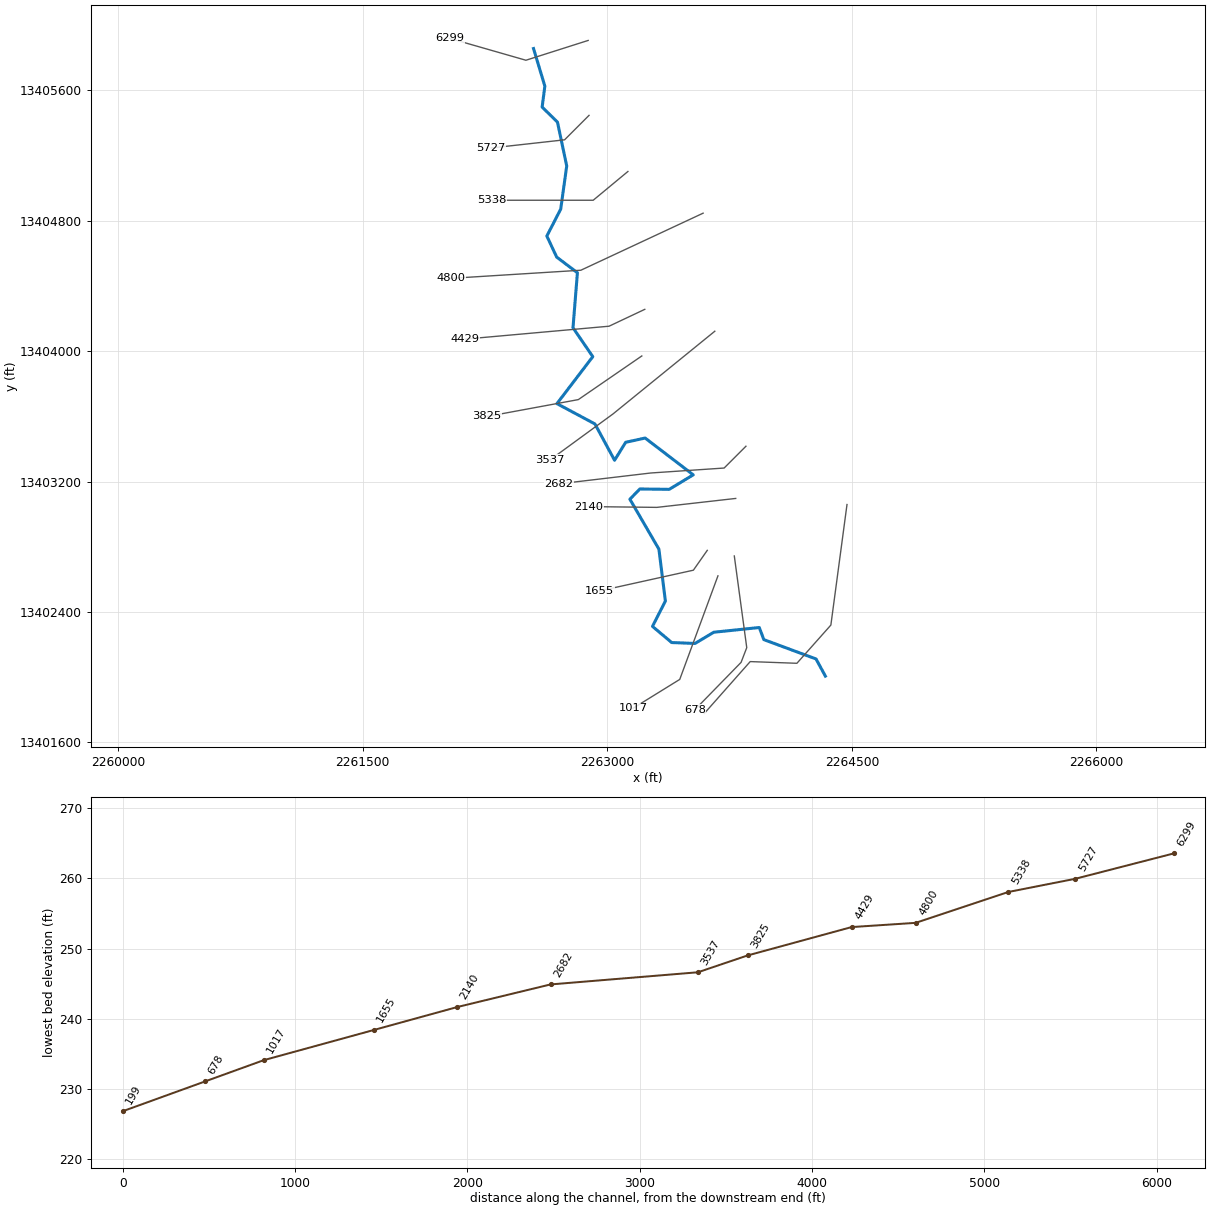
--- UNT043 IN SUCR.prj (project) ---

Proj Title=UNT043 IN SUCR Base Level Engineering
Current Plan=p01
Default Exp/Contr=0.3,0.1
English Units
Geom File=g01
Flow File=f01
Plan File=p01
BEGIN DESCRIPTION:
UNT043 IN SUCR
END DESCRIPTION:

--- UNT043 IN SUCR.p01 (plan) ---

Plan Title=Multiple Run
Short Identifier=Multiple
Geom File=g01
Flow File=f01
Subcritical Flow
K Sum by GR= 0
Std Step Tol= 0.01
Critical Tol= 0.01
Num of Std Step Trials= 20
Max Error Tol= 0.3
Flow Tol Ratio= 0.001
Split Flow NTrial= 30
Split Flow Tol= 0.02
Split Flow Ratio= 0.02
Log Output Level= 0
Friction Slope Method= 1
Unsteady Friction Slope Method= 2
Unsteady Bridges Friction Slope Method= 1
Parabolic Critical Depth
Global Vel Dist=  1 , 1 , 1
Global Log Level= 0
CheckData=True
Encroach Param= -1, 0, 0, 0
BEGIN DESCRIPTION:
Multiple Run
END DESCRIPTION:

--- UNT043 IN SUCR.f01 (steady flow) ---

Flow Title=Multiple
Number of Profiles=7
Profile Names=10-year,25-year,50-year,1pct_min,100-year,1pct_plu,500-year
River Rch & RM= UNT043 IN SUCR,Reach-1,6299
     192     264     322     290     393     531     591
River Rch & RM= UNT043 IN SUCR,Reach-1,4800
     308     433     539     493     666     901    1035
Boundary for River Rch & Prof#=UNT043 IN SUCR,Reach-1,1
Up Type=0
Dn Type=3
Dn Slope=0.005
Boundary for River Rch & Prof#=UNT043 IN SUCR,Reach-1,2
Up Type=0
Dn Type=3
Dn Slope=0.005
Boundary for River Rch & Prof#=UNT043 IN SUCR,Reach-1,3
Up Type=0
Dn Type=3
Dn Slope=0.005
Boundary for River Rch & Prof#=UNT043 IN SUCR,Reach-1,4
Up Type=0
Dn Type=3
Dn Slope=0.005
Boundary for River Rch & Prof#=UNT043 IN SUCR,Reach-1,5
Up Type=0
Dn Type=3
Dn Slope=0.005
Boundary for River Rch & Prof#=UNT043 IN SUCR,Reach-1,6
Up Type=0
Dn Type=3
Dn Slope=0.005
Boundary for River Rch & Prof#=UNT043 IN SUCR,Reach-1,7
Up Type=0
Dn Type=3
Dn Slope=0.005

--- UNT043 IN SUCR.g01 (geometry) ---

Geom Title=Existing Conditions

River Reach=UNT043 IN SUCR,Reach-1
Reach XY= 30
      2262547.19     13405856.93      2262616.71     13405626.33
      2262600.15     13405497.76      2262694.13     13405405.46
      2262750.94     13405136.48      2262714.15     13404872.15
      2262628.98     13404706.45      2262689.42     13404577.29
      2262816.53     13404481.49      2262789.40     13404143.95
      2262910.88     13403966.61      2262690.91     13403678.47
      2262924.12     13403553.75      2263044.46     13403331.08
      2263112.64     13403441.29      2263232.00     13403467.33
      2263527.14     13403241.64      2263379.57     13403152.66
      2263199.45     13403154.83      2263138.49     13403092.16
      2263316.51     13402785.53      2263356.21     13402467.26
      2263277.00     13402311.84      2263394.95     13402212.81
      2263537.70     13402207.27      2263653.02     13402275.98
      2263932.28     13402304.94      2263960.08     13402230.81
      2264280.38     13402112.04      2264337.72     13402006.85

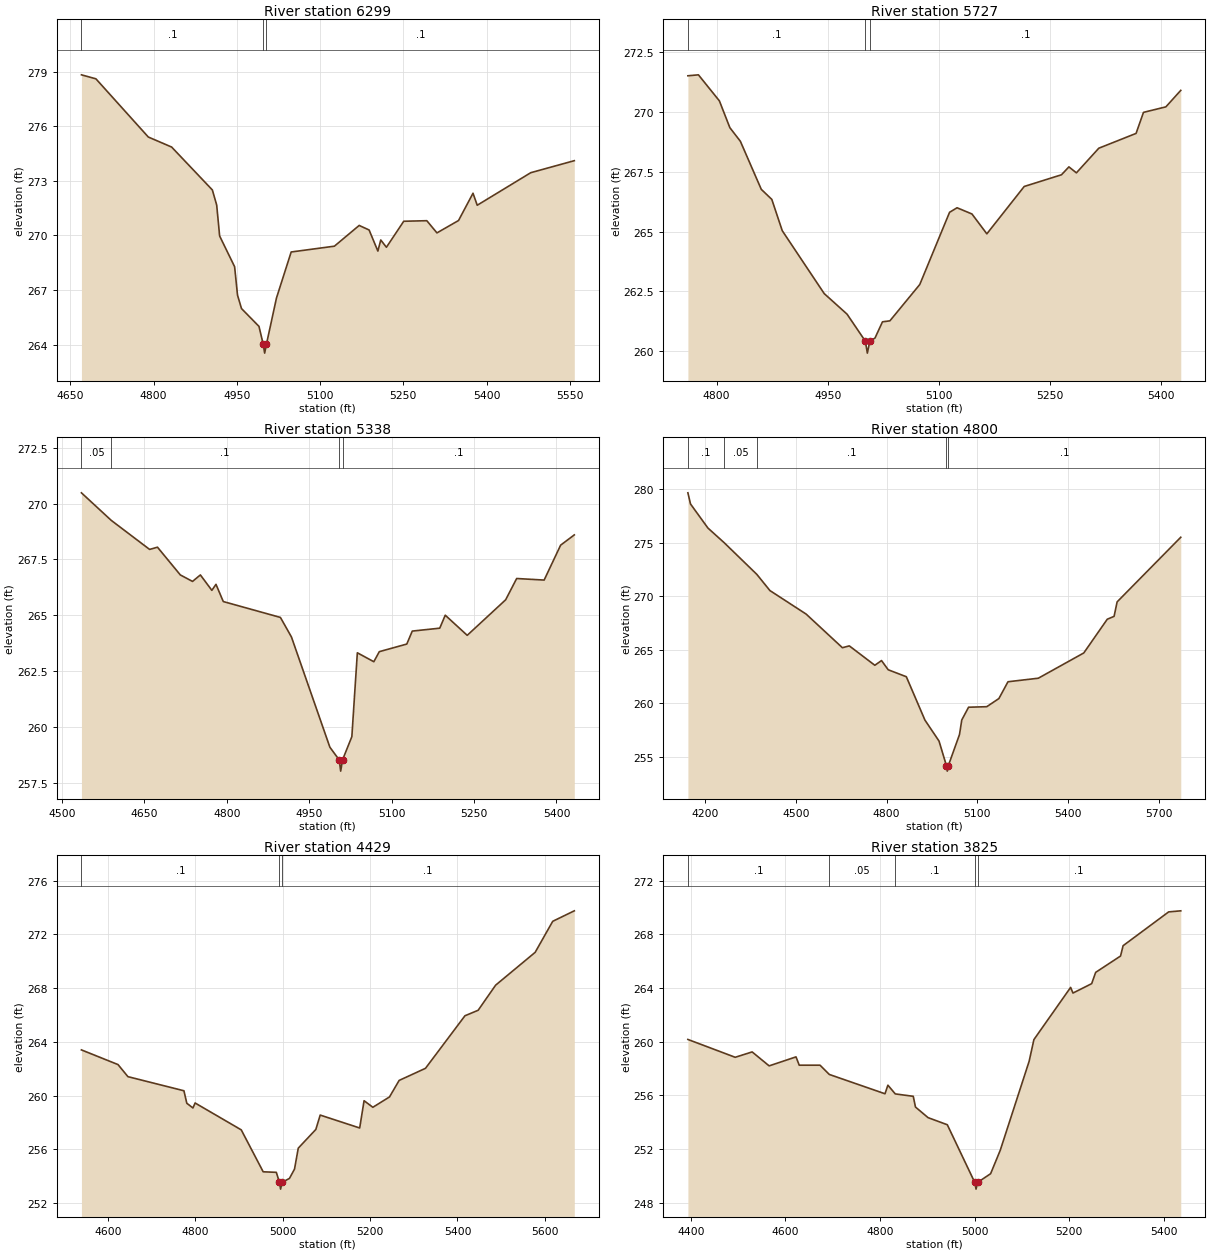
Type RM Length L Ch R = 1,6299,572,572,572
BEGIN DESCRIPTION:
UNT043 IN SUCR 11.0
END DESCRIPTION:
XS GIS Cut Line= 3
      2262882.55     13405906.54      2262500.63     13405785.02
      2262032.33     13405919.43
#Sta/Elev= 30
  4670.1  278.83  4696.2  278.61  4790.6  275.41  4832.6  274.86  4906.0  272.50
  4913.8  271.67  4919.1  269.97  4946.1  268.28  4951.3  266.72  4958.5  265.98
  4990.0  265.00  4997.5  264.03  5000.2  263.53  5003.5  264.03  5021.5  266.56
  5048.0  269.09  5125.9  269.41  5170.5  270.55  5188.4  270.30  5204.2  269.14
  5209.4  269.75  5219.6  269.35  5250.8  270.78  5292.4  270.81  5310.6  270.14
  5349.5  270.82  5375.6  272.32  5383.2  271.66  5479.7  273.45  5558.1  274.11
#Mann=3,-1,0
  4670.1     0.1       0  4997.5    0.07       0  5003.5     0.1       0
Bank Sta=4997.5,5003.5
Exp/Cntr=0.3,0.1

Type RM Length L Ch R = 1,5727,389,389,389
BEGIN DESCRIPTION:
UNT043 IN SUCR 10.0
END DESCRIPTION:
XS GIS Cut Line= 3
      2262887.75     13405446.89      2262737.72     13405296.85
      2262287.77     13405246.86
#Sta/Elev= 30
  4761.4  271.52  4775.6  271.56  4803.9  270.47  4818.0  269.35  4832.2  268.78
  4860.4  266.77  4874.6  266.35  4888.7  265.04  4945.3  262.41  4976.1  261.55
  5000.8  260.42  5003.5  259.92  5006.8  260.42  5013.8  260.55  5023.9  261.23
  5033.9  261.27  5074.2  262.79  5114.4  265.81  5124.5  266.00  5144.6  265.74
  5164.7  264.91  5215.1  266.89  5265.4  267.38  5275.4  267.71  5285.5  267.46
  5315.7  268.49  5366.0  269.11  5376.0  269.99  5406.2  270.22  5426.3  270.91
#Mann=3,-1,0
  4761.4     0.1       0  5000.8    0.07       0  5006.8     0.1       0
Bank Sta=5000.8,5006.8
Exp/Cntr=0.3,0.1

Type RM Length L Ch R = 1,5338,538,538,538
BEGIN DESCRIPTION:
UNT043 IN SUCR 9.0
END DESCRIPTION:
XS GIS Cut Line= 3
      2263126.32     13405102.61      2262913.39     13404926.18
      2262292.82     13404926.18
#Sta/Elev= 30
  4535.4  270.48  4589.6  269.25  4659.5  267.95  4673.8  268.05  4715.4  266.81
  4737.6  266.52  4751.9  266.81  4772.8  266.12  4780.3  266.39  4793.6  265.62
  4897.6  264.91  4917.6  264.04  4987.6  259.11  5004.6  258.54  5007.3  258.04
  5010.6  258.54  5027.6  259.58  5037.6  263.33  5067.6  262.93  5077.6  263.38
  5127.6  263.72  5137.6  264.30  5187.6  264.43  5197.6  265.01  5237.6  264.11
  5307.6  265.70  5327.6  266.65  5377.6  266.58  5407.6  268.14  5432.5  268.60
#Mann=4,-1,0
  4535.4    0.05       0  4589.6     0.1       0  5004.6    0.07       0
  5010.6     0.1       0
Bank Sta=5004.6,5010.6
Exp/Cntr=0.3,0.1

Type RM Length L Ch R = 1,4800,371,371,371
BEGIN DESCRIPTION:
UNT043 IN SUCR 8.0
END DESCRIPTION:
XS GIS Cut Line= 3
      2263587.70     13404846.84      2262837.72     13404496.85
      2262037.70     13404446.85
#Sta/Elev= 30
  4143.3  279.65  4151.9  278.61  4209.5  276.36  4263.6  274.98  4371.2  272.03
  4414.4  270.52  4534.2  268.32  4654.0  265.18  4676.9  265.35  4761.2  263.54
  4783.3  263.98  4805.4  263.12  4865.3  262.47  4926.8  258.42  4973.4  256.46
  4998.0  254.15  5000.7  253.65  5004.0  254.15  5041.1  257.07  5048.6  258.43
  5071.1  259.62  5131.2  259.67  5171.3  260.43  5201.4  262.00  5301.6  262.33
  5451.9  264.69  5529.5  267.84  5552.1  268.11  5562.1  269.46  5772.5  275.50
#Mann=5,-1,0
  4143.3     0.1       0  4263.6    0.05       0  4371.2     0.1       0
  4998.0    0.07       0  5004.0     0.1       0
Bank Sta=4998,5004
Exp/Cntr=0.3,0.1

Type RM Length L Ch R = 1,4429,604,604,604
BEGIN DESCRIPTION:
UNT043 IN SUCR 7.0
END DESCRIPTION:
XS GIS Cut Line= 3
      2263229.83     13404256.90      2263010.75     13404153.44
      2262128.47     13404074.34
#Sta/Elev= 30
  4539.3  263.41  4623.0  262.32  4645.7  261.42  4773.9  260.37  4780.5  259.44
  4794.5  259.09  4799.5  259.46  4905.1  257.46  4955.3  254.34  4985.4  254.30
  4992.5  253.55  4995.2  253.05  4998.5  253.55  5015.5  253.85  5027.0  254.54
  5035.6  256.10  5075.8  257.49  5085.8  258.56  5176.2  257.60  5186.2  259.63
  5206.3  259.14  5244.4  259.91  5266.5  261.14  5326.8  262.04  5417.1  265.95
  5447.3  266.36  5487.4  268.23  5577.8  270.67  5618.0  272.98  5667.4  273.76
#Mann=3,-1,0
  4539.3     0.1       0  4992.5    0.07       0  4998.5     0.1       0
Bank Sta=4992.5,4998.5
Exp/Cntr=0.3,0.1

Type RM Length L Ch R = 1,3825,288,288,288
BEGIN DESCRIPTION:
UNT043 IN SUCR 6.0
END DESCRIPTION:
XS GIS Cut Line= 3
      2263211.58     13403970.93      2262822.13     13403703.18
      2262262.51     13403599.78
#Sta/Elev= 30
  4393.8  260.17  4493.8  258.84  4529.6  259.24  4565.5  258.20  4622.3  258.87
  4629.1  258.25  4673.1  258.25  4692.7  257.56  4810.4  256.12  4816.5  256.76
  4832.1  256.11  4870.1  255.93  4874.8  255.13  4901.4  254.34  4942.1  253.81
  5000.1  249.51  5002.8  249.01  5006.1  249.51  5033.6  250.16  5053.9  251.90
  5115.0  258.54  5125.1  260.16  5202.7  264.05  5207.7  263.63  5247.2  264.33
  5255.6  265.17  5308.2  266.39  5313.6  267.16  5409.9  269.68  5435.5  269.76
#Mann=5,-1,0
  4393.8     0.1       0  4692.7    0.05       0  4832.1     0.1       0
  5000.1    0.07       0  5006.1     0.1       0
Bank Sta=5000.1,5006.1
Exp/Cntr=0.3,0.1

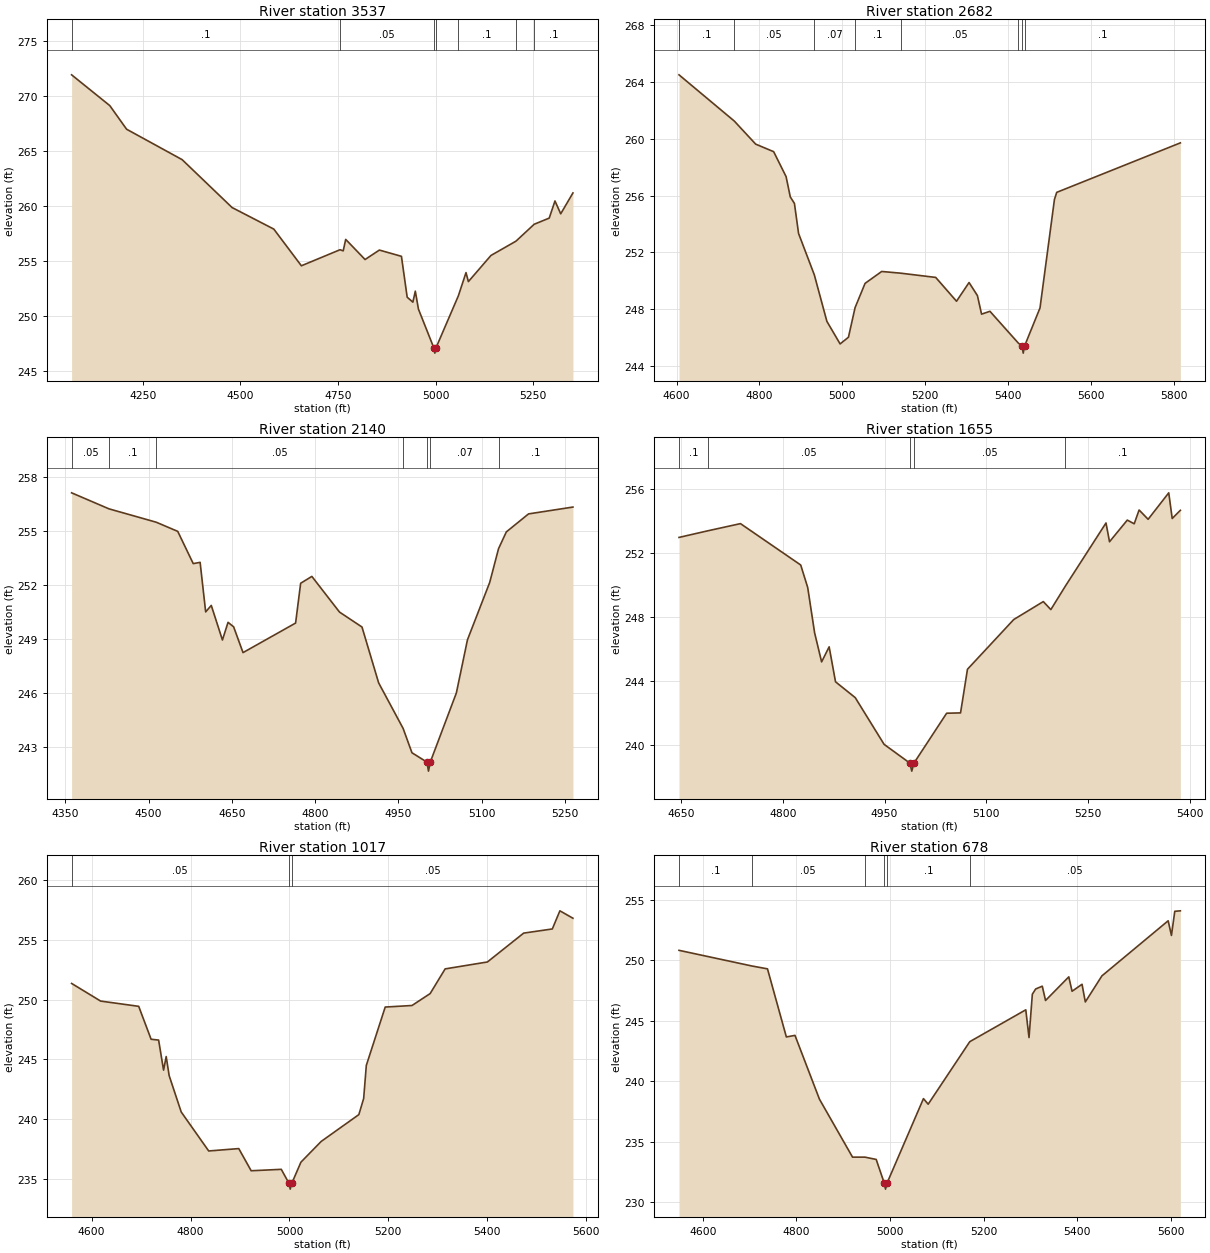
Type RM Length L Ch R = 1,3537,855,855,855
BEGIN DESCRIPTION:
Mapping XS 7657293f
END DESCRIPTION:
XS GIS Cut Line= 3
      2263659.49     13404122.70      2263034.48     13403614.88
      2262648.23     13403332.79
#Sta/Elev= 30
  4067.8  271.95  4165.5  269.15  4208.6  267.00  4350.8  264.23  4478.7  259.87
  4585.5  257.91  4656.1  254.57  4755.0  256.03  4763.2  255.93  4769.6  256.97
  4819.2  255.14  4855.8  256.00  4912.3  255.43  4927.0  251.71  4941.6  251.26
  4947.8  252.26  4955.8  250.63  4995.0  247.12  4997.8  246.62  5001.0  247.12
  5058.1  251.84  5077.6  253.95  5083.7  253.13  5141.5  255.51  5205.5  256.81
  5252.2  258.35  5290.7  258.91  5305.4  260.47  5320.1  259.30  5351.4  261.20
#Mann=7,-1,0
  4067.8     0.1       0  4755.0    0.05       0  4995.0    0.03       0
  5001.0    0.05       0  5058.1     0.1       0  5205.5    0.05       0
  5252.2     0.1       0
Bank Sta=4995,5001
Exp/Cntr=0.3,0.1

Type RM Length L Ch R = 1,2682,542,542,542
BEGIN DESCRIPTION:
Mapping XS c494dad1
END DESCRIPTION:
XS GIS Cut Line= 4
      2263850.44     13403417.23      2263716.56     13403283.35
      2263266.30     13403252.92      2262701.56     13403186.13
#Sta/Elev= 30
  4606.0  264.52  4739.3  261.26  4791.0  259.63  4834.3  259.10  4864.3  257.34
  4874.4  255.91  4884.4  255.45  4894.4  253.33  4932.4  250.41  4962.7  247.13
  4994.6  245.54  5014.7  246.01  5030.7  248.10  5054.8  249.81  5094.9  250.65
  5140.4  250.53  5225.2  250.23  5275.4  248.55  5305.6  249.87  5325.8  248.95
  5335.8  247.64  5356.0  247.84  5424.4  245.60  5433.5  245.39  5436.3  244.89
  5439.5  245.39  5476.8  248.08  5511.6  255.73  5517.1  256.23  5815.3  259.72
#Mann=8,-1,0
  4606.0     0.1       0  4739.3    0.05       0  4932.4    0.07       0
  5030.7     0.1       0  5140.4    0.05       0  5424.4     0.1       0
  5433.5    0.07       0  5439.5     0.1       0
Bank Sta=5433.5,5439.5
Exp/Cntr=0.3,0.1

Type RM Length L Ch R = 1,2140,485,485,485
BEGIN DESCRIPTION:
UNT043 IN SUCR 4.0
END DESCRIPTION:
XS GIS Cut Line= 3
      2263787.72     13403096.85      2263303.58     13403041.96
      2262887.75     13403046.85
#Sta/Elev= 30
  4361.2  257.12  4428.6  256.23  4513.5  255.49  4552.4  254.98  4580.3  253.19
  4592.7  253.26  4602.7  250.51  4612.8  250.87  4632.9  248.95  4643.0  249.93
  4653.1  249.68  4670.0  248.25  4764.7  249.89  4773.8  252.10  4794.0  252.48
  4843.8  250.50  4884.3  249.67  4914.3  246.57  4958.4  244.04  4974.3  242.69
  5001.3  242.17  5004.1  241.67  5007.3  242.17  5054.3  246.01  5074.3  248.96
  5114.3  252.14  5130.3  254.02  5144.3  254.95  5184.3  255.95  5264.3  256.33
#Mann=7,-1,0
  4361.2    0.05       0  4428.6     0.1       0  4513.5    0.05       0
  4958.4    0.07       0  5001.3    0.07       0  5007.3    0.07       0
  5130.3     0.1       0
Bank Sta=5001.3,5007.3
Exp/Cntr=0.3,0.1

Type RM Length L Ch R = 1,1655,638,638,638
BEGIN DESCRIPTION:
UNT043 IN SUCR 3.0
END DESCRIPTION:
XS GIS Cut Line= 3
      2263613.09     13402778.29      2263527.94     13402656.64
      2262951.35     13402529.18
#Sta/Elev= 30
  4647.1  252.97  4689.3  253.38  4737.7  253.83  4826.5  251.25  4836.8  249.85
  4847.0  247.02  4857.3  245.21  4868.4  246.15  4877.8  243.97  4906.9  242.98
  4949.4  240.07  4987.4  238.90  4990.2  238.40  4993.4  238.90  5041.6  242.01
  5062.1  242.03  5072.3  244.75  5140.5  247.85  5184.1  248.97  5195.2  248.47
  5216.4  249.92  5276.5  253.87  5281.7  252.70  5307.9  254.05  5318.1  253.82
  5325.3  254.68  5338.6  254.10  5369.0  255.75  5374.1  254.15  5386.1  254.66
#Mann=5,-1,0
  4647.1     0.1       0  4689.3    0.05       0  4987.4    0.03       0
  4993.4    0.05       0  5216.4     0.1       0
Bank Sta=4987.4,4993.4
Exp/Cntr=0.3,0.1

Type RM Length L Ch R = 1,1017,339,339,339
BEGIN DESCRIPTION:
UNT043 IN SUCR 2.0
END DESCRIPTION:
XS GIS Cut Line= 3
      2263678.67     13402621.98      2263444.31     13401986.59
      2263157.85     13401809.51
#Sta/Elev= 30
  4559.4  251.36  4618.2  249.88  4695.1  249.44  4720.2  246.68  4735.4  246.61
  4745.4  244.09  4750.7  245.23  4756.7  243.63  4781.1  240.58  4836.7  237.31
  4897.5  237.51  4922.6  235.65  4983.5  235.77  4998.9  234.61  5001.6  234.11
  5004.9  234.61  5023.2  236.37  5064.2  238.11  5140.4  240.36  5150.1  241.71
  5155.5  244.49  5193.7  249.38  5247.9  249.51  5284.6  250.51  5314.9  252.58
  5400.4  253.16  5473.7  255.58  5531.7  255.93  5547.0  257.45  5573.4  256.83
#Mann=3,-1,0
  4559.4    0.05       0  4998.9    0.03       0  5004.9    0.05       0
Bank Sta=4998.9,5004.9
Exp/Cntr=0.3,0.1

Type RM Length L Ch R = 1,678,479,479,479
BEGIN DESCRIPTION:
UNT043 IN SUCR 5.0
END DESCRIPTION:
XS GIS Cut Line= 4
      2263778.97     13402744.01      2263855.36     13402181.50
      2263820.64     13402091.23      2263537.03     13401800.70
#Sta/Elev= 30
  4549.4  250.81  4704.6  249.52  4738.3  249.28  4778.6  243.66  4797.0  243.79
  4849.3  238.52  4919.9  233.74  4946.3  233.74  4970.4  233.55  4987.6  231.60
  4990.3  231.10  4993.6  231.60  5071.3  238.57  5081.4  238.11  5170.2  243.27
  5289.8  245.90  5296.7  243.61  5303.8  247.19  5310.9  247.62  5325.0  247.85
  5332.0  246.67  5381.6  248.62  5388.6  247.43  5409.9  248.01  5416.9  246.55
  5452.3  248.70  5593.8  253.25  5600.8  252.04  5607.9  254.03  5619.8  254.07
#Mann=6,-1,0
  4549.4     0.1       0  4704.6    0.05       0  4946.3     0.1       0
  4987.6    0.07       0  4993.6     0.1       0  5170.2    0.05       0
Bank Sta=4987.6,4993.6
Exp/Cntr=0.3,0.1

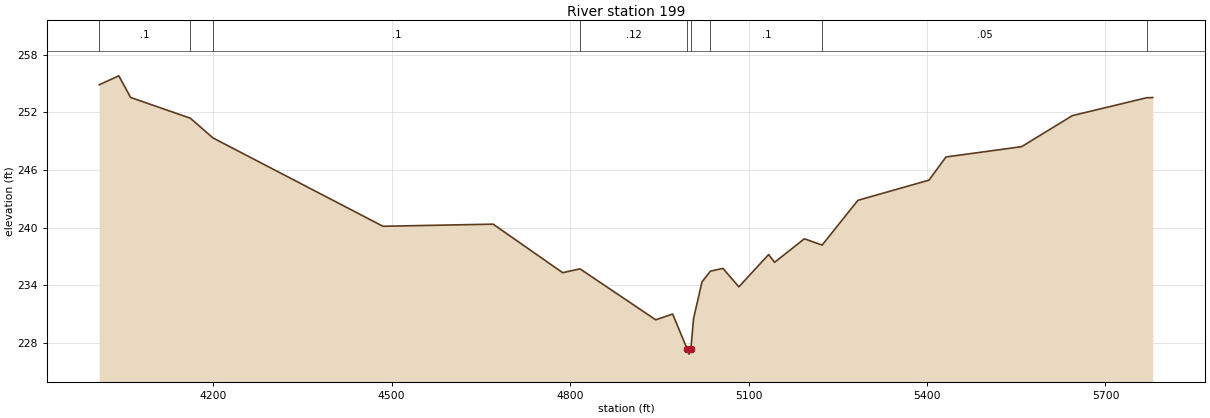
Type RM Length L Ch R = 1,199,0,0,0
BEGIN DESCRIPTION:
UNT043 IN SUCR 1.0
END DESCRIPTION:
XS GIS Cut Line= 5
      2264470.35     13403059.50      2264371.39     13402319.93
      2264163.06     13402085.55      2263876.60     13402095.97
      2263595.36     13401778.27
#Sta/Elev= 30
  4008.7  254.87  4041.6  255.80  4061.5  253.55  4161.9  251.39  4199.9  249.34
  4485.6  240.15  4670.8  240.37  4787.7  235.32  4816.8  235.72  4944.1  230.42
  4972.5  231.02  4997.1  227.35  4999.9  226.85  5003.1  227.35  5007.6  230.54
  5021.8  234.37  5036.0  235.48  5057.0  235.77  5083.8  233.85  5133.8  237.21
  5143.8  236.40  5193.9  238.85  5223.7  238.19  5283.9  242.85  5403.4  244.95
  5431.9  247.36  5559.0  248.43  5644.3  251.66  5769.2  253.52  5779.4  253.54
#Mann=9,-1,0
  4008.7     0.1       0  4161.9    0.05       0  4199.9     0.1       0
  4816.8    0.12       0  4997.1    0.07       0  5003.1    0.12       0
  5036.0     0.1       0  5223.7    0.05       0  5769.2     0.1       0
Bank Sta=4997.1,5003.1
Exp/Cntr=0.3,0.1

Chan Stop Cuts=-1