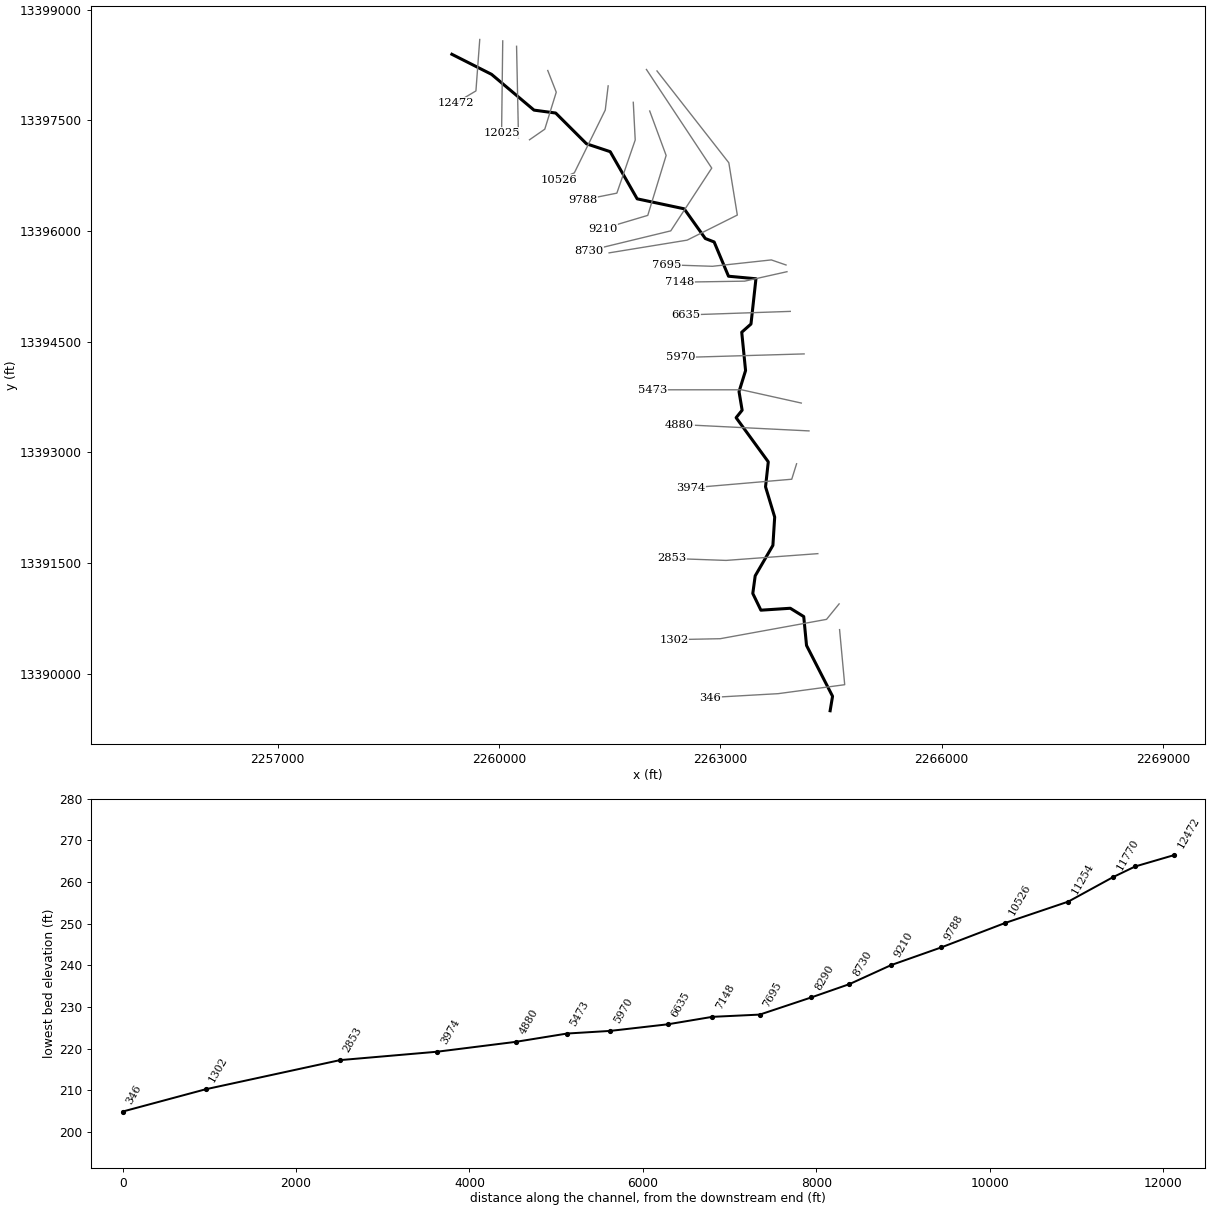
--- UNT044 IN SUCR.prj (project) ---

Proj Title=UNT044 IN SUCR Base Level Engineering
Current Plan=p01
Default Exp/Contr=0.3,0.1
English Units
Geom File=g01
Flow File=f01
Plan File=p01
Y Axis Title=Elevation
X Axis Title(PF)=Main Channel Distance
X Axis Title(XS)=Station
BEGIN DESCRIPTION:
UNT044 IN SUCR
END DESCRIPTION:
DSS Export Rating Curves= 0
DSS Export Rating Curve Sorted= 0
DSS Export Volume Flow Curves= 0
DXF OffsetX= 0
DXF OffsetY= 0
DXF ScaleX= 1
DXF ScaleY= 10

--- UNT044 IN SUCR.p01 (plan) ---

Plan Title=Multiple Run
Short Identifier=Multiple
Geom File=g01
Flow File=f01
Subcritical Flow
K Sum by GR= 0
Std Step Tol= 0.01
Critical Tol= 0.01
Num of Std Step Trials= 20
Max Error Tol= 0.3
Flow Tol Ratio= 0.001
Split Flow NTrial= 30
Split Flow Tol= 0.02
Split Flow Ratio= 0.02
Log Output Level= 0
Friction Slope Method= 1
Unsteady Friction Slope Method= 2
Unsteady Bridges Friction Slope Method= 1
Parabolic Critical Depth
Global Vel Dist=  1 , 1 , 1
Global Log Level= 0
CheckData=True
Encroach Param= -1, 0, 0, 0
BEGIN DESCRIPTION:
Multiple Run
END DESCRIPTION:

--- UNT044 IN SUCR.f01 (steady flow) ---

Flow Title=Multiple
Program Version=4.10
Number of Profiles= 7
Profile Names=10-year,25-year,50-year,1pct_min,100-year,1pct_plu,500-year
River Rch & RM=UNT044 IN SUCR,Reach-1         ,12472
     163     221     268     240     324     438     481
River Rch & RM=UNT044 IN SUCR,Reach-1         ,11770
     193     265     323     291     393     532     590
River Rch & RM=UNT044 IN SUCR,Reach-1         ,7148
     288     402     497     452     612     827     939
River Rch & RM=UNT044 IN SUCR,Reach-1         ,2853
     312     438     542     494     669     904    1031
Boundary for River Rch & Prof#=UNT044 IN SUCR,Reach-1         , 1
Up Type= 0
Dn Type= 3
Dn Slope=0.0057
Boundary for River Rch & Prof#=UNT044 IN SUCR,Reach-1         , 2
Up Type= 0
Dn Type= 3
Dn Slope=0.0057
Boundary for River Rch & Prof#=UNT044 IN SUCR,Reach-1         , 3
Up Type= 0
Dn Type= 3
Dn Slope=0.0057
Boundary for River Rch & Prof#=UNT044 IN SUCR,Reach-1         , 4
Up Type= 0
Dn Type= 3
Dn Slope=0.0057
Boundary for River Rch & Prof#=UNT044 IN SUCR,Reach-1         , 5
Up Type= 0
Dn Type= 3
Dn Slope=0.0057
Boundary for River Rch & Prof#=UNT044 IN SUCR,Reach-1         , 6
Up Type= 0
Dn Type= 3
Dn Slope=0.0057
Boundary for River Rch & Prof#=UNT044 IN SUCR,Reach-1         , 7
Up Type= 0
Dn Type= 3
Dn Slope=0.0057
DSS Import GetInterval= 0
DSS Import GetPeak= 0
DSS Import FillOption= 0

--- UNT044 IN SUCR.g01 (geometry) ---

Geom Title=Existing Conditions
Program Version=4.10

River Reach=UNT044 IN SUCR  ,Reach-1
Reach XY= 30
      2259359.89     13398394.31      2259897.54     13398122.49
      2260473.33     13397637.38      2260767.14     13397597.91
      2261185.02     13397180.86      2261506.15     13397074.27
      2261871.73     13396435.06      2262508.67     13396299.98
      2262795.43     13395897.19      2262915.12     13395850.38
        2263110.     13395386.12      2263481.96     13395351.76
       2263414.7     13394738.06       2263289.3     13394627.01
       2263341.2     13394107.52       2263252.7     13393821.83
      2263294.68     13393570.34      2263213.08     13393468.77
      2263649.18     13392870.29      2263611.97     13392531.98
      2263736.04     13392121.83      2263711.78     13391738.45
      2263471.82     13391325.37      2263439.11     13391086.51
      2263548.93     13390859.79      2263947.67     13390885.81
      2264129.87     13390773.12      2264167.68     13390381.55
      2264520.46     13389692.86      2264487.72     13389496.86

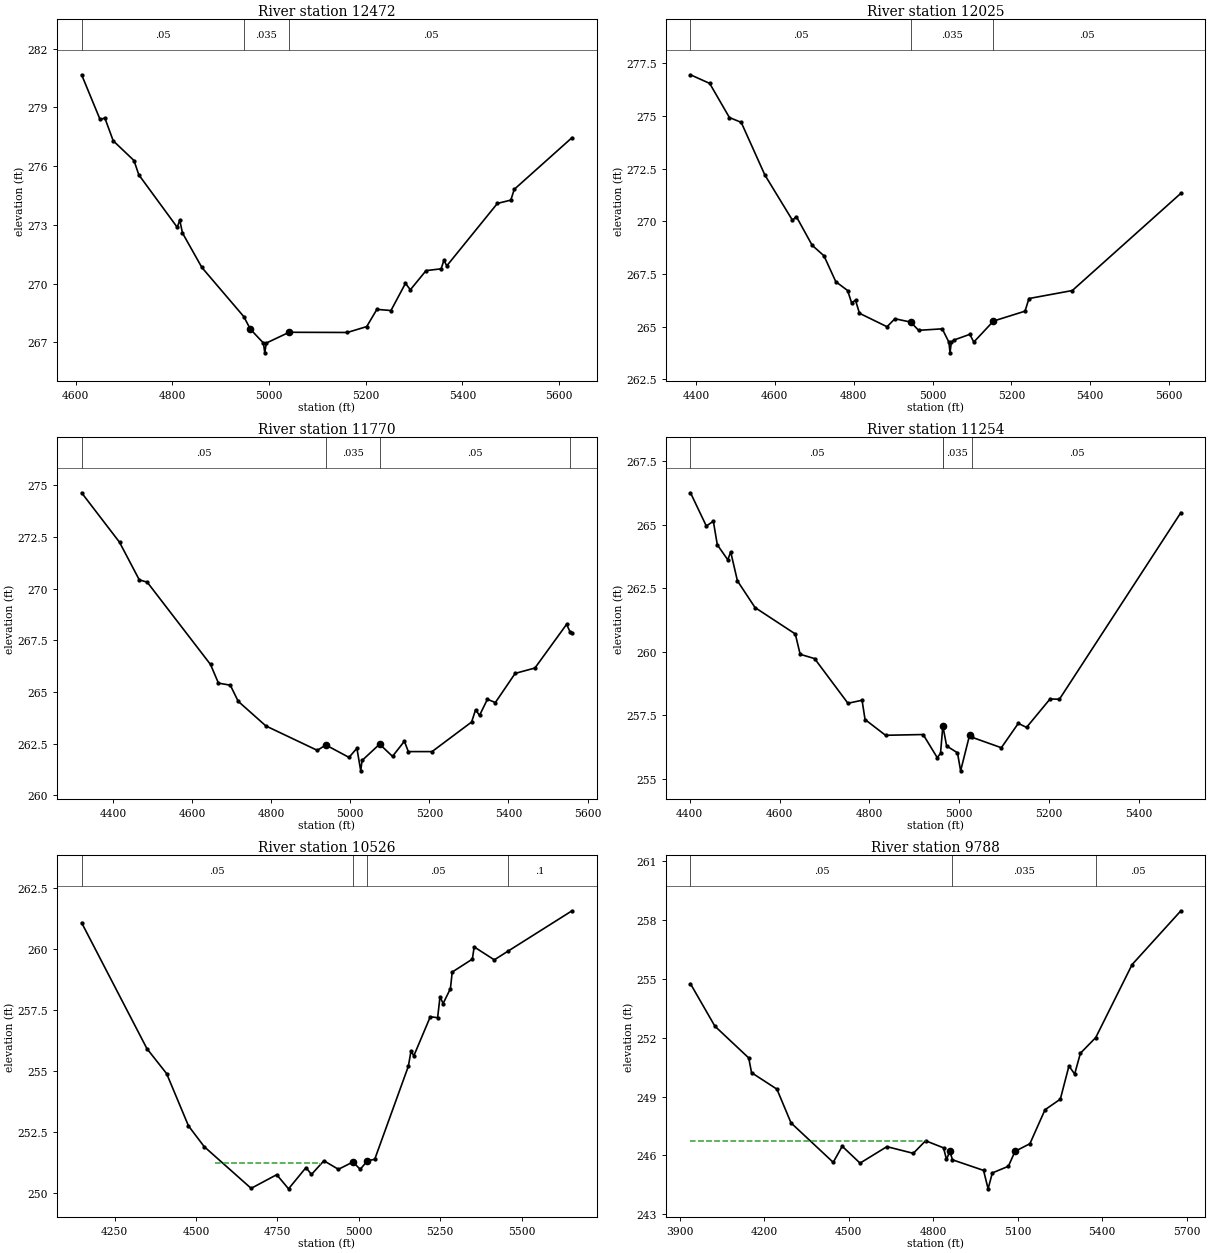
Type RM Length L Ch R = 1 ,12472   ,447,447,447
BEGIN DESCRIPTION:
UNT044 IN SUCR 10.0
END DESCRIPTION:
XS GIS Cut Line= 3
      2259737.72     13398594.85      2259685.86     13397897.68
      2259415.06     13397736.35
#Sta/Elev= 30
  4612.3  280.67  4650.4  278.39  4660.4  278.46  4677.6   277.3  4720.6  276.29
  4730.6  275.56  4810.1  272.88  4815.2  273.25  4820.9  272.59    4861  270.83
  4947.7  268.32  4961.3  267.68  4988.3  266.97  4991.1  266.47  4994.3  266.97
  5041.5  267.52  5161.8  267.51  5201.9  267.81    5223  268.69  5252.1  268.63
  5282.1  270.02  5292.2  269.69  5324.7  270.67  5355.8  270.76  5361.7   271.2
  5367.5  270.91  5472.2   274.1    5500  274.27  5507.1  274.82  5626.6  277.46
#Mann= 3 ,-1 , 0
  4612.3     .05       0  4947.7    .035       0  5041.5     .05       0
Bank Sta=4961.3,5041.5
XS Rating Curve= 0 ,0
Exp/Cntr=0.3,0.1

Type RM Length L Ch R = 1 ,12025   ,255,255,255
BEGIN DESCRIPTION:
UNT044 IN SUCR 9.0
END DESCRIPTION:
XS GIS Cut Line= 2
      2260049.34     13398575.56      2260033.73     13397331.36
#Sta/Elev= 30
  4385.9  276.96  4434.6  276.55  4484.6  274.93  4514.6   274.7  4574.6   272.2
  4644.6  270.05  4654.6  270.22  4694.6  268.86  4724.6  268.36  4754.6  267.13
  4784.6  266.71  4794.6  266.13  4804.6  266.25  4814.6  265.63  4884.6  264.99
  4904.6  265.37  4944.7  265.21  4964.7  264.82  5024.7  264.89  5041.7  264.25
  5044.4  263.75  5047.7  264.25  5054.7  264.36  5094.7  264.63  5104.7  264.26
  5154.7  265.26  5234.7  265.73  5244.7  266.33  5354.7  266.71  5630.2  271.33
#Mann= 3 , 0 , 0
  4385.9     .05       0  4944.7    .035       0  5154.7     .05       0
Bank Sta=4944.7,5154.7
XS Rating Curve= 0 ,0
Exp/Cntr=0.3,0.1

Type RM Length L Ch R = 1 ,11770   ,516,516,516
BEGIN DESCRIPTION:
UNT044 IN SUCR 8.0
END DESCRIPTION:
XS GIS Cut Line= 2
      2260236.84     13398502.67      2260262.89     13397263.04
#Sta/Elev= 30
  4320.8  274.63  4416.6  272.24  4466.6  270.42  4486.6  270.31  4646.7  266.33
  4666.7  265.43  4696.7  265.33  4716.7  264.55  4786.7  263.36  4916.7  262.18
 4938.16  262.44  4996.8  261.84  5016.8  262.28  5026.5  261.19  5029.8  261.69
  5074.2  262.48  5106.8  261.89  5136.8  262.62  5146.8  262.12  5206.8  262.12
  5306.8  263.55  5316.8  264.14  5326.8  263.87  5346.8  264.65  5366.8  264.49
  5416.9   265.9  5466.9  266.16  5546.9  268.27  5555.7  267.91  5560.7  267.87
#Mann= 4 ,-1 , 0
  4320.8     .05       0 4938.16    .035       0  5074.2     .05       0
  5555.7     .05       0
Bank Sta=4938.16,5074.2
XS Rating Curve= 0 ,0
Exp/Cntr=0.3,0.1

Type RM Length L Ch R = 1 ,11254   ,728,728,728
BEGIN DESCRIPTION:
UNT044 IN SUCR 7.0
END DESCRIPTION:
XS GIS Cut Line= 4
      2260659.62     13398174.26      2260774.86     13397880.39
      2260619.29     13397379.11      2260412.32     13397235.38
#Sta/Elev= 30
  4401.7  266.26    4437  264.95  4452.6  265.14  4461.5  264.21  4484.8  263.62
  4491.3  263.93  4506.3  262.79  4545.5  261.74  4635.2   260.7    4646   259.9
  4678.2  259.73  4752.5  257.97  4783.9  258.09  4790.6  257.33  4836.2  256.71
    4920  256.74  4951.4  255.83  4958.7     256  4963.9  257.08  4972.3  256.29
  4996.5  256.02  5003.5  255.31  5023.8  256.74  5029.1  256.63  5094.2  256.22
    5132  257.18  5150.3  257.02  5202.7  258.14  5223.6  258.13  5494.2  265.48
#Mann= 4 ,-1 , 0
  4401.7     .05       0  4963.9      .1       0  4963.9    .035       0
  5029.1     .05       0
Bank Sta=4963.9,5023.8
XS Rating Curve= 0 ,0
Exp/Cntr=0.3,0.1

Type RM Length L Ch R = 1 ,10526   ,738,738,738
BEGIN DESCRIPTION:
UNT044 IN SUCR 6.0
END DESCRIPTION:
XS GIS Cut Line= 4
      2261478.48     13397966.11      2261439.18     13397638.59
        2261020.     13396787.15      2260811.58     13396695.96
#Sta/Elev= 30
  4148.4  261.08  4349.1  255.92  4409.5   254.9  4476.6  252.76  4524.8  251.91
  4669.1   250.2  4747.7  250.76    4784  250.18  4837.5  251.05  4854.4  250.77
  4892.6  251.33  4937.2  250.98  4981.8  251.28  5004.1  250.98  5026.4  251.33
  5048.7  251.39    5152   255.2  5160.1  255.82  5168.9  255.63  5219.4  257.23
  5241.9  257.19  5249.3  258.05  5258.8  257.77  5281.2  258.38  5286.8  259.06
  5348.6  259.59  5354.2  260.09    5416  259.56  5458.6  259.92  5654.8  261.57
#Mann= 4 ,-1 , 0
  4148.4     .05       0  4981.8    .035       0  5026.4     .05       0
  5458.6      .1       0
#XS Ineff= 1 ,-1
 4558.49 4881.13  251.24
Permanent Ineff=
       T
Bank Sta=4981.8,5026.4
XS Rating Curve= 0 ,0
Exp/Cntr=0.3,0.1

Type RM Length L Ch R = 1 ,9788    ,578,578,578
BEGIN DESCRIPTION:
UNT044 IN SUCR 5.0
END DESCRIPTION:
XS GIS Cut Line= 4
      2261819.05     13397743.36      2261845.25     13397232.52
      2261596.37     13396512.06      2261137.89     13396420.37
#Sta/Elev= 30
  3938.5  254.75  4025.1  252.59  4145.3  250.97  4155.3  250.22  4245.4  249.38
  4295.5  247.66  4445.3  245.65  4477.2  246.47  4540.6  245.61  4635.9  246.45
  4729.6  246.11  4773.4  246.75  4836.9  246.39  4847.5   245.8  4859.6  246.22
  4868.6  245.78  4979.1  245.24  4995.3   244.3  5010.2  245.11  5067.3  245.45
  5090.8  246.21  5143.7   246.6  5197.3  248.33  5251.7  248.87  5282.3  250.56
  5302.6  250.15    5323  251.21  5377.5  252.01  5506.6  255.73  5679.8  258.47
#Mann= 3 ,-1 , 0
  3938.5     .05       0  4868.6    .035       0  5377.5     .05       0
#XS Ineff= 2 , 0
       0 4774.84  246.76               0
Permanent Ineff=
       T       F
Bank Sta=4859.6,5090.8
XS Rating Curve= 0 ,0
Exp/Cntr=0.3,0.1

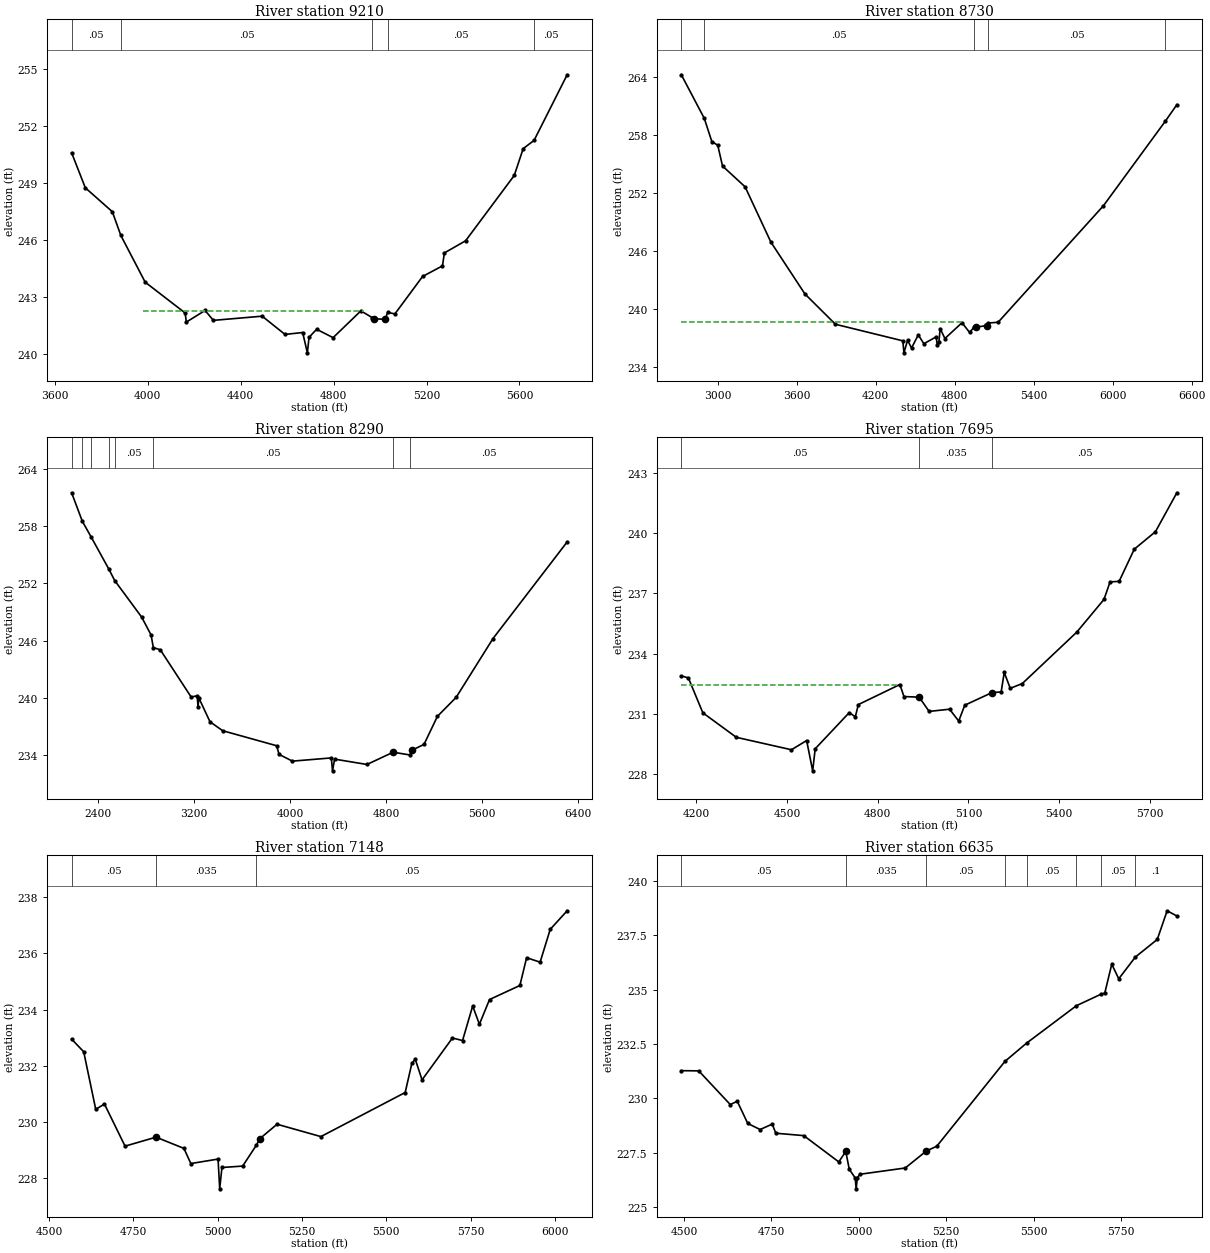
Type RM Length L Ch R = 1 ,9210    ,480,480,480
BEGIN DESCRIPTION:
UNT044 IN SUCR 4.0
END DESCRIPTION:
XS GIS Cut Line= 4
      2262041.72     13397625.54      2262264.43     13397022.93
      2262015.54     13396210.78      2261401.28     13396027.81
#Sta/Elev= 30
  3672.5  250.58  3731.4  248.74  3847.7  247.48  3884.3  246.23  3989.1  243.77
    4161  242.15  4166.3  241.67  4246.8  242.28  4282.6  241.76  4492.6  241.98
  4590.9  241.02  4666.9  241.12  4687.1  240.05  4694.4  240.87  4727.1  241.29
  4797.9  240.85  4917.5  242.26  4966.9   241.9  4972.1  241.85  5022.1  241.81
  5032.4  242.18  5063.9   242.1    5183  244.07  5268.7  244.63  5276.9  245.31
  5368.2  245.95  5577.6  249.39    5616   250.8  5663.1  251.24  5805.3  254.69
#Mann= 5 ,-1 , 0
  3672.5     .05       0  3884.3     .05       0  4966.9    .035       0
  5032.4     .05       0  5663.1     .05       0
#XS Ineff= 1 ,-1
 3979.56  4928.2  242.26
Permanent Ineff=
       T
Bank Sta=4972.1,5022.1
XS Rating Curve= 0 ,0
Exp/Cntr=0.3,0.1

Type RM Length L Ch R = 1 ,8730    ,440,440,440
BEGIN DESCRIPTION:
UNT044 IN SUCR 3.0
END DESCRIPTION:
XS GIS Cut Line= 4
      2261997.28     13398188.38      2262882.68     13396851.61
      2262327.12     13396000.92      2261216.07     13395731.83
#Sta/Elev= 30
  2725.3   264.2  2899.6   259.7  2956.7  257.31  3001.9  256.92    3038  254.78
  3209.5  252.63    3405  246.93  3663.7  241.57  3895.4  238.44  4406.9  236.73
  4415.8  235.49  4443.1  236.79  4473.3  235.99  4524.6  237.34  4566.8  236.43
  4660.3  237.14  4668.8  236.29  4681.4  236.66  4690.6  237.99  4726.8  236.97
 4856.41   238.6  4913.7   237.6    4950  238.16  4965.1  238.15  5043.4   238.3
    5051  238.56    5131  238.65  5930.5  250.68  6401.6  259.43  6487.9  261.11
#Mann= 5 ,-1 , 0
  2725.3     .05       0  2899.6     .05       0    4950    .035       0
    5051     .05       0  6401.6      .1       0
#XS Ineff= 2 , 0
       0 4856.39  238.64               0
Permanent Ineff=
       T       F
Bank Sta=4965.1,5043.4
XS Rating Curve= 0 ,0
Exp/Cntr=0.3,0.1

Type RM Length L Ch R = 1 ,8290    ,595,595,595
BEGIN DESCRIPTION:
Mapping XS 491b3c27
END DESCRIPTION:
XS GIS Cut Line= 5
      2262140.42     13398168.51      2263114.19     13396923.92
      2263229.43      13396215.2      2262549.53     13395875.25
      2261491.05     13395702.67
#Sta/Elev= 30
  2177.9  261.54  2267.1  258.54  2338.4  256.94  2488.5   253.5  2536.8  252.31
  2761.8  248.46  2840.2  246.58  2858.9  245.26  2917.3  245.02  3174.1  240.06
  3223.9  240.18    3232  239.05  3238.3  239.96  3331.5  237.45  3437.3  236.51
  3886.9  234.93  3907.2  234.02  4018.6  233.31  4342.8  233.65  4352.7  232.29
  4370.1  233.52  4640.2  232.96  4858.2  234.25    4998  233.96  5014.7  234.46
  5115.4  235.07  5227.2  238.02  5383.4  240.02  5690.8  246.21  6308.8  256.37
#Mann= 8 ,-1 , 0
  2177.9     .05       0  2267.1      .1       0  2338.4     .05       0
  2488.5      .1       0  2536.8     .05       0  2858.9     .05       0
  4858.2    .035       0    4998     .05       0
#XS Ineff= 1 ,-1
 3863.49 4856.83  234.18
Permanent Ineff=
       T
Bank Sta=4858.2,5014.7
XS Rating Curve= 0 ,0
Exp/Cntr=0.3,0.1

Type RM Length L Ch R = 1 ,7695    ,547,547,547
BEGIN DESCRIPTION:
Mapping XS 3b9916ac
END DESCRIPTION:
XS GIS Cut Line= 4
      2263889.69     13395538.57      2263690.37      13395607.2
      2262891.93      13395520.7      2262266.89     13395541.53
#Sta/Elev= 30
  4150.3  232.89  4173.5  232.79  4221.5  231.05  4332.2  229.83  4514.6  229.21
  4564.9  229.67  4584.8  228.16  4593.2  229.26  4705.8  231.06  4725.9  230.85
  4735.9  231.46  4873.3  232.46  4886.8  231.86  4937.1  231.83  4970.1  231.12
  5037.7  231.23  5067.9  230.64    5088  231.43  5178.4  232.06  5208.4  232.09
  5218.5  233.06  5238.5  232.27  5278.5  232.51  5458.6  235.07  5548.6   236.7
  5568.6  237.57  5598.7   237.6  5648.7   239.2  5718.7  240.07  5789.6  242.01
#Mann= 3 , 0 , 0
  4150.3     .05       0  4937.1    .035       0  5178.4     .05       0
#XS Ineff= 2 , 0
       0  4871.7  232.45 5218.87       0  233.03
Permanent Ineff=
       T       T
Bank Sta=4937.1,5178.4
XS Rating Curve= 0 ,0
Exp/Cntr=0.3,0.1

Type RM Length L Ch R = 1 ,7148    ,513,513,513
BEGIN DESCRIPTION:
Mapping XS c7e464df
END DESCRIPTION:
XS GIS Cut Line= 3
      2263902.67     13395447.42      2263329.43     13395319.31
      2262447.52     13395305.42
#Sta/Elev= 30
  4566.7  232.95  4602.5   232.5  4638.2  230.45    4664  230.64  4725.1  229.14
    4817  229.46  4899.7  229.06  4920.2  228.52  5000.9  228.68  5005.8  227.62
  5012.4  228.38  5073.9  228.43  5114.8  229.18  5125.1  229.41  5175.8  229.92
  5305.8  229.48  5555.8  231.05  5575.8   232.1  5585.8  232.23  5605.8   231.5
  5695.9  232.99  5725.9   232.9  5755.9  234.13  5775.9  233.48  5805.9  234.36
  5895.9  234.86  5915.9  235.85  5955.9  235.69  5985.9  236.86  6036.1  237.52
#Mann= 3 ,-1 , 0
  4566.7     .05       0    4817    .035       0  5114.8     .05       0
Bank Sta=4817,5125.1
XS Rating Curve= 0 ,0
Exp/Cntr=0.3,0.1

Type RM Length L Ch R = 1 ,6635    ,665,665,665
BEGIN DESCRIPTION:
Mapping XS e7531443
END DESCRIPTION:
XS GIS Cut Line= 2
      2263947.51     13394909.59      2262531.75     13394861.01
#Sta/Elev= 30
  4492.5  231.27  4542.3  231.26  4632.4  229.71  4652.4  229.86  4682.4  228.84
  4717.7  228.56  4752.4  228.81  4762.5  228.39  4842.5  228.28  4942.6  227.07
  4962.6  227.55  4972.6  226.73  4989.6  226.33  4992.3  225.83  4995.6  226.33
  5002.6   226.5  5132.7  226.79  5192.7  227.57  5222.7  227.79  5417.8   231.7
  5479.7  232.54  5621.9  234.26  5692.3  234.79    5703  234.84    5723  236.17
    5743   235.5  5790.5   236.5  5853.1  237.31  5881.3  238.63  5909.1  238.39
#Mann= 8 ,-1 , 0
  4492.5     .05       0  4962.6    .035       0  5192.7     .05       0
  5417.8      .1       0  5479.7     .05       0  5621.9      .1       0
  5692.3     .05       0  5790.5      .1       0
Bank Sta=4962.6,5192.7
XS Rating Curve= 0 ,0
Exp/Cntr=0.3,0.1

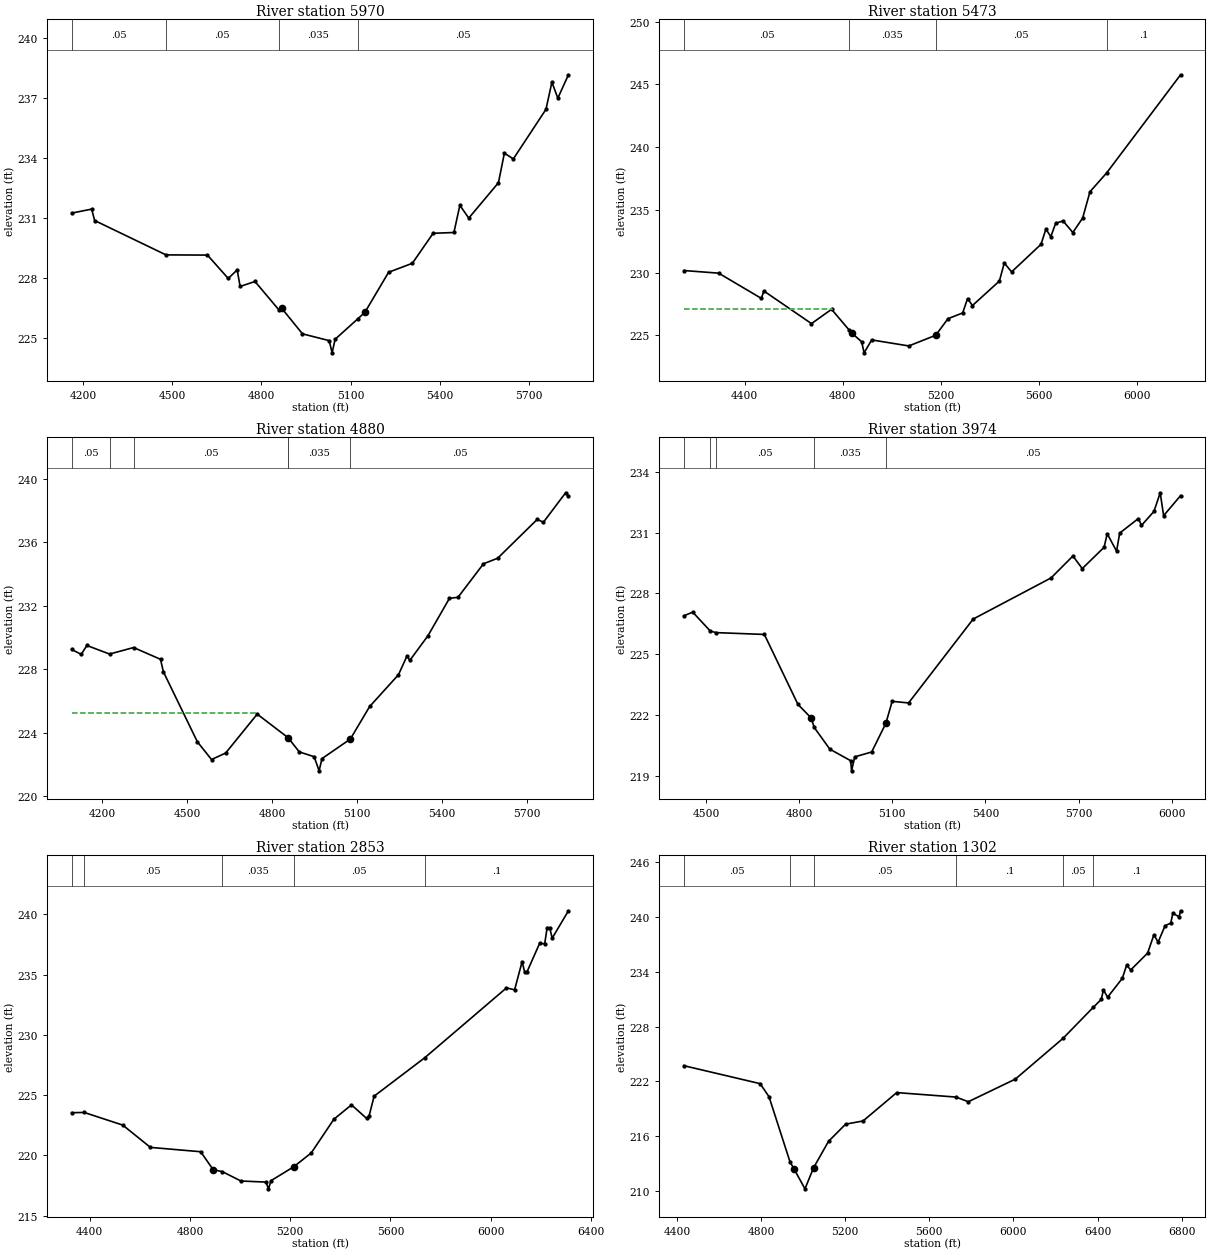
Type RM Length L Ch R = 1 ,5970    ,497,497,497
BEGIN DESCRIPTION:
Mapping XS 9414be02
END DESCRIPTION:
XS GIS Cut Line= 2
      2264134.95      13394333.2      2262462.06     13394284.61
#Sta/Elev= 30
  4160.6  231.23  4227.9  231.43  4237.9  230.86  4478.2  229.14    4618  229.13
  4688.1  227.96  4718.1  228.39  4728.1  227.56  4778.1  227.81  4858.1   226.4
  4868.1  226.47  4938.2  225.19  5028.2  224.85    5038  224.24  5048.2  224.92
  5123.7  225.93  5148.2  226.26  5228.3  228.27  5308.3  228.72  5378.3  230.22
  5448.4  230.26  5468.4  231.62  5498.4  230.98  5598.4  232.75  5618.4  234.23
  5648.5  233.94  5758.5  236.42  5778.5  237.78  5798.5  236.98  5834.2  238.15
#Mann= 4 ,-1 , 0
  4160.6     .05       0  4478.2     .05       0  4858.1    .035       0
  5123.7     .05       0
Bank Sta=4868.1,5148.2
XS Rating Curve= 0 ,0
Exp/Cntr=0.3,0.1

Type RM Length L Ch R = 1 ,5473    ,593,593,593
BEGIN DESCRIPTION:
UNT044 IN SUCR 2.0
END DESCRIPTION:
XS GIS Cut Line= 3
      2264096.64     13393667.09      2263287.72     13393846.85
      2262087.68     13393846.85
#Sta/Elev= 30
    4151  230.17  4293.3  229.96  4467.5  227.95  4477.7  228.54  4672.3  225.94
  4754.3  227.08    4826  225.43  4836.2   225.2  4877.2  224.49  4887.2  223.61
  4918.2  224.64  5069.7  224.16  5179.7  225.01  5229.7  226.33  5289.7  226.79
  5309.7  227.93  5329.7  227.38  5439.7  229.33  5459.7  230.77  5489.7  230.06
  5609.7  232.26  5629.7  233.47  5649.7  232.87  5669.7  233.94  5699.7  234.12
  5739.7   233.2  5779.7  234.35  5809.7  236.45  5877.4  237.94  6179.7  245.77
#Mann= 4 ,-1 , 0
    4151     .05       0    4826    .035       0  5179.7     .05       0
  5877.4      .1       0
#XS Ineff= 2 , 0
       0 4757.34  227.14               0
Permanent Ineff=
       T       F
Bank Sta=4836.2,5179.7
XS Rating Curve= 0 ,0
Exp/Cntr=0.3,0.1

Type RM Length L Ch R = 1 ,4880    ,906,906,906
BEGIN DESCRIPTION:
Mapping XS fbfc7e0d
END DESCRIPTION:
XS GIS Cut Line= 2
      2264201.27     13393289.62      2262447.81     13393376.42
#Sta/Elev= 30
  4091.8  229.25  4125.4  228.94  4145.4   229.5  4225.7  228.96  4310.6  229.37
  4405.7  228.63  4415.7  227.85  4535.9  223.44    4586  222.32    4636  222.73
  4747.5  225.18  4856.3   223.7  4896.3   222.8  4948.7   222.5  4966.2  221.61
  4976.4  222.38  5076.6  223.61    5145  225.66  5246.8  227.66  5276.8  228.84
  5286.8  228.56  5351.2  230.12    5427  232.47    5457  232.53  5547.1  234.64
  5597.2  234.99  5737.4  237.44  5758.7  237.25  5837.5  239.11  5847.4  238.89
#Mann= 6 ,-1 , 0
  4091.8     .05       0  4225.7      .1       0  4310.6     .05       0
  4856.3      .1       0  4856.3    .035       0  5076.6     .05       0
#XS Ineff= 2 , 0
       0 4748.43  225.26               0
Permanent Ineff=
       T       F
Bank Sta=4856.3,5076.6
XS Rating Curve= 0 ,0
Exp/Cntr=0.3,0.1

Type RM Length L Ch R = 1 ,3974    ,1121,1121,1121
BEGIN DESCRIPTION:
Mapping XS 58e745a1
END DESCRIPTION:
XS GIS Cut Line= 3
      2264032.81     13392844.28      2263967.32     13392634.71
      2262592.33     13392516.85
#Sta/Elev= 30
    4429  226.89  4457.7  227.07    4514  226.14  4532.9  226.06  4688.3  225.97
  4796.4  222.52  4838.9  221.85  4848.9  221.38  4899.1  220.31  4966.3  219.74
  4969.1  219.24  4979.4  219.93  5033.9  220.17  5079.7  221.59  5099.8  222.67
  5152.7  222.59  5360.8  226.73  5611.7  228.76  5681.9  229.84    5712  229.22
  5782.3  230.27  5792.3  230.94  5822.5  230.08  5832.5  230.97  5892.7  231.69
  5902.7  231.35  5942.9  232.04    5963  232.96    5974  231.83  6028.6  232.82
#Mann= 5 ,-1 , 0
    4429     .05       0    4514      .1       0  4532.9     .05       0
  4848.9    .035       0  5079.7     .05       0
Bank Sta=4838.9,5079.7
XS Rating Curve= 0 ,0
Exp/Cntr=0.3,0.1

Type RM Length L Ch R = 1 ,2853    ,1551,1551,1551
BEGIN DESCRIPTION:
Mapping XS a6fd9988
END DESCRIPTION:
XS GIS Cut Line= 3
      2264320.98     13391626.07      2263076.57     13391534.38
      2262343.02     13391560.58
#Sta/Elev= 30
  4328.4  223.54  4378.4  223.56  4532.2  222.51  4642.5  220.66    4843   220.3
  4893.2   218.8  4929.2  218.65  5003.5  217.87  5103.8  217.78  5113.5  217.22
  5123.8   217.9  5214.1  219.05  5284.2   220.2  5374.5     223  5444.7  224.19
  5504.8  223.07  5514.9  223.27  5534.9  224.91  5737.5  228.11  6063.1   233.9
  6095.4  233.74  6125.4  236.08  6135.4  235.22  6145.4  235.25  6195.4   237.6
  6215.4  237.56  6225.4  238.91  6235.4  238.89  6245.5  238.03  6310.2   240.3
#Mann= 5 ,-1 , 0
  4328.4      .1       0  4378.4     .05       0  4929.2    .035       0
  5214.1     .05       0  5737.5      .1       0
Bank Sta=4893.2,5214.1
XS Rating Curve= 0 ,0
Exp/Cntr=0.3,0.1

Type RM Length L Ch R = 1 ,1302    ,956,956,956
BEGIN DESCRIPTION:
Mapping XS 8aa2e925
END DESCRIPTION:
XS GIS Cut Line= 4
       2264609.2     13390944.95      2264438.89     13390735.33
      2262997.98     13390473.34      2262370.93     13390460.28
#Sta/Elev= 30
  4432.7  223.71  4795.4  221.74  4837.6  220.31  4937.7  213.15  4958.1  212.33
  5008.6  210.21  5049.5  212.52  5120.7  215.42    5202   217.3  5284.8  217.65
  5444.9  220.76  5726.3  220.27  5785.4  219.76    6009  222.24  6235.8  226.71
  6378.7  230.09  6417.6  230.98  6427.6  232.01  6447.6  231.22  6517.7  233.29
  6537.7  234.71  6557.7  234.21  6637.7  236.05  6667.7  238.06  6687.7  237.25
  6720.8  239.06  6747.7  239.33  6757.7  240.41  6787.7  240.03  6794.5  240.69
#Mann= 6 ,-1 , 0
  4432.7     .05       0  4937.7    .035       0  5049.5     .05       0
  5726.3      .1       0  6235.8     .05       0  6378.7      .1       0
Bank Sta=4958.1,5049.5
XS Rating Curve= 0 ,0
Exp/Cntr=0.3,0.1

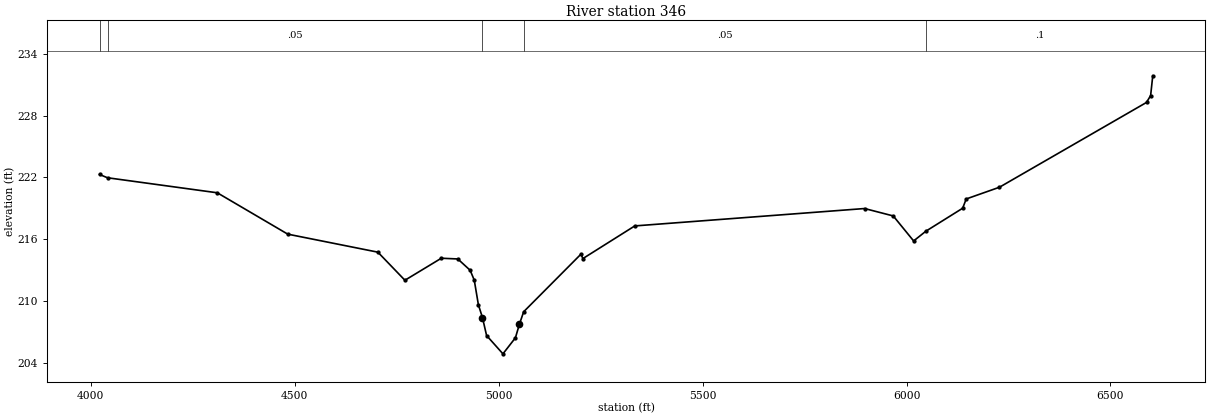
Type RM Length L Ch R = 1 ,346     ,0,0,0
BEGIN DESCRIPTION:
UNT044 IN SUCR 1.0
END DESCRIPTION:
XS GIS Cut Line= 4
       2264615.7     13390596.33      2264685.15     13389849.82
      2263782.37     13389728.29      2262862.49     13389676.22
#Sta/Elev= 30
  4021.6  222.29  4041.2  221.97  4310.3  220.51  4483.1  216.49    4704  214.74
  4770.3  212.01  4859.5  214.15  4899.9  214.08  4930.2  212.98  4940.3  212.02
  4950.4  209.63  4960.4  208.38  4970.5  206.64  5010.6  204.86  5041.2  206.42
    5051  207.74  5061.4  208.95  5201.7  214.54  5206.7  214.12  5333.8  217.29
  5897.2  218.98  5967.4  218.26  6017.4  215.83  6047.5  216.78  6137.6  219.01
  6146.3  219.91  6227.8  221.05  6588.3  229.29  6598.4  229.96  6603.6  231.88
#Mann= 5 ,-1 , 0
  4021.6     .05       0  4041.2     .05       0  4960.4    .035       0
  5061.4     .05       0  6047.5      .1       0
Bank Sta=4960.4,5051
XS Rating Curve= 0 ,0
Exp/Cntr=0.3,0.1

Chan Stop Cuts=-1
Use User Specified Reach Order=0
Composite Channel Slope=5