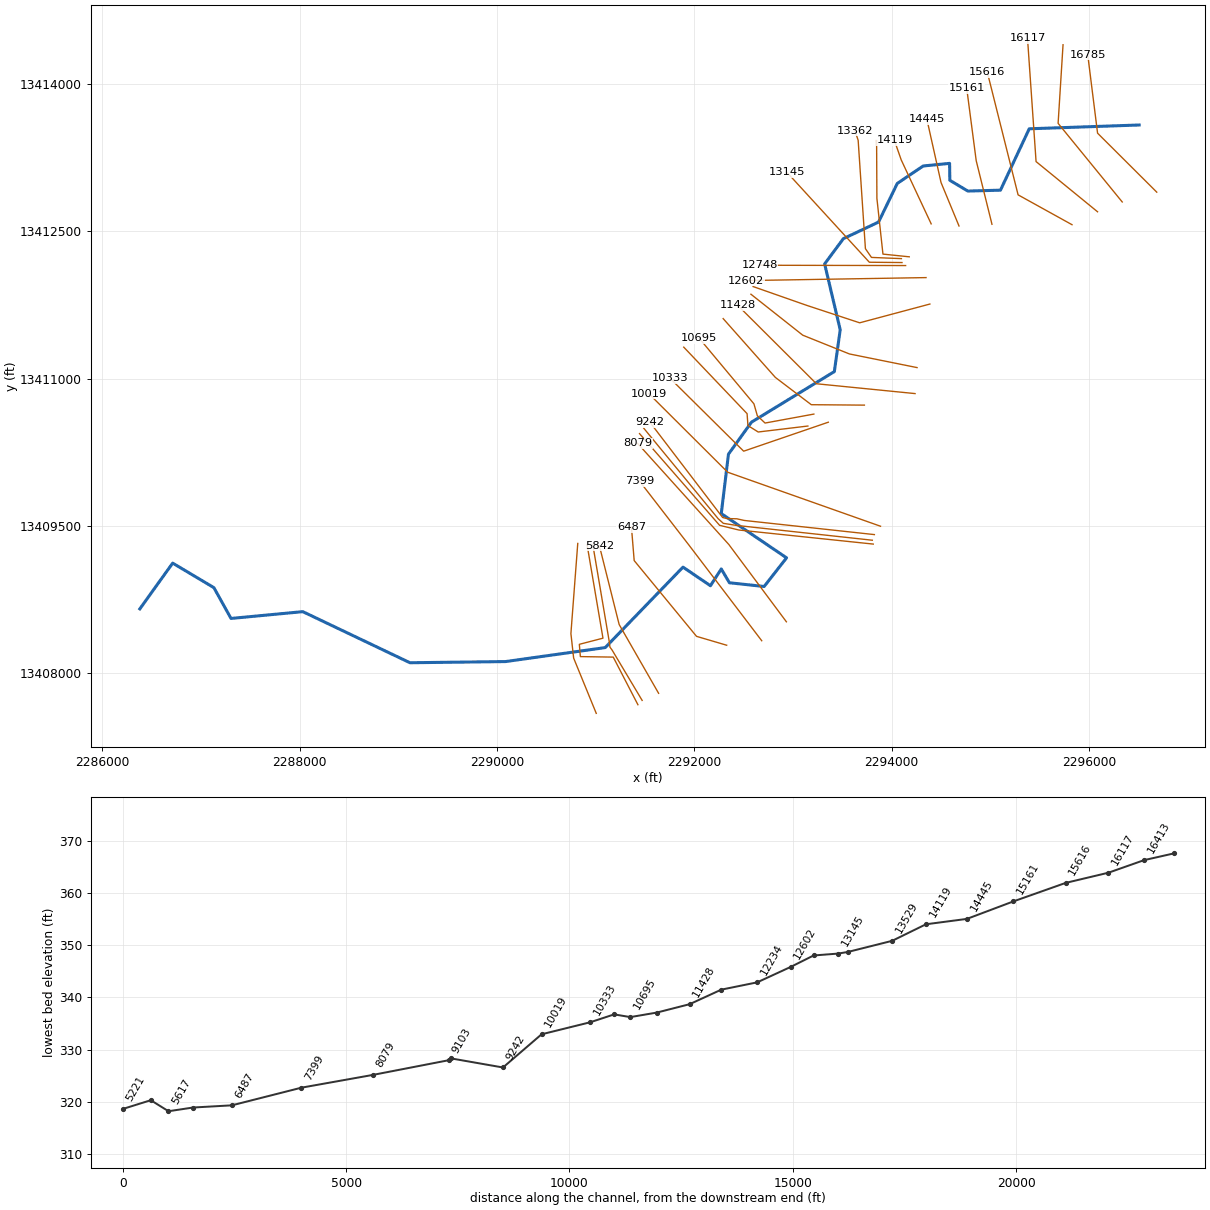
--- UNT046 IN SUCR.prj (project) ---

Proj Title=UNT046 IN SUCR Base Level Engineering
Current Plan=p01
Default Exp/Contr=0.3,0.1
English Units
Geom File=g01
Flow File=f01
Plan File=p01
Y Axis Title=Elevation
X Axis Title(PF)=Main Channel Distance
X Axis Title(XS)=Station
BEGIN DESCRIPTION:
UNT046 IN SUCR
END DESCRIPTION:
DSS Export Rating Curves= 0
DSS Export Rating Curve Sorted= 0
DSS Export Volume Flow Curves= 0
DXF OffsetX= 0
DXF OffsetY= 0
DXF ScaleX= 1
DXF ScaleY= 10

--- UNT046 IN SUCR.p01 (plan) ---

Plan Title=Multiple Run
Short Identifier=Multiple
Geom File=g01
Flow File=f01
Subcritical Flow
K Sum by GR= 0
Std Step Tol= 0.01
Critical Tol= 0.01
Num of Std Step Trials= 20
Max Error Tol= 0.3
Flow Tol Ratio= 0.001
Split Flow NTrial= 30
Split Flow Tol= 0.02
Split Flow Ratio= 0.02
Log Output Level= 0
Friction Slope Method= 1
Unsteady Friction Slope Method= 2
Unsteady Bridges Friction Slope Method= 1
Parabolic Critical Depth
Global Vel Dist=  1 , 1 , 1
Global Log Level= 0
CheckData=True
Encroach Param= -1, 0, 0, 0
BEGIN DESCRIPTION:
Multiple Run
END DESCRIPTION:

--- UNT046 IN SUCR.f01 (steady flow) ---

Flow Title=Multiple
Program Version=4.10
Number of Profiles= 7
Profile Names=10-year,25-year,50-year,1pct_min,100-year,1pct_plu,500-year
River Rch & RM=UNT046 IN SUCR,Reach-1         ,16785
     638     908    1137    1040    1406    1901    2159
River Rch & RM=UNT046 IN SUCR,Reach-1         ,16413
     762    1094    1376    1265    1710    2313    2650
River Rch & RM=UNT046 IN SUCR,Reach-1         ,13362
     820    1181    1489   13670    1853    2507    2884
River Rch & RM=UNT046 IN SUCR,Reach-1         ,12602
     886    1279    1616    1489    2014    2724    3143
River Rch & RM=UNT046 IN SUCR,Reach-1         ,10019
    1416    2090    2679    2501    3382    4574    5419
River Rch & RM=UNT046 IN SUCR,Reach-1         ,2712
    1431    2114    2711    2533    3425    4632    5499
Boundary for River Rch & Prof#=UNT046 IN SUCR,Reach-1         , 1
Up Type= 0
Dn Type= 3
Dn Slope=0.0491
Boundary for River Rch & Prof#=UNT046 IN SUCR,Reach-1         , 2
Up Type= 0
Dn Type= 3
Dn Slope=0.0491
Boundary for River Rch & Prof#=UNT046 IN SUCR,Reach-1         , 3
Up Type= 0
Dn Type= 3
Dn Slope=0.0491
Boundary for River Rch & Prof#=UNT046 IN SUCR,Reach-1         , 4
Up Type= 0
Dn Type= 3
Dn Slope=0.0491
Boundary for River Rch & Prof#=UNT046 IN SUCR,Reach-1         , 5
Up Type= 0
Dn Type= 3
Dn Slope=0.0491
Boundary for River Rch & Prof#=UNT046 IN SUCR,Reach-1         , 6
Up Type= 0
Dn Type= 3
Dn Slope=0.0491
Boundary for River Rch & Prof#=UNT046 IN SUCR,Reach-1         , 7
Up Type= 0
Dn Type= 3
Dn Slope=0.0491
DSS Import GetInterval= 0
DSS Import GetPeak= 0
DSS Import FillOption= 0

--- UNT046 IN SUCR.g01 (geometry) ---

Geom Title=Existing Conditions
Program Version=4.10

River Reach=UNT046 IN SUCR  ,Reach-1
Reach XY= 30
      2296509.03     13413580.09      2295395.04     13413541.45
      2295103.32     13412916.79      2294772.48     13412907.83
      2294589.93      13413017.5      2294587.66     13413189.62
      2294319.41     13413162.85      2294057.32     13412985.36
      2293867.17     13412592.05      2293510.76     13412423.64
      2293320.87     13412166.48      2293478.75     13411496.31
      2293419.08     13411070.62      2292579.14     13410555.98
      2292345.85     13410230.46      2292272.97     13409625.77
      2292934.76     13409175.42      2292707.53     13408883.77
      2292355.28     13408921.83      2292273.07     13409062.51
      2292163.32     13408891.54      2291884.85      13409080.8
      2291096.29     13408262.02      2290085.52      13408119.8
      2289117.08     13408107.86      2288030.59     13408627.81
      2287302.76     13408558.62      2287129.15     13408872.21
      2286711.39     13409121.77      2286378.43     13408655.82

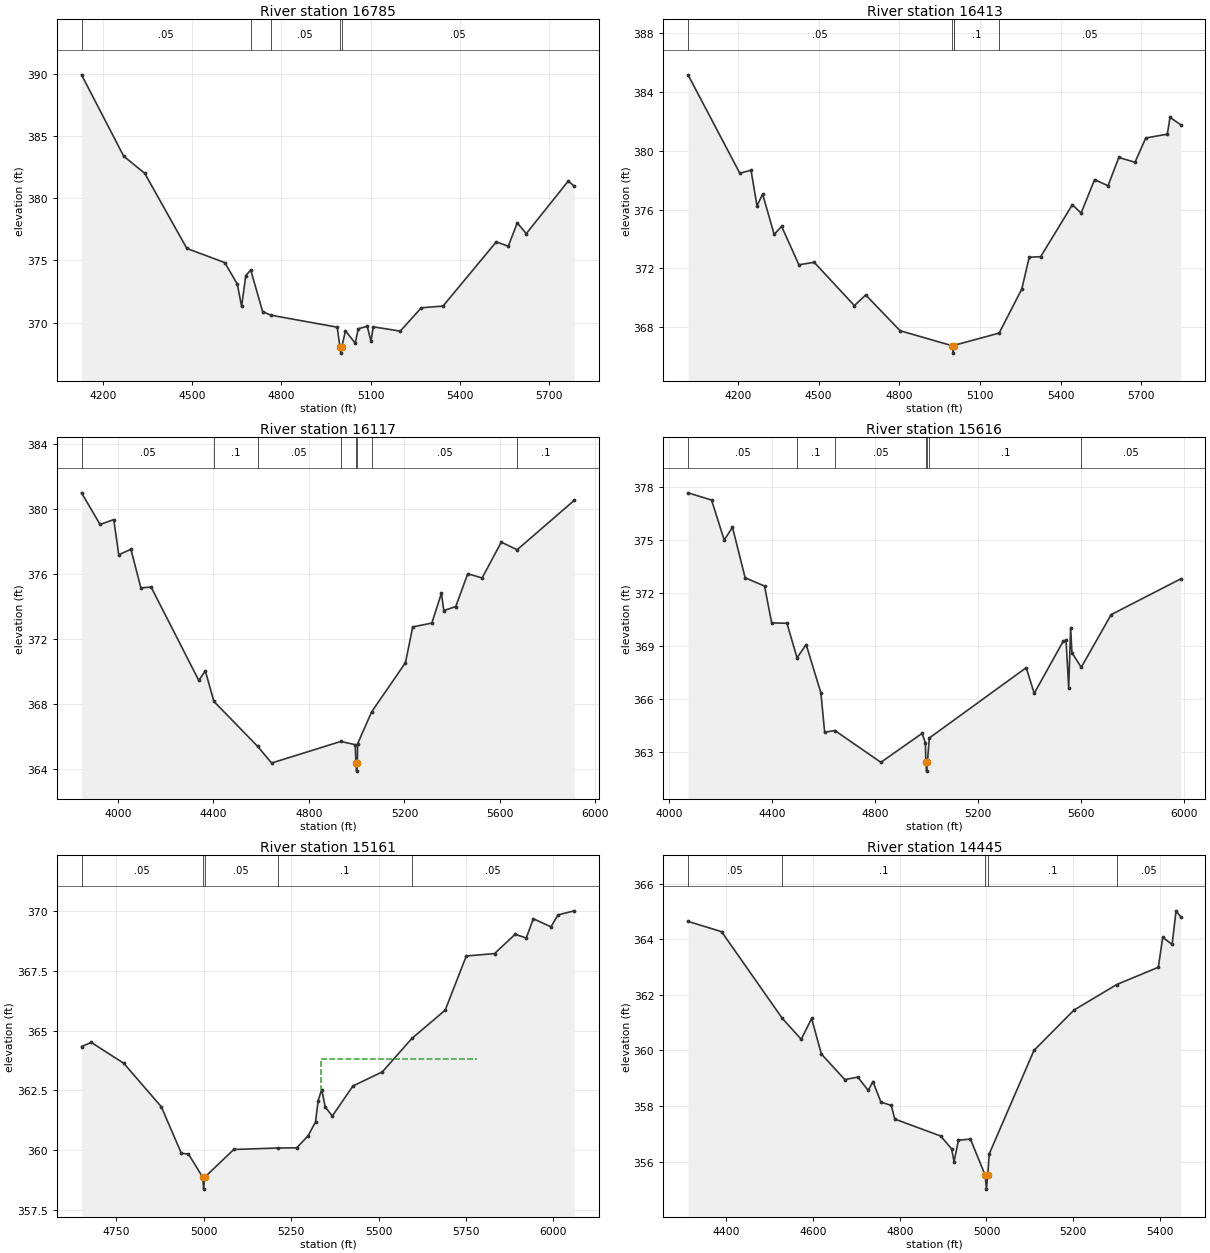
Type RM Length L Ch R = 1 ,16785   ,668,668,668
BEGIN DESCRIPTION:
UNT046 IN SUCR 26.0
END DESCRIPTION:
XS GIS Cut Line= 3
      2296687.74     13412896.83      2296087.72     13413496.85
      2295987.72     13414296.87
#Sta/Elev= 30
  4129.2  389.95  4270.7   383.4  4341.4  382.02  4482.8  375.97  4610.1  374.83
  4652.5  373.09  4666.6   371.3  4680.8  373.79  4697.4  374.23  4737.3  370.89
    4764   370.6  4987.8  369.63    4997  368.04  4999.8  367.54    5003  368.04
  5015.6  369.34  5048.3  368.34  5058.4   369.5  5088.6   369.7  5101.2  368.51
  5108.8  369.66  5199.5  369.31    5270  371.19  5343.1  371.33    5522   376.5
  5562.3  376.15  5592.5  378.03  5622.7  377.16  5763.8   381.4    5784  380.98
#Mann= 5 ,-1 , 0
  4129.2     .05       0  4697.4      .1       0    4764     .05       0
    4997     .03       0    5003     .05       0
Bank Sta=4997,5003
XS Rating Curve= 0 ,0
Exp/Cntr=0.3,0.1

Type RM Length L Ch R = 1 ,16413   ,796,796,796
BEGIN DESCRIPTION:
UNT046 IN SUCR 25.0
END DESCRIPTION:
XS GIS Cut Line= 3
      2296337.72     13412796.85      2295687.72     13413596.85
      2295737.72     13414396.81
#Sta/Elev= 30
  4014.3  385.15  4206.8  378.47  4248.5  378.67  4270.8  376.25  4291.6  377.05
  4334.7  374.31  4362.2  374.86  4426.6  372.25  4483.4  372.42  4632.8  369.48
  4675.1   370.2    4803  367.77    4997  366.75  4999.8  366.25    5003  366.75
  5003.6  366.78  5171.2  367.61  5255.5  370.61    5283  372.76  5325.6   372.8
  5443.4  376.33  5475.9  375.76    5526  378.03  5576.1  377.62  5616.2  379.54
  5676.3  379.21  5716.4  380.86  5796.5  381.12  5806.6  382.26  5846.6  381.76
#Mann= 5 ,-1 , 0
  4014.3     .05       0    4997     .03       0    5003     .05       0
  5003.6      .1       0  5171.2     .05       0
Bank Sta=4997,5003
XS Rating Curve= 0 ,0
Exp/Cntr=0.3,0.1

Type RM Length L Ch R = 1 ,16117   ,957,957,957
BEGIN DESCRIPTION:
UNT046 IN SUCR 24.0
END DESCRIPTION:
XS GIS Cut Line= 3
      2296087.69     13412696.88      2295464.29     13413207.73
      2295377.49     13414461.96
#Sta/Elev= 30
  3848.2  381.01  3925.7  379.06  3983.1  379.36  4003.9  377.19  4054.9  377.53
  4096.5  375.15  4139.5   375.2  4339.1  369.44  4366.3  370.04  4402.3  368.15
    4586  365.37  4644.1  364.35  4933.6  365.68  4994.1  365.48    4997  364.35
  4999.8  363.85    5003  364.35  5004.1  365.54  5063.1  367.51  5204.6  370.54
  5234.7  372.74  5314.9  372.98    5355  374.82    5365  373.75  5415.1     374
  5465.2  376.02  5525.4  375.76  5605.6  377.97    5672   377.5  5911.4  380.55
#Mann= 8 ,-1 , 0
  3848.2     .05       0  4402.3      .1       0    4586     .05       0
  4933.6      .1       0    4997     .07       0    5003      .1       0
  5063.1     .05       0    5672      .1       0
Bank Sta=4997,5003
XS Rating Curve= 0 ,0
Exp/Cntr=0.3,0.1

Type RM Length L Ch R = 1 ,15616   ,1171,1171,1171
BEGIN DESCRIPTION:
UNT046 IN SUCR 23.0
END DESCRIPTION:
XS GIS Cut Line= 3
      2295828.87     13412565.38        2295282.     13412869.19
      2294969.49     13414119.22
#Sta/Elev= 30
  4073.2  377.69  4164.6  377.28  4213.8  375.01  4245.8  375.74    4295  372.87
  4370.5   372.4    4398  370.31  4457.5  370.29  4496.6  368.33  4532.1  369.08
  4589.3  366.34  4603.9  364.11  4643.9   364.2  4822.4   362.4  4982.2  364.04
  4995.3  363.51    4997   362.4  4999.8   361.9    5003   362.4  5010.4  363.78
    5387  367.77  5417.9  366.31  5531.3  369.29  5541.6  369.33  5551.9  366.63
  5559.4  370.03  5564.5  368.62  5600.7  367.79  5716.9  370.78  5987.3  372.81
#Mann= 7 ,-1 , 0
  4073.2     .05       0  4496.6      .1       0  4643.9     .05       0
    4997    .035       0    5003     .05       0  5010.4      .1       0
  5600.7     .05       0
Bank Sta=4997,5003
XS Rating Curve= 0 ,0
Exp/Cntr=0.3,0.1

Type RM Length L Ch R = 1 ,15161   ,1041,1041,1041
BEGIN DESCRIPTION:
Mapping XS 8c5fb43d
END DESCRIPTION:
XS GIS Cut Line= 3
      2295017.23     13412569.75       2294857.4     13413216.77
      2294761.32     13413953.06
#Sta/Elev= 30
  4650.7  364.33  4678.6   364.5  4771.3  363.63  4878.7  361.81  4936.1  359.86
  4956.5  359.83    4997  358.86  4999.8  358.36    5003  358.86    5086  360.02
    5212  360.08  5265.8  360.09  5298.4  360.59  5319.7  361.17  5327.3  362.07
  5337.4  362.53  5347.5   361.8  5367.7  361.42  5426.9  362.68  5510.9  363.27
  5595.4  364.67  5690.4  365.85  5750.9  368.12  5831.6  368.22  5890.7  369.03
  5922.3  368.87  5942.5  369.68  5992.9  369.34  6013.1  369.84  6059.7  370.01
#Mann= 5 ,-1 , 0
  4650.7     .05       0    4997     .03       0    5003     .05       0
    5212      .1       0  5595.4     .05       0
#XS Ineff= 1 ,-1
 5336.17 5782.48  363.81
Permanent Ineff=
       T
Bank Sta=4997,5003
XS Rating Curve= 0 ,0
Exp/Cntr=0.3,0.1

Type RM Length L Ch R = 1 ,14445   ,917,917,917
BEGIN DESCRIPTION:
Mapping XS febc91cc
END DESCRIPTION:
XS GIS Cut Line= 3
      2294683.03     13412552.39      2294500.75     13412995.06
      2294357.51     13413637.45
#Sta/Elev= 30
  4311.4  364.64  4388.8  364.27    4529  361.15  4572.6   360.4  4596.6  361.15
    4619  359.87  4673.1  358.95  4703.2  359.04  4727.1  358.56    4738  358.88
  4756.5  358.14  4780.4  358.02  4788.4  357.53  4894.4  356.92  4919.5  356.46
  4925.2     356  4935.4  356.77    4963  356.81    4997  355.51  4999.8  355.01
    5003  355.51  5006.4  356.28  5109.6     360  5201.8  361.45  5300.7  362.37
  5396.5  362.99  5406.7  364.07  5428.3  363.81  5437.4  365.02  5448.3   364.8
#Mann= 5 ,-1 , 0
  4311.4     .05       0    4529      .1       0    4997     .07       0
    5003      .1       0  5300.7     .05       0
Bank Sta=4997,5003
XS Rating Curve= 0 ,0
Exp/Cntr=0.3,0.1

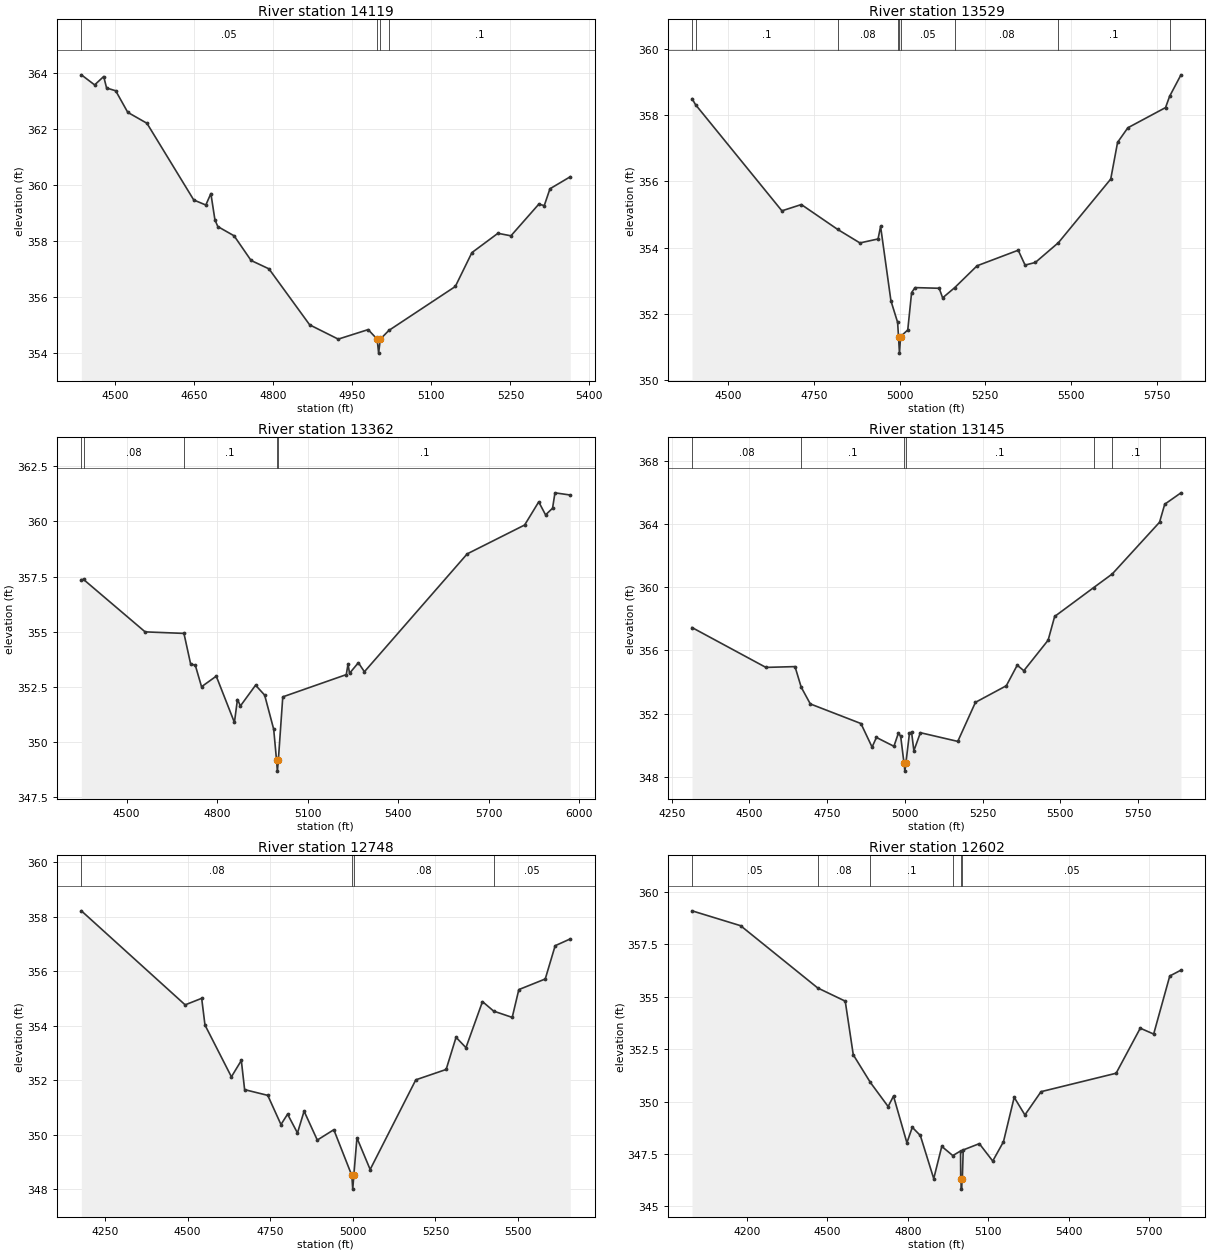
Type RM Length L Ch R = 1 ,14119   ,757,757,757
BEGIN DESCRIPTION:
Mapping XS fc454340
END DESCRIPTION:
XS GIS Cut Line= 3
      2294400.93     13412574.05      2294097.11      13413225.1
      2294028.16      13413423.3
#Sta/Elev= 30
  4435.4  363.92  4460.6  363.56  4477.8  363.86  4483.3  363.45  4500.6  363.35
  4523.5  362.58  4559.9  362.19  4648.8  359.45  4671.7  359.27  4681.3  359.68
    4689  358.74  4694.5   358.5  4725.4  358.17  4757.6  357.29  4791.6  356.99
  4868.9  354.99  4923.1  354.48  4979.9  354.82    4997  354.48  4999.8  353.98
    5003  354.48  5019.2  354.79  5145.4  356.36  5176.9  357.57  5226.3  358.26
    5251  358.17  5303.9   359.3  5314.3  359.25  5325.1  359.85  5363.7  360.28
#Mann= 4 ,-1 , 0
  4435.4     .05       0    4997    .035       0    5003     .05       0
  5019.2      .1       0
Bank Sta=4997,5003
XS Rating Curve= 0 ,0
Exp/Cntr=0.3,0.1

Type RM Length L Ch R = 1 ,13529   ,998,998,998
BEGIN DESCRIPTION:
Mapping XS f4c3370a
END DESCRIPTION:
XS GIS Cut Line= 4
      2294178.64     13412238.66      2293911.99     13412266.24
      2293850.68     13412833.35      2293847.62     13413421.85
#Sta/Elev= 30
  4394.4   358.5  4404.5  358.32  4656.7  355.11  4713.4   355.3  4819.2  354.55
  4884.4  354.14  4937.3  354.26  4944.7  354.64  4974.9  352.39  4994.4  351.74
    4997  351.31  4999.8  350.81    5003  351.31    5024  351.51  5035.2  352.64
  5045.3  352.79  5115.7  352.77  5125.8  352.48  5161.1  352.79  5226.4  353.45
  5346.4  353.92  5366.4  353.47  5396.4  353.55  5463.9  354.15  5616.4  356.07
  5636.4  357.18  5666.4  357.62  5776.4  358.23  5788.2  358.57  5821.4  359.22
#Mann= 9 ,-1 , 0
  4394.4     .05       0  4404.5      .1       0  4819.2     .08       0
  4994.4     .05       0    4997    .035       0    5003     .05       0
  5161.1     .08       0  5463.9      .1       0  5788.2     .05       0
Bank Sta=4997,5003
XS Rating Curve= 0 ,0
Exp/Cntr=0.3,0.1

Type RM Length L Ch R = 1 ,13362   ,217,217,217
BEGIN DESCRIPTION:
UNT046 IN SUCR 22.0
END DESCRIPTION:
XS GIS Cut Line= 5
      2294098.98     13412220.26       2293795.5     13412232.52
      2293734.19     13412321.42      2293660.62     13413424.99
      2293627.12     13413522.46
#Sta/Elev= 30
    4350  357.36  4357.1  357.37  4561.4  354.99  4690.1  354.92  4712.6  353.51
  4727.4  353.49  4748.4   352.5  4797.2  352.98  4857.4  350.88  4867.4  351.92
  4877.4  351.63  4927.5  352.57  4957.6  352.12  4987.6  350.57    4997  349.17
  4999.8  348.67    5003  349.17  5017.7  352.04  5228.2  353.05    5234  353.53
    5239  353.11  5268.3  353.59  5288.3  353.18  5629.1  358.53  5819.5  359.84
  5866.2  360.89  5888.8   360.3    5912   360.6    5920   361.3  5970.8   361.2
#Mann= 5 ,-1 , 0
    4350      .1       0  4357.1     .08       0  4690.1      .1       0
    4997     .07       0    5003      .1       0
Bank Sta=4997,5003
XS Rating Curve= 0 ,0
Exp/Cntr=0.3,0.1

Type RM Length L Ch R = 1 ,13145   ,543,543,543
BEGIN DESCRIPTION:
Mapping XS 7772beae
END DESCRIPTION:
XS GIS Cut Line= 3
      2294105.09     13412180.41      2293774.04     13412183.47
      2292937.18     13413100.04
#Sta/Elev= 30
  4315.4  357.45  4552.8  354.93  4646.5  354.98  4666.4  353.68  4695.7  352.62
  4858.5  351.38  4894.3  349.89  4908.3   350.5  4964.6  349.94  4978.7  350.76
  4986.2  350.59    4997  348.87  4999.8  348.37    5003  348.87  5014.5  350.76
  5021.3  350.84  5028.7  349.66  5049.7   350.8  5169.9  350.25  5226.7  352.72
    5326  353.77  5361.1  355.07  5382.3  354.72  5460.4  356.65  5481.4  358.15
  5606.4  359.97  5666.7  360.84  5818.7  364.11  5835.4  365.25  5887.6  365.97
#Mann= 7 ,-1 , 0
  4315.4     .08       0  4666.4      .1       0    4997     .07       0
    5003      .1       0  5606.4     .05       0  5666.7      .1       0
  5818.7     .05       0
Bank Sta=4997,5003
XS Rating Curve= 0 ,0
Exp/Cntr=0.3,0.1

Type RM Length L Ch R = 1 ,12748   ,513,513,513
BEGIN DESCRIPTION:
Mapping XS 9fbe881f
END DESCRIPTION:
XS GIS Cut Line= 2
      2294141.95     13412149.75      2292661.95     13412152.82
#Sta/Elev= 30
  4178.3  358.22  4492.5  354.77  4542.5  355.01  4552.5  354.03  4632.5  352.13
  4662.5  352.73  4672.5  351.66  4742.5  351.45  4782.5  350.38  4802.5  350.76
  4832.5  350.07  4852.5  350.87  4892.5  349.81  4942.5  350.19    4997  348.51
  4999.8  348.01    5003  348.51  5012.5  349.89  5052.5  348.73  5190.7  352.02
  5282.5   352.4  5312.5  353.58  5342.5   353.2  5392.5  354.89  5426.5  354.54
  5482.5  354.31  5502.5  355.33  5582.5  355.72  5612.5  356.94  5658.3  357.19
#Mann= 4 ,-1 , 0
  4178.3     .08       0    4997     .07       0    5003     .08       0
  5426.5     .05       0
Bank Sta=4997,5003
XS Rating Curve= 0 ,0
Exp/Cntr=0.3,0.1

Type RM Length L Ch R = 1 ,12602   ,749,749,749
BEGIN DESCRIPTION:
UNT046 IN SUCR 21.0
END DESCRIPTION:
XS GIS Cut Line= 2
      2294348.79     13412027.18      2292525.95      13411996.8
#Sta/Elev= 30
  3995.2   359.1  4176.3  358.39  4463.8  355.42  4566.4  354.79  4596.4  352.23
  4660.2  350.91  4726.4  349.76  4746.4  350.26  4796.4  348.03  4816.4  348.77
  4846.4  348.38  4896.4  346.32  4926.4  347.86  4967.5  347.42  4996.4  347.64
    4997  346.32  4999.8  345.82    5003  346.32  5006.4  347.69  5066.4  347.99
  5116.4  347.16  5156.4  348.08  5196.4   350.2  5236.4  349.36  5296.5  350.47
  5576.5  351.35  5666.5   353.5  5716.5  353.22  5776.5  355.99  5818.3  356.27
#Mann= 6 ,-1 , 0
  3995.2     .05       0  4463.8     .08       0  4660.2      .1       0
  4967.5     .05       0    4997     .03       0    5003     .05       0
Bank Sta=4997,5003
XS Rating Curve= 0 ,0
Exp/Cntr=0.3,0.1

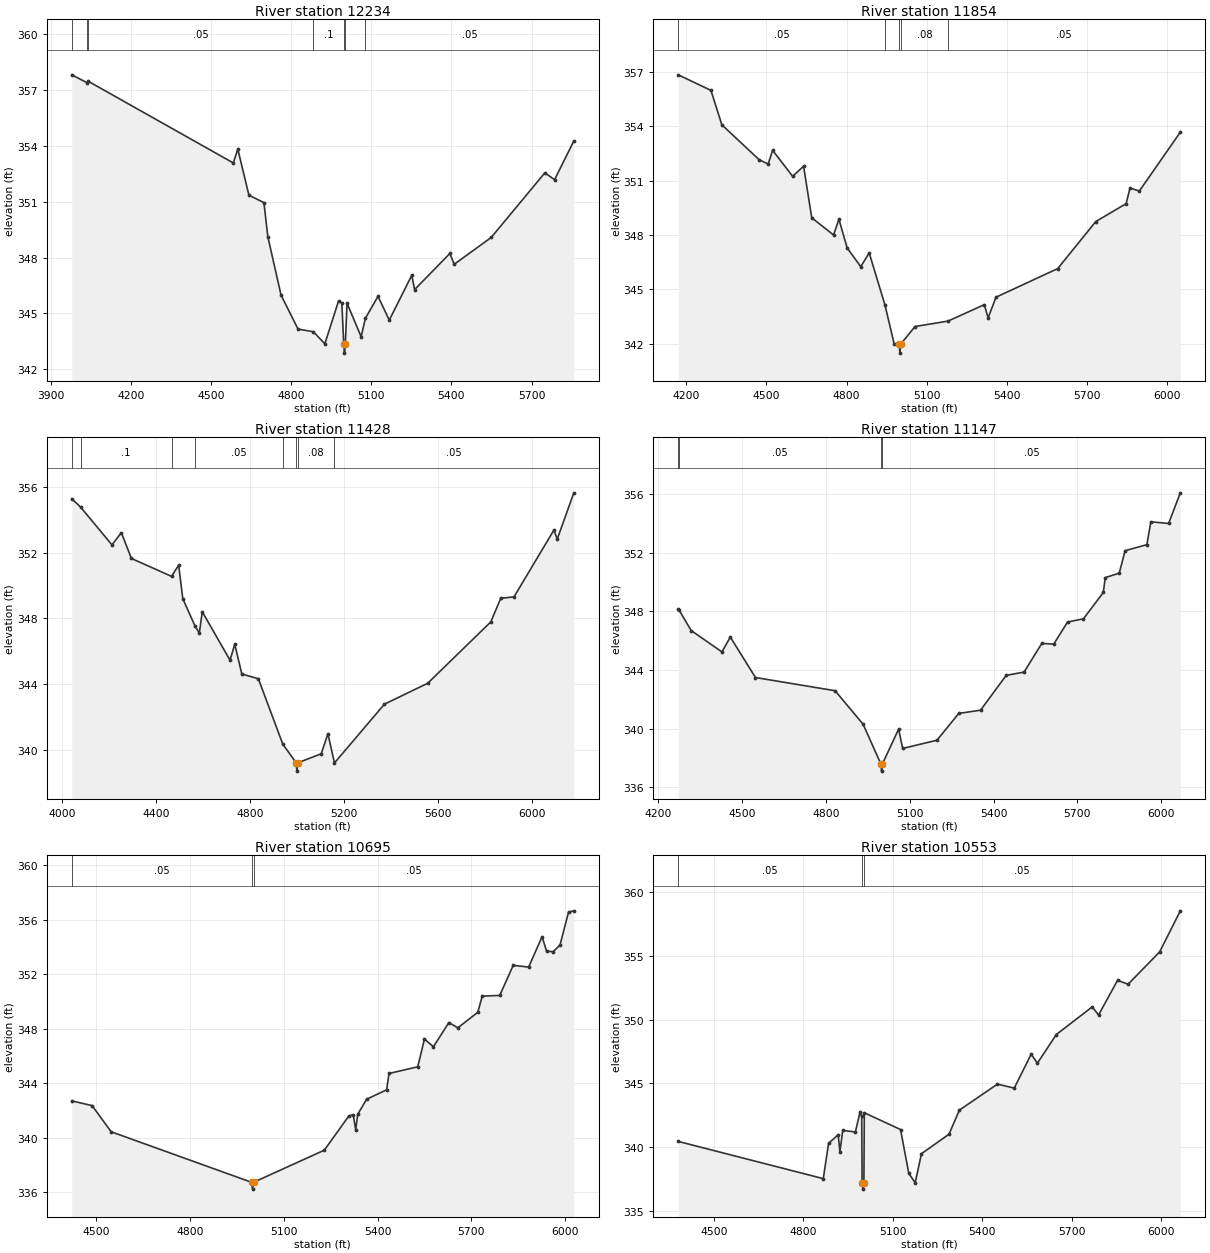
Type RM Length L Ch R = 1 ,12234   ,805,805,805
BEGIN DESCRIPTION:
Mapping XS 52f89e23
END DESCRIPTION:
XS GIS Cut Line= 4
      2294387.93     13411758.09       2293676.1     13411567.11
       2293137.9     13411745.06      2292595.39     13411936.03
#Sta/Elev= 30
  3979.2  357.81    4036  357.39  4041.5  357.46  4583.6  353.08  4600.6  353.82
  4642.1  351.35  4698.4  350.95  4712.8  349.13  4762.5  345.98    4826  344.16
    4883  344.02  4926.4  343.37  4977.8  345.68  4989.9  345.56    4997  343.37
  4999.8  342.87    5003  343.37  5009.4  345.55  5062.1  343.75  5078.1  344.74
  5125.3  345.92  5167.4  344.64  5251.7  347.05  5262.2  346.28  5394.2  348.22
  5410.5  347.64    5549  349.08  5749.7  352.55  5786.1  352.18  5858.2  354.26
#Mann= 7 ,-1 , 0
  3979.2     .05       0    4036      .1       0  4041.5     .05       0
    4883      .1       0    4997     .07       0    5003      .1       0
  5078.1     .05       0
Bank Sta=4997,5003
XS Rating Curve= 0 ,0
Exp/Cntr=0.3,0.1

Type RM Length L Ch R = 1 ,11854   ,708,708,708
BEGIN DESCRIPTION:
UNT046 IN SUCR 20.0
END DESCRIPTION:
XS GIS Cut Line= 4
      2294257.74     13411111.37      2293571.93     13411250.27
      2293098.84     13411441.24      2292573.66     13411857.91
#Sta/Elev= 30
  4169.6  356.85  4292.1  355.99  4332.9  354.09  4472.5  352.16  4506.3  351.92
  4523.1  352.68  4598.1  351.24    4639   351.8  4669.6  348.95  4751.2     348
  4771.5  348.87  4802.2  347.28  4853.2  346.25  4884.7  347.01  4943.8  344.13
  4978.4  341.97    4997  341.97  4999.8  341.47    5003  341.97  5056.2  342.94
    5180  343.24    5316  344.15    5330  343.41  5359.5  344.56  5590.6  346.14
  5733.2  348.74    5847  349.73  5861.4  350.59  5896.6  350.43  6049.9  353.68
#Mann= 5 ,-1 , 0
  4169.6     .05       0  4943.8     .08       0    4997     .07       0
    5003     .08       0    5180     .05       0
Bank Sta=4997,5003
XS Rating Curve= 0 ,0
Exp/Cntr=0.3,0.1

Type RM Length L Ch R = 1 ,11428   ,733,733,733
BEGIN DESCRIPTION:
UNT046 IN SUCR 19.0
END DESCRIPTION:
XS GIS Cut Line= 3
      2294237.74     13410846.85      2293237.72     13410946.85
      2292437.71     13411746.87
#Sta/Elev= 30
  4041.9  355.29  4079.5  354.78  4212.8  352.48    4253  353.22  4295.7  351.65
  4466.4  350.56  4496.7  351.24  4514.3   349.2  4565.4  347.56  4584.6   347.1
  4597.2   348.4  4715.3  345.45  4735.4  346.42  4765.5  344.61  4835.9  344.32
  4939.7  340.34    4997  339.19  4999.8  338.69    5003  339.19  5103.5  339.75
  5131.8  340.97  5159.8  339.19  5372.2  342.77    5556  344.04  5824.7  347.78
  5867.2  349.22  5923.7  349.31  6093.4  353.38  6107.6  352.83  6178.3  355.65
#Mann= 8 ,-1 , 0
  4041.9     .05       0  4079.5      .1       0  4466.4     .08       0
  4565.4     .05       0  4939.7     .08       0    4997     .07       0
    5003     .08       0  5159.8     .05       0
Bank Sta=4997,5003
XS Rating Curve= 0 ,0
Exp/Cntr=0.3,0.1

Type RM Length L Ch R = 1 ,11147   ,594,594,594
BEGIN DESCRIPTION:
Mapping XS 43496c94
END DESCRIPTION:
XS GIS Cut Line= 4
      2293723.88     13410729.44      2293185.65     13410733.78
      2292821.06     13411011.55      2292292.12     13411609.87
#Sta/Elev= 30
  4272.7  348.17  4274.8  348.12  4318.9  346.69  4428.9  345.23  4458.9  346.24
  4548.9  343.48  4833.5  342.58  4933.8  340.29    4997  337.59  4999.8  337.09
    5003  337.59  5060.7  339.96  5075.2  338.64  5197.8   339.2  5275.8  341.03
  5353.6  341.25  5445.6  343.63  5509.2  343.85  5572.7  345.81  5615.4  345.76
  5664.7  347.27  5721.6  347.49  5792.7  349.29  5799.4   350.3  5849.6  350.61
  5870.5  352.14  5948.3  352.55  5962.5  354.11  6026.1     354  6067.9  356.09
#Mann= 4 ,-1 , 0
  4272.7     .08       0  4274.8     .05       0    4997     .03       0
    5003     .05       0
Bank Sta=4997,5003
XS Rating Curve= 0 ,0
Exp/Cntr=0.3,0.1

Type RM Length L Ch R = 1 ,10695   ,362,362,362
BEGIN DESCRIPTION:
UNT046 IN SUCR 18.0
END DESCRIPTION:
XS GIS Cut Line= 5
      2293211.69     13410638.29       2292716.9     13410547.14
      2292638.77     13410620.93      2292604.05     13410742.46
       2292048.5     13411410.85
#Sta/Elev= 30
  4421.6   342.7  4486.6  342.35  4547.7  340.43    4997  336.72  4999.8  336.22
    5003  336.72  5229.5  339.08  5307.6  341.58    5322  341.69  5329.8  340.57
  5336.3  341.71  5364.9  342.82  5428.7  343.51  5436.5  344.71  5528.4   345.2
  5549.8  347.24  5578.5  346.67  5627.9  348.45  5656.6  348.06  5720.4   349.2
  5734.7  350.39  5790.7  350.44  5833.7  352.65  5883.1  352.52  5926.1  354.75
  5940.4  353.69  5961.2  353.65  5983.4  354.13  6010.7  356.56  6027.7  356.65
#Mann= 3 ,-1 , 0
  4421.6     .05       0    4997    .035       0    5003     .05       0
Bank Sta=4997,5003
XS Rating Curve= 0 ,0
Exp/Cntr=0.3,0.1

Type RM Length L Ch R = 1 ,10553   ,533,533,533
BEGIN DESCRIPTION:
UNT046 IN SUCR 17.0
END DESCRIPTION:
XS GIS Cut Line= 5
      2293150.95     13410516.76      2292647.45       13410456.
      2292543.29      13410521.1      2292534.61     13410642.63
      2291892.47     13411319.47
#Sta/Elev= 30
    4380  340.47  4866.7  337.56  4884.5  340.32  4916.7  340.99  4922.6  339.67
    4932  341.33  4974.5  341.21  4989.8  342.75  4995.7  342.43    4997  337.24
  4999.8  336.74    5003  337.24  5004.4  342.71    5126   341.4  5153.7  337.97
  5175.1  337.24  5196.2  339.51  5288.4  341.03  5323.6  342.92    5451  344.95
  5507.6  344.64  5564.3  347.29  5585.3  346.59  5648.8  348.83  5769.3  350.99
  5790.4  350.35  5854.3  353.07  5889.5  352.76  5995.5  355.29  6064.8   358.5
#Mann= 3 ,-1 , 0
    4380     .05       0    4997     .03       0    5003     .05       0
Bank Sta=4997,5003
XS Rating Curve= 0 ,0
Exp/Cntr=0.3,0.1

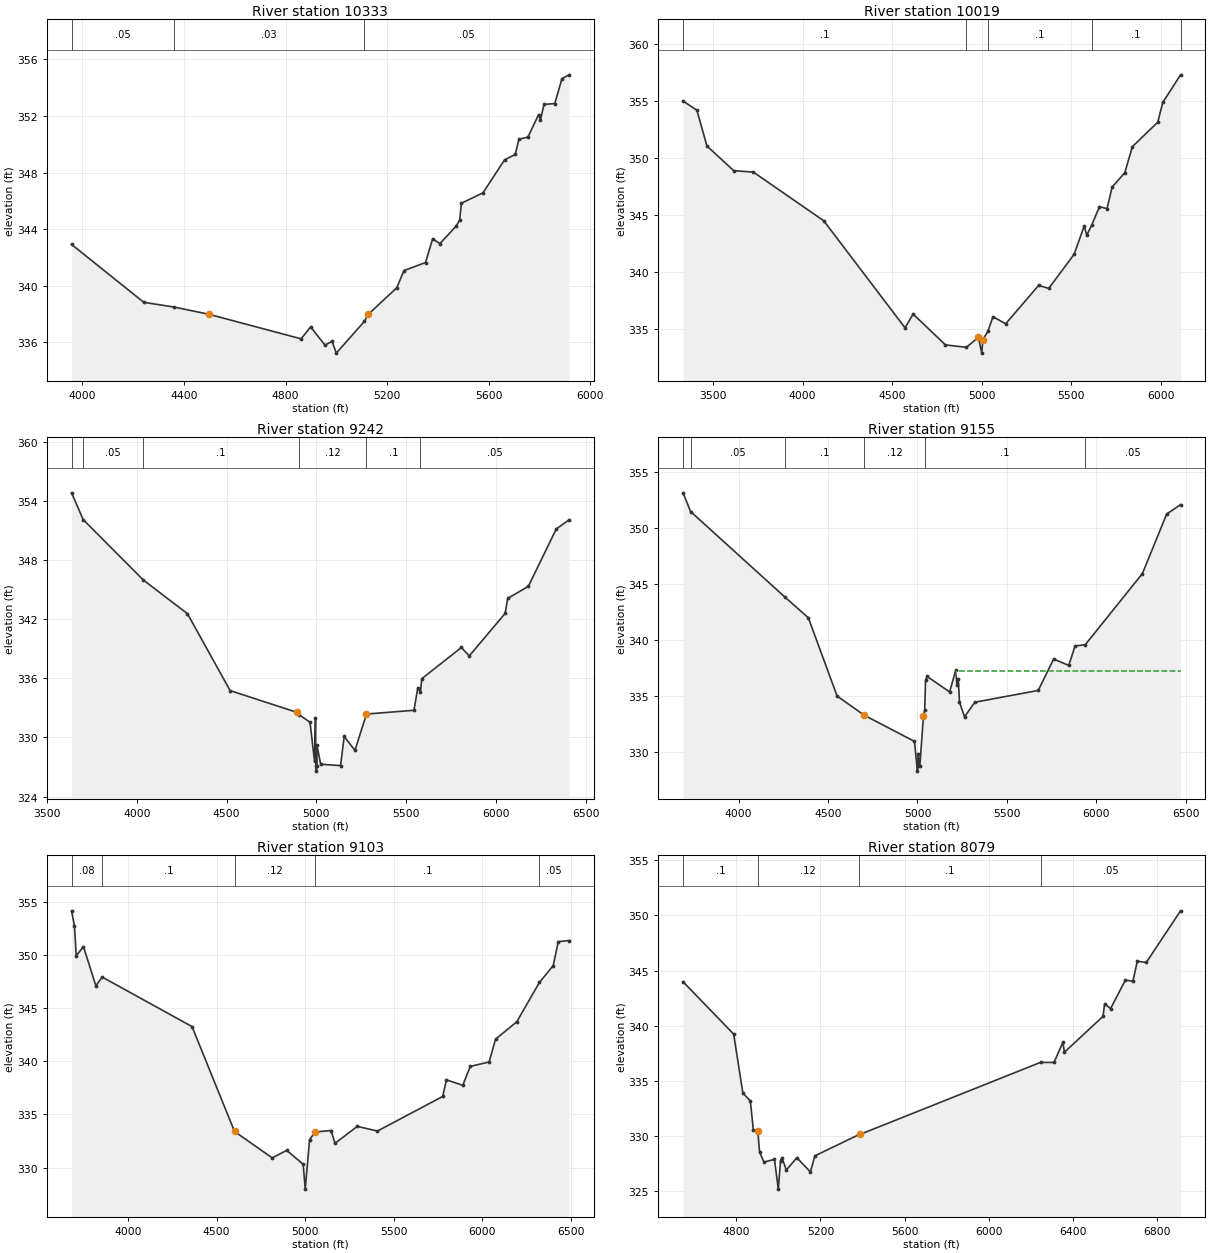
Type RM Length L Ch R = 1 ,10333   ,1092,1092,1092
BEGIN DESCRIPTION:
Mapping XS 8be2dd48
END DESCRIPTION:
XS GIS Cut Line= 3
      2293358.03     13410555.65      2292499.88     13410260.69
      2291753.86     13411002.38
#Sta/Elev= 30
  3957.1  342.92  4241.6  338.83  4359.2   338.5  4496.9  337.99  4861.2  336.25
  4898.7  337.09  4955.3  335.81  4983.5  336.07  4999.8  335.24  5110.8  337.49
    5125  337.97  5238.1  339.86  5266.4  341.07  5351.2  341.64  5379.5  343.32
  5407.8  342.97  5471.5  344.21  5485.6  344.63  5492.7  345.83  5577.5  346.56
  5662.4  348.89  5704.8  349.28  5718.9  350.35  5754.3   350.5  5796.7  352.09
  5803.8   351.7  5817.9  352.81  5860.4  352.87  5888.6  354.63  5916.5   354.9
#Mann= 3 ,-1 , 0
  3957.1     .05       0  4359.2     .03       0  5110.8     .05       0
Bank Sta=4496.9,5125
XS Rating Curve= 0 ,0
Exp/Cntr=0.3,0.1

Type RM Length L Ch R = 1 ,10019   ,864,864,864
BEGIN DESCRIPTION:
UNT046 IN SUCR 16.0
END DESCRIPTION:
XS GIS Cut Line= 3
      2293887.68     13409496.87      2292337.72     13410046.85
      2291537.73     13410846.84
#Sta/Elev= 30
  3333.1  355.01  3410.2   354.2  3466.7  351.06  3615.7  348.91  3725.7  348.78
  4118.3  344.52  4571.6  335.15    4617  336.35  4797.4  333.65  4914.1  333.44
  4981.3  334.32  4999.8  332.93    5006   334.1  5034.3  334.86  5062.6  336.12
  5133.3   335.5  5317.2  338.86  5373.7   338.6  5515.1  341.58  5571.7  344.07
  5585.9  343.26  5614.1  344.16  5656.6  345.76    5699  345.58  5727.3  347.47
    5798  348.73  5840.4  351.01  5981.8  353.15  6010.1  354.88  6109.1   357.3
#Mann= 5 ,-1 , 0
  3333.1      .1       0  4914.1     .12       0  5034.3      .1       0
  5614.1      .1       0  6109.1     .05       0
Bank Sta=4981.3,5006
XS Rating Curve= 0 ,0
Exp/Cntr=0.3,0.1

Type RM Length L Ch R = 1 ,9242    ,1163,1163,1163
BEGIN DESCRIPTION:
Mapping XS 954ec16b
END DESCRIPTION:
XS GIS Cut Line= 6
      2293824.97     13409411.96       2292505.6     13409555.89
      2292430.29     13409572.83      2292332.63       13409575.
      2292287.06     13409585.85      2291548.49     13410556.62
#Sta/Elev= 30
  3637.3  354.85  3702.2  352.13  4036.9  345.99  4282.6  342.57  4519.8  334.76
  4891.9  332.55    4902  332.33  4964.5  331.55  4989.8  327.56  4994.9     332
    4997  327.08  4999.8  326.58    5003  327.08  5003.3  329.21  5023.8  327.28
  5134.3  327.14  5154.7   330.1  5214.4  328.69  5278.8  332.38  5542.9  332.76
  5564.4  335.05  5578.9  334.58  5586.5  335.97    5807  339.14  5850.6  338.28
  6050.2   342.6  6064.7  344.13  6179.1  345.34  6335.1  351.18    6406   352.1
#Mann= 6 ,-1 , 0
  3637.3     .08       0  3702.2     .05       0  4036.9      .1       0
    4902     .12       0  5278.8      .1       0  5578.9     .05       0
Bank Sta=4891.9,5278.8
XS Rating Curve= 0 ,0
Exp/Cntr=0.3,0.1

Type RM Length L Ch R = 1 ,9155    ,52,52,52
BEGIN DESCRIPTION:
UNT046 IN SUCR 15.0
END DESCRIPTION:
XS GIS Cut Line= 5
      2293804.17     13409354.66      2292423.95      13409505.7
      2292293.74     13409526.54      2292241.66     13409573.41
      2291486.46     13410495.28
#Sta/Elev= 30
  3689.1  353.12  3731.3  351.45  4258.9  343.83  4389.7  341.99  4550.7  335.01
  4701.6  333.31  4983.2  330.97  4999.8  328.32    5003  328.82  5003.3  329.85
  5013.4  328.82  5033.5  333.24  5040.4  333.78  5045.4  336.45  5053.6  336.76
  5179.9  335.38  5214.1  337.32  5220.8  335.97  5228.3  336.51    5235  334.47
  5263.4  333.16  5320.7  334.46  5675.3  335.51  5761.4  338.31  5846.1  337.74
  5881.3  339.47  5938.7  339.59  6258.1  345.93  6393.7  351.23  6471.2  352.07
#Mann= 6 ,-1 , 0
  3689.1     .08       0  3731.3     .05       0  4258.9      .1       0
  4701.6     .12       0  5040.4      .1       0  5938.7     .05       0
#XS Ineff= 2 , 0
                         5216.48          337.28
Permanent Ineff=
       F       F
Bank Sta=4701.6,5033.5
XS Rating Curve= 0 ,0
Exp/Cntr=0.3,0.1

Type RM Length L Ch R = 1 ,9103    ,1703,1703,1703
BEGIN DESCRIPTION:
Mapping XS cf1a1d8a
END DESCRIPTION:
XS GIS Cut Line= 4
      2293814.11     13409315.31      2292451.27     13409458.54
      2292255.95     13409506.28      2291444.29     13410439.48
#Sta/Elev= 30
  3680.7  354.13  3697.2  352.72  3707.2   349.9  3747.9  350.77  3817.8  347.09
  3854.2   347.9  4360.8  343.25  4600.7  333.39  4813.3  330.91  4895.1  331.61
  4988.2  330.31  4999.8  327.97  5024.4  332.62  5055.4  333.35  5056.4  333.34
  5145.7  333.48  5167.9  332.27  5293.4  333.87  5407.3  333.43  5775.7  336.68
  5796.6  338.24    5889  337.73  5931.5  339.51  6037.8  339.92  6073.9  342.06
  6193.9   343.7  6321.7   347.4  6399.6  348.98  6428.1  351.23  6488.9  351.34
#Mann= 5 ,-1 , 0
  3680.7     .08       0  3854.2      .1       0  4600.7     .12       0
  5056.4      .1       0  6321.7     .05       0
Bank Sta=4600.7,5055.4
XS Rating Curve= 0 ,0
Exp/Cntr=0.3,0.1

Type RM Length L Ch R = 1 ,8079    ,1592,1592,1592
BEGIN DESCRIPTION:
UNT046 IN SUCR 14.0
END DESCRIPTION:
XS GIS Cut Line= 3
      2292933.05     13408524.56      2292349.71     13409311.03
      2291422.89     13410341.98
#Sta/Elev= 30
  4546.8  343.98  4787.4  339.23  4831.3  333.87  4866.7  333.17  4881.3   330.5
  4902.2  330.46  4910.6  328.52  4931.4  327.61  4981.5  327.85  4999.8  325.15
  5010.3  327.74    5017  328.01  5037.8  326.89  5087.9     328  5152.6  326.71
  5173.4  328.17  5382.1  330.09  5388.4  330.12  6246.5  336.66  6310.6  336.65
  6353.2  338.49    6360  337.58  6543.8  340.84  6551.3  341.98  6579.7  341.54
    6650  344.13  6685.9  344.03  6706.8  345.85  6749.4  345.73  6912.3  350.42
#Mann= 4 ,-1 , 0
  4546.8      .1       0  4902.2     .12       0  5382.1      .1       0
  6246.5     .05       0
Bank Sta=4902.2,5388.4
XS Rating Curve= 0 ,0
Exp/Cntr=0.3,0.1

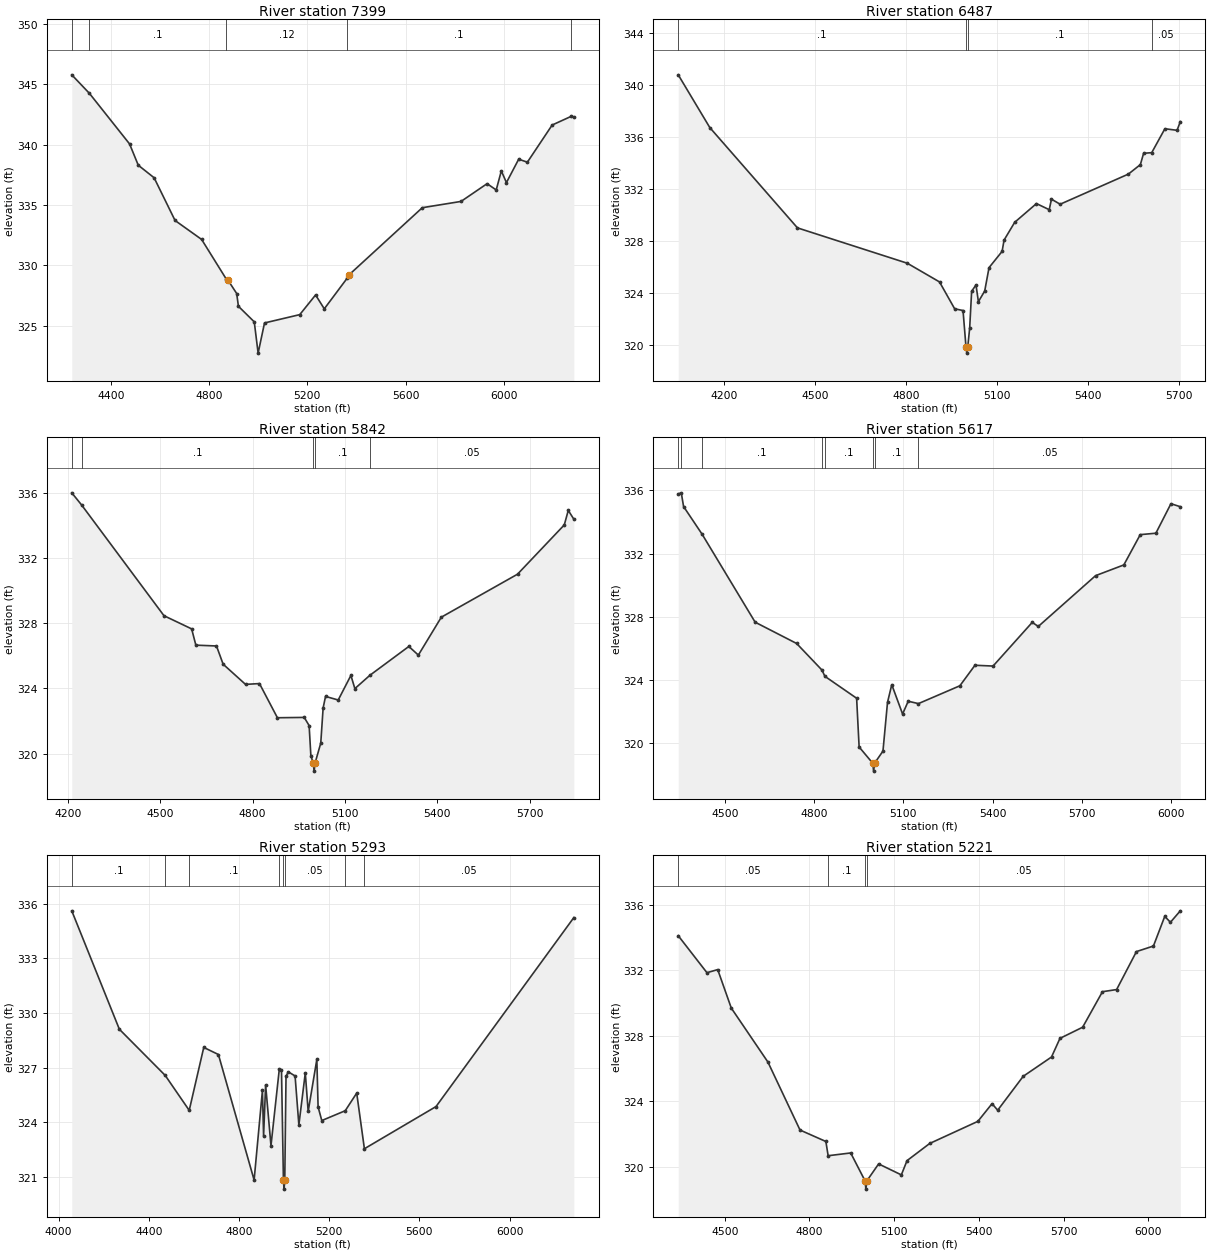
Type RM Length L Ch R = 1 ,7399    ,1558,1558,1558
BEGIN DESCRIPTION:
UNT046 IN SUCR 13.0
END DESCRIPTION:
XS GIS Cut Line= 3
      2292683.05     13408331.86      2291948.67     13409300.62
      2291443.48     13409956.83
#Sta/Elev= 30
  4241.2  345.78  4313.2  344.24  4476.6  340.05  4511.9  338.29  4576.4  337.25
  4661.7  333.71  4769.8  332.14  4869.7  328.87    4876   328.8  4912.5  327.66
  4919.6   326.6  4984.1  325.31  4999.8  322.72  5025.8  325.22  5169.3  325.91
  5233.7  327.54  5269.1  326.39  5362.7  328.94    5369  329.19  5668.1  334.77
  5825.8  335.29  5931.8  336.76    5969  336.24  5989.8  337.82  6010.6  336.85
  6060.5  338.79  6095.8  338.54  6196.7  341.62  6274.3  342.34    6285   342.3
#Mann= 5 ,-1 , 0
  4241.2     .05       0  4313.2      .1       0  4869.7     .12       0
  5362.7      .1       0  6274.3     .05       0
Bank Sta=4876,5369
XS Rating Curve= 0 ,0
Exp/Cntr=0.3,0.1

Type RM Length L Ch R = 1 ,6487    ,870,870,870
BEGIN DESCRIPTION:
UNT046 IN SUCR 12.0
END DESCRIPTION:
XS GIS Cut Line= 4
      2292327.66     13408286.19      2292022.07     13408376.48
      2291390.13     13409147.31      2291362.35     13409487.57
#Sta/Elev= 30
  4047.5  340.76  4151.7   336.7  4440.9  328.98  4803.3  326.26  4909.7  324.82
  4959.7  322.75  4987.3  322.62    4997  319.84  4999.8  319.34    5003  319.84
  5009.3  321.29  5015.7   324.1  5030.1  324.59    5038   323.3  5058.8  324.12
  5073.1  325.92  5116.2  327.17  5122.7  328.04  5157.8  329.41  5229.6  330.85
  5271.8  330.38  5279.1  331.19  5307.8   330.8    5533  333.12  5572.5  333.85
  5583.2  334.72    5610  334.77  5653.4  336.61  5693.6  336.49  5704.3  337.16
#Mann= 4 ,-1 , 0
  4047.5      .1       0    4997     .07       0    5003      .1       0
    5610     .05       0
Bank Sta=4997,5003
XS Rating Curve= 0 ,0
Exp/Cntr=0.3,0.1

Type RM Length L Ch R = 1 ,5842    ,549,549,549
BEGIN DESCRIPTION:
UNT046 IN SUCR 11.0
END DESCRIPTION:
XS GIS Cut Line= 3
      2291637.72     13407796.85      2291237.72     13408496.85
      2291037.71      13409296.9
#Sta/Elev= 30
  4212.6  336.02  4244.7  335.27  4512.1  328.47    4602  327.66  4615.7  326.66
  4682.7  326.61  4704.3  325.49    4777  324.25  4822.3   324.3  4880.6   322.2
  4967.7  322.22  4983.6  321.72  4989.3  319.86    4997  319.42  4999.8  318.92
    5003  319.42  5021.4  320.64  5029.1   322.8  5036.9  323.51  5078.1  323.29
  5119.3   324.8  5132.2  323.99  5181.1  324.81  5307.5  326.58  5338.4  326.05
  5413.1  328.38  5660.5  331.02  5812.5  334.05  5825.4  334.94  5843.5   334.4
#Mann= 5 ,-1 , 0
  4212.6     .05       0  4244.7      .1       0    4997     .07       0
    5003      .1       0  5181.1     .05       0
Bank Sta=4997,5003
XS Rating Curve= 0 ,0
Exp/Cntr=0.3,0.1

Type RM Length L Ch R = 1 ,5617    ,396,396,396
BEGIN DESCRIPTION:
Mapping XS e546cc57
END DESCRIPTION:
XS GIS Cut Line= 5
      2291470.85     13407724.53      2291165.27     13408238.46
      2291144.44     13408266.24      2291137.49     13408321.79
      2290970.83     13409307.88
#Sta/Elev= 30
  4342.7  335.78  4352.9  335.85  4360.7  334.98  4423.2  333.22  4601.4  327.65
    4741   326.3  4826.4  324.61  4835.9  324.22  4942.7  322.83  4951.1  319.74
    4997  318.71  4999.8  318.21    5003  318.71  5031.3  319.48  5046.6  322.57
  5060.9  323.69  5097.3  321.83  5116.2  322.64  5150.6  322.49    5290  323.62
  5340.7  324.92  5401.6  324.87  5533.4  327.64  5553.7  327.38  5746.4   330.6
  5841.4  331.28  5896.7   333.2  5949.2  333.29  5999.9  335.16  6031.4  334.97
#Mann= 8 ,-1 , 0
  4342.7      .1       0  4352.9     .05       0  4423.2      .1       0
  4826.4     .05       0  4835.9      .1       0    4997     .07       0
    5003      .1       0  5150.6     .05       0
Bank Sta=4997,5003
XS Rating Curve= 0 ,0
Exp/Cntr=0.3,0.1

Type RM Length L Ch R = 1 ,5293    ,629,629,629
BEGIN DESCRIPTION:
UNT046 IN SUCR 10.0
END DESCRIPTION:
XS GIS Cut Line= 6
      2291427.82     13407680.86      2291177.83      13408165.2
       2290844.5     13408170.41      2290834.08     13408295.41
      2291073.67     13408357.91      2290912.46     13409309.54
#Sta/Elev= 30
  4058.1  335.62  4269.2  329.11  4472.7  326.57  4579.1  324.65  4643.6  328.11
  4708.6  327.72    4867  320.82  4903.9  325.75    4909  323.24    4918  326.05
  4941.8  322.71  4978.6   326.9  4988.4  326.87    4997  320.82  4999.8  320.32
    5003  320.82  5008.5  326.52  5018.6  326.77  5048.7  326.54  5065.5  323.85
    5094  326.71  5106.8  324.59  5145.2  327.45  5150.8  324.84  5167.2  324.09
  5271.2  324.63  5322.1   325.6  5356.2  322.54    5674  324.86  6285.3  335.25
#Mann= 8 ,-1 , 0
  4058.1      .1       0  4472.7     .05       0  4579.1      .1       0
  4978.6     .05       0    4997     .03       0    5003     .05       0
  5271.2      .1       0  5356.2     .05       0
Bank Sta=4997,5003
XS Rating Curve= 0 ,0
Exp/Cntr=0.3,0.1

Type RM Length L Ch R = 1 ,5221    ,905,905,905
BEGIN DESCRIPTION:
UNT046 IN SUCR 9.0
END DESCRIPTION:
XS GIS Cut Line= 4
      2291005.54     13407592.64      2290776.38     13408155.13
       2290748.6     13408405.13      2290818.05     13409321.79
#Sta/Elev= 30
  4335.2  334.12  4436.9  331.86    4475  332.05  4523.1   329.7  4652.9   326.4
  4766.5  322.25  4858.1  321.55  4866.1  320.68    4946  320.85    4997  319.14
  4999.8  318.64    5003  319.14  5044.9  320.18  5125.4  319.51  5145.5  320.38
  5225.9  321.43  5396.4  322.78  5446.6  323.86  5466.6  323.46  5556.9  325.53
  5657.2  326.71  5687.2  327.85  5767.5  328.53  5837.7   330.7  5887.8  330.83
    5958  333.15  6018.2  333.49  6058.3   335.3  6078.4  334.94  6113.4  335.64
#Mann= 4 ,-1 , 0
  4335.2     .05       0  4866.1      .1       0    4997     .03       0
    5003     .05       0
Bank Sta=4997,5003
XS Rating Curve= 0 ,0
Exp/Cntr=0.3,0.1