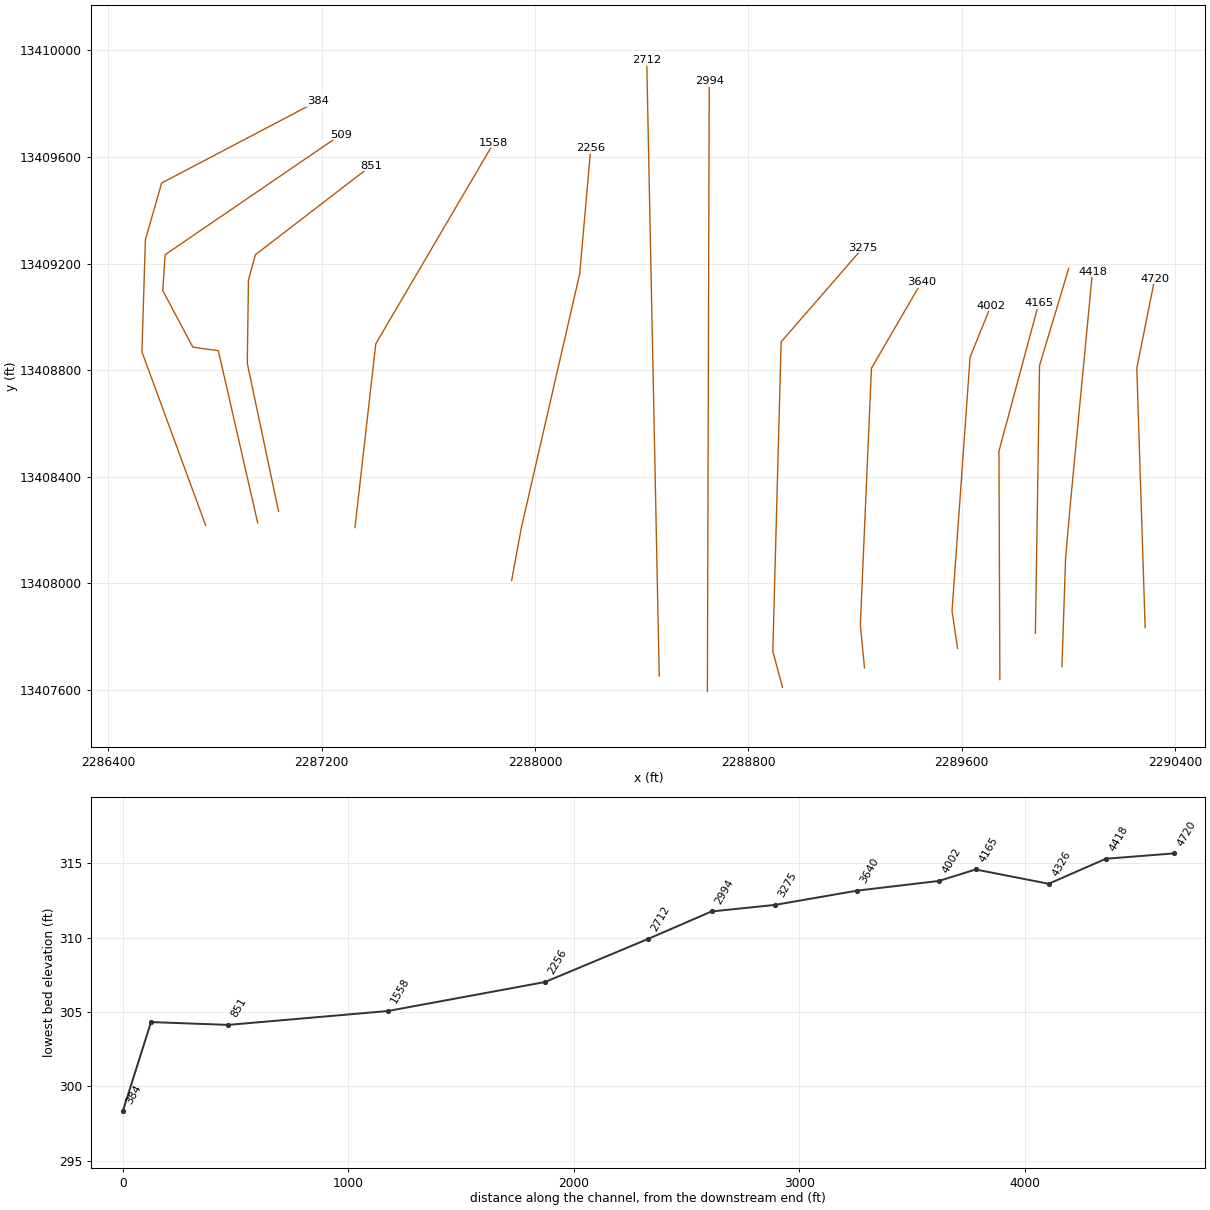
HEC-RAS study UNT046 IN SUCR.prj: UNT046 IN SUCR Base Level Engineering

--- UNT046 IN SUCR.g01 (geometry) --- (continued)

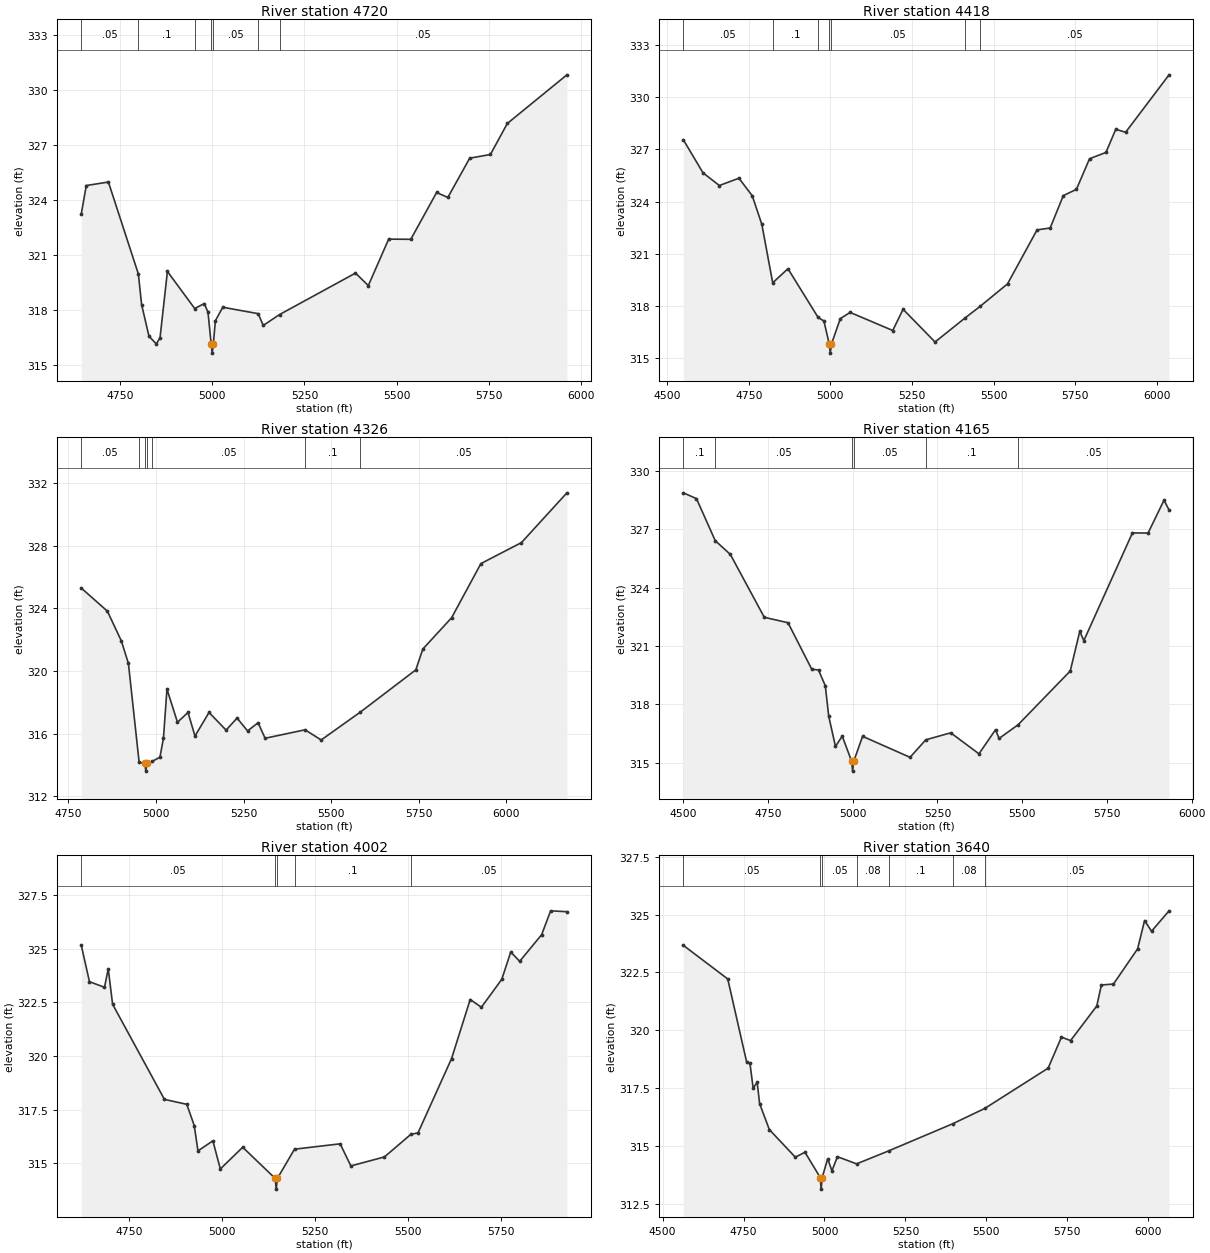
Type RM Length L Ch R = 1 ,4720    ,302,302,302
BEGIN DESCRIPTION:
UNT046 IN SUCR 8.0
END DESCRIPTION:
XS GIS Cut Line= 3
      2290287.69     13407833.08      2290256.45     13408807.03
      2290323.78     13409143.71
#Sta/Elev= 30
  4644.4  323.21  4658.2  324.78  4718.2  324.97  4799.5  319.96  4808.3  318.29
  4828.3  316.57  4848.3  316.15  4858.3  316.49  4878.3   320.1  4952.3  318.08
  4978.3  318.35  4988.4  317.88    4997  316.15  4999.8  315.65    5003  316.15
  5008.4  317.41  5028.4  318.15  5124.6   317.8  5138.4  317.16  5182.5  317.75
  5388.6  320.01  5423.4  319.33  5478.6  321.86  5538.6  321.85  5608.7   324.4
  5639.1  324.13  5698.5  326.27  5754.6  326.47  5800.5  328.16  5962.2  330.81
#Mann= 7 ,-1 , 0
  4644.4     .05       0  4799.5      .1       0  4952.3     .05       0
    4997     .03       0    5003     .05       0  5124.6      .1       0
  5182.5     .05       0
Bank Sta=4997,5003
XS Rating Curve= 0 ,0
Exp/Cntr=0.3,0.1

Type RM Length L Ch R = 1 ,4418    ,253,253,253
BEGIN DESCRIPTION:
UNT046 IN SUCR 7.1
END DESCRIPTION:
XS GIS Cut Line= 4
      2289975.71     13407686.64       2289989.6     13408096.36
      2290006.96     13408294.27      2290090.29     13409169.29
#Sta/Elev= 30
  4549.8  327.55    4610  325.65  4660.1  324.92  4720.1  325.34  4760.9  324.33
  4790.2  322.69  4823.5  319.33  4870.2  320.14  4962.6  317.34  4980.3  317.14
    4997  315.79  4999.8  315.29    5003  315.79  5030.5  317.27  5060.6  317.63
  5191.2  316.59  5222.8  317.81  5320.7  315.93  5413.3  317.32  5458.3  317.97
  5542.7  319.27  5633.1  322.37  5673.3  322.48  5713.5  324.34  5753.7   324.7
  5793.9  326.46  5844.1  326.82  5874.2  328.15  5904.4  327.98  6037.4  331.28
#Mann= 7 ,-1 , 0
  4549.8     .05       0  4823.5      .1       0  4962.6     .05       0
    4997     .03       0    5003     .05       0  5413.3      .1       0
  5458.3     .05       0
Bank Sta=4997,5003
XS Rating Curve= 0 ,0
Exp/Cntr=0.3,0.1

Type RM Length L Ch R = 1 ,4326    ,324,324,324
BEGIN DESCRIPTION:
UNT046 IN SUCR 7.0
END DESCRIPTION:
XS GIS Cut Line= 3
      2289876.24     13407812.21      2289891.86     13408817.45
      2290001.21     13409181.94
#Sta/Elev= 30
  4786.5  325.31  4861.2  323.83  4901.2  321.92  4921.2  320.49  4951.8  314.17
  4968.2  314.11  4970.9  313.61  4974.2  314.11  4988.9  314.23  5011.2   314.5
  5021.2  315.72  5031.2  318.85  5061.2  316.73  5091.2  317.36  5111.2  315.85
  5151.2  317.36  5199.9  316.23  5231.2     317  5261.2  316.18  5291.2   316.7
  5311.2  315.71  5425.3  316.25  5471.2   315.6  5582.9  317.38  5741.3  320.08
  5761.3  321.41  5843.4  323.41    5927  326.87  6042.7  328.21  6172.4  331.39
#Mann= 7 ,-1 , 0
  4786.5     .05       0  4951.8      .1       0  4968.2     .03       0
  4974.2      .1       0  4988.9     .05       0  5425.3      .1       0
  5582.9     .05       0
Bank Sta=4968.2,4974.2
XS Rating Curve= 0 ,0
Exp/Cntr=0.3,0.1

Type RM Length L Ch R = 1 ,4165    ,163,163,163
BEGIN DESCRIPTION:
UNT046 IN SUCR 7.0
END DESCRIPTION:
XS GIS Cut Line= 3
      2289743.07     13407638.02       2289739.6     13408495.66
       2289888.9      13409051.2
#Sta/Elev= 30
  4500.4  328.88  4539.2  328.58  4594.5  326.42  4639.2  325.71  4739.2  322.48
  4809.2   322.2  4879.2  319.81  4899.2  319.77  4919.2  318.96  4929.2   317.4
  4949.2  315.84  4969.2  316.37    4997  315.07  4999.8  314.57    5003  315.07
  5029.2  316.36  5169.2  315.28  5215.6  316.18  5289.2  316.54  5372.5  315.46
  5421.4   316.7  5431.8  316.25  5487.7  316.95  5641.9  319.72  5669.9  321.76
  5681.9  321.28  5825.3  326.82  5871.4  326.81  5918.4   328.5  5933.3     328
#Mann= 6 ,-1 , 0
  4500.4      .1       0  4594.5     .05       0    4997     .03       0
    5003     .05       0  5215.6      .1       0  5487.7     .05       0
Bank Sta=4997,5003
XS Rating Curve= 0 ,0
Exp/Cntr=0.3,0.1

Type RM Length L Ch R = 1 ,4002    ,362,362,362
BEGIN DESCRIPTION:
UNT046 IN SUCR 6.0
END DESCRIPTION:
XS GIS Cut Line= 4
      2289584.57     13407754.93      2289563.74     13407895.58
      2289631.45      13408848.7      2289709.59     13409041.45
#Sta/Elev= 30
  4621.1  325.17  4643.3  323.46  4683.7   323.2  4693.8  324.06  4705.5  322.41
  4844.8  317.98  4904.9  317.75    4925  316.76    4935  315.58  4975.1  316.05
  4995.1  314.74  5055.3  315.75  5142.5   314.3  5145.3   313.8  5148.5   314.3
  5194.5  315.66  5317.2  315.91    5346  314.88  5436.3   315.3  5507.2  316.35
  5526.5  316.42  5616.7  319.88  5666.8  322.63  5696.9  322.27  5751.7  323.57
  5775.8  324.84  5799.9  324.41  5858.9  325.65    5883  326.76  5926.8  326.72
#Mann= 5 ,-1 , 0
  4621.1     .05       0  5142.5     .03       0  5148.5     .05       0
  5194.5      .1       0  5507.2     .05       0
Bank Sta=5142.5,5148.5
XS Rating Curve= 0 ,0
Exp/Cntr=0.3,0.1

Type RM Length L Ch R = 1 ,3640    ,365,365,365
BEGIN DESCRIPTION:
UNT046 IN SUCR 5.0
END DESCRIPTION:
XS GIS Cut Line= 4
      2289235.61     13407682.07      2289219.99     13407843.49
      2289261.65     13408807.03      2289449.14     13409129.93
#Sta/Elev= 30
  4564.2  323.67  4701.3  322.22  4759.8  318.63  4769.8  318.59  4779.8  317.51
  4792.2  317.76  4799.8  316.84  4829.8  315.72  4909.9  314.53  4939.9  314.74
    4987  313.65  4989.7  313.15    4993  313.65    5010  314.46  5023.1  313.94
    5040  314.55  5099.3  314.24  5198.2   314.8  5395.9  315.97  5494.8  316.63
  5690.8  318.37  5731.9  319.71    5760  319.56  5840.9  321.05  5855.3  321.96
  5892.5     322  5967.1  323.52  5988.6  324.74  6010.1  324.28  6064.2  325.16
#Mann= 7 ,-1 , 0
  4564.2     .05       0    4987     .03       0    4993     .05       0
  5099.3     .08       0  5198.2      .1       0  5395.9     .08       0
  5494.8     .05       0
Bank Sta=4987,4993
XS Rating Curve= 0 ,0
Exp/Cntr=0.3,0.1

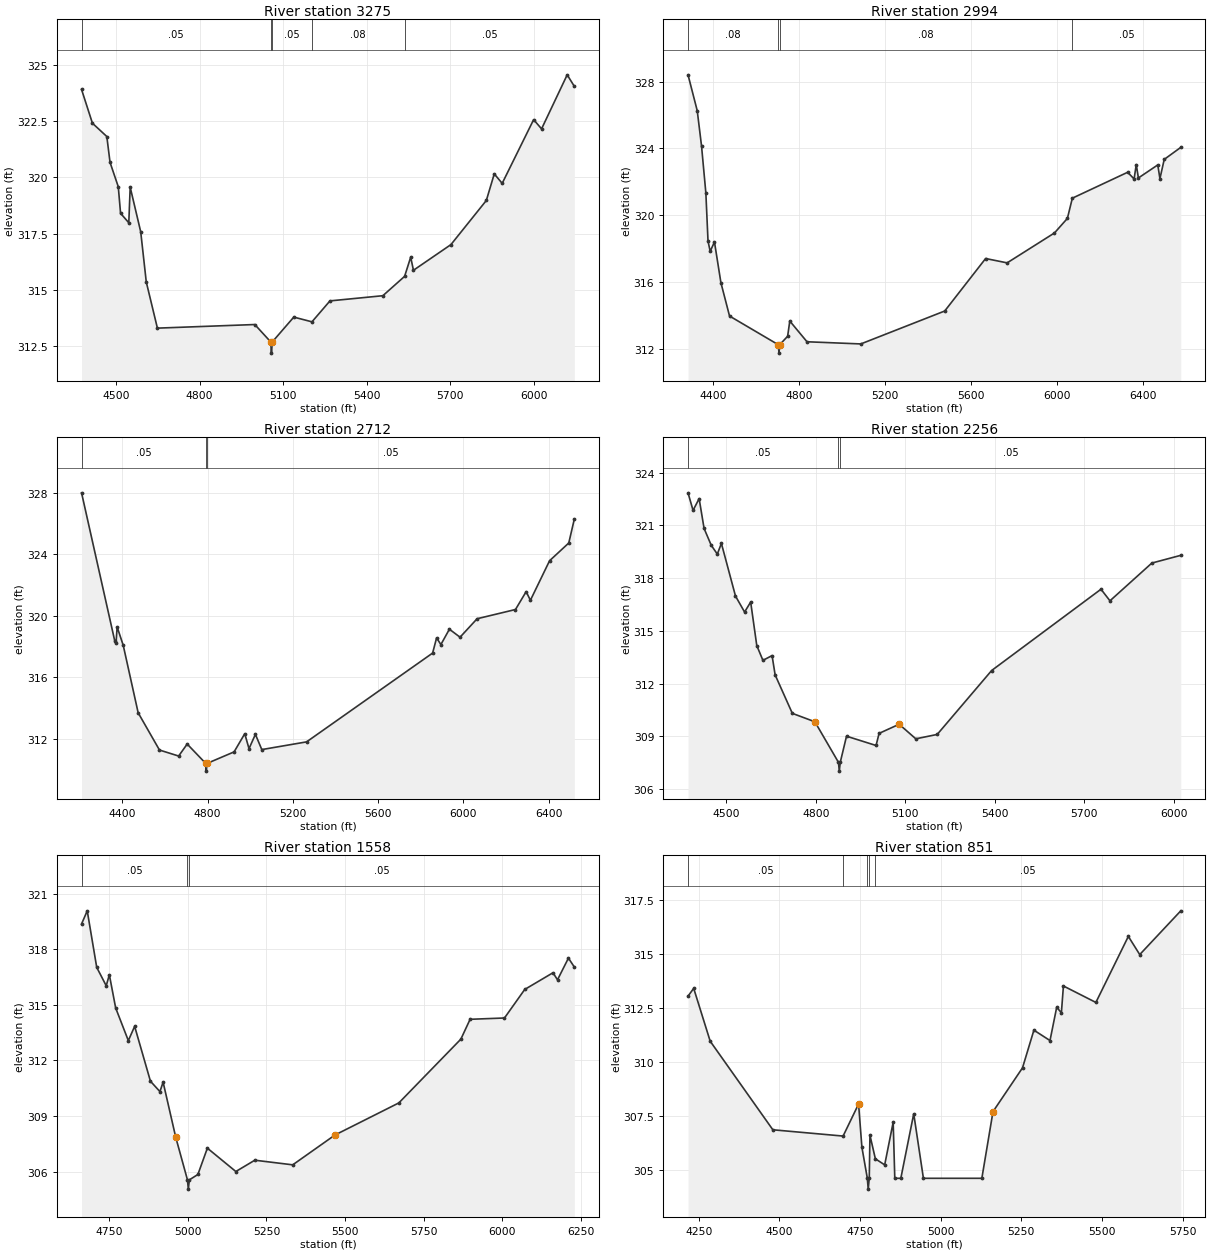
Type RM Length L Ch R = 1 ,3275    ,281,281,281
BEGIN DESCRIPTION:
UNT046 IN SUCR 4.0
END DESCRIPTION:
XS GIS Cut Line= 4
      2288928.31     13407609.14      2288891.86     13407744.53
      2288923.11     13408905.99      2289230.41     13409260.17
#Sta/Elev= 30
  4375.5   323.9  4414.6   322.4  4466.3  321.81  4477.9  320.66  4507.5  319.58
  4515.7   318.4  4545.3  317.98  4550.3  319.56  4588.1  317.58  4608.1  315.35
  4648.1   313.3  4998.2  313.46  5055.2  312.69    5058  312.19  5061.2  312.69
  5138.3  313.79  5203.6  313.58  5268.3  314.51  5458.4  314.74  5536.6   315.6
  5558.4  316.45  5568.4  315.87  5703.1  317.01  5830.3  318.97  5858.8  320.15
  5887.3  319.73  6000.3  322.56  6028.8  322.15  6120.9  324.55  6146.5  324.04
#Mann= 5 ,-1 , 0
  4375.5     .05       0  5055.2     .03       0  5061.2     .05       0
  5203.6     .08       0  5536.6     .05       0
Bank Sta=5055.2,5061.2
XS Rating Curve= 0 ,0
Exp/Cntr=0.3,0.1

Type RM Length L Ch R = 1 ,2994    ,282,282,282
BEGIN DESCRIPTION:
UNT046 IN SUCR 3.0
END DESCRIPTION:
XS GIS Cut Line= 2
      2288646.58       13407594.      2288653.52     13409883.79
#Sta/Elev= 30
    4285   328.4  4327.9  326.25  4347.9  324.13  4367.9  321.33  4377.9  318.46
  4387.9  317.84  4407.9   318.4  4437.9  315.96  4477.9  313.97  4704.9  312.25
  4707.6  311.75  4710.9  312.25  4747.9  312.76  4757.9  313.67  4837.9  312.43
  5087.9   312.3  5477.9  314.27  5667.9  317.41  5767.9  317.15  5987.9  318.94
  6047.9  319.81  6070.9  321.02  6327.9  322.57  6357.9  322.17  6367.9  323.03
  6377.9  322.23  6467.9  323.01  6477.9  322.19  6497.9  323.34  6574.8  324.06
#Mann= 4 ,-1 , 0
    4285     .08       0  4704.9     .07       0  4710.9     .08       0
  6070.9     .05       0
Bank Sta=4704.9,4710.9
XS Rating Curve= 0 ,0
Exp/Cntr=0.3,0.1

Type RM Length L Ch R = 1 ,2712    ,456,456,456
BEGIN DESCRIPTION:
UNT046 IN SUCR 2.0
END DESCRIPTION:
XS GIS Cut Line= 2
      2288466.03     13407651.31      2288419.17     13409962.84
#Sta/Elev= 30
  4208.9  327.98  4364.5  318.37  4370.8  318.23  4375.8  319.27  4404.5  318.07
  4474.5  313.69  4574.5  311.27  4664.5  310.88  4704.5  311.66  4791.6   310.4
  4794.3   309.9  4797.6   310.4  4924.6  311.15  4974.6  312.33  4994.6  311.36
  5024.6  312.29  5054.6   311.3  5264.7   311.8  5856.1  317.57  5874.8  318.56
  5894.8  318.12  5934.8  319.12  5984.8   318.6  6064.8   319.8  6244.9   320.4
  6294.9  321.56  6314.9     321  6404.9  323.57  6494.9  324.72  6520.9  326.27
#Mann= 3 ,-1 , 0
  4208.9     .05       0  4791.6    .035       0  4797.6     .05       0
Bank Sta=4791.6,4797.6
XS Rating Curve= 0 ,0
Exp/Cntr=0.3,0.1

Type RM Length L Ch R = 1 ,2256    ,698,698,698
BEGIN DESCRIPTION:
Mapping XS 1324efdf
END DESCRIPTION:
XS GIS Cut Line= 4
       2287912.7     13408010.19      2287949.15     13408208.08
       2288167.9      13409161.2      2288209.43     13409633.55
#Sta/Elev= 30
  4370.9  322.86  4387.8  321.86  4408.2  322.53  4424.8  320.83  4448.9  319.87
  4469.2  319.37  4482.9  319.98  4530.2  316.98  4560.7  316.07  4581.1  316.64
  4601.6  314.16  4622.2  313.32  4652.9  313.59  4663.2  312.49  4720.9   310.3
  4796.6  309.82  4875.7  307.51  4878.4  307.01  4881.7  307.51  4902.7     309
  5001.8  308.47    5012  309.16  5079.3  309.68  5135.2  308.85    5207   309.1
  5389.6  312.74  5756.5  317.37  5786.6  316.71  5927.1  318.86  6024.2   319.3
#Mann= 3 ,-1 , 0
  4370.9     .05       0  4875.7    .035       0  4881.7     .05       0
Bank Sta=4796.6,5079.3
XS Rating Curve= 0 ,0
Exp/Cntr=0.3,0.1

Type RM Length L Ch R = 1 ,1558    ,707,707,707
BEGIN DESCRIPTION:
Mapping XS bd5ae325
END DESCRIPTION:
XS GIS Cut Line= 3
       2287325.4      13408208.9      2287403.53       13408899.
      2287845.53     13409652.99
#Sta/Elev= 30
  4661.3  319.36  4679.4  320.07  4709.6  317.02  4739.8  316.03  4749.8  316.62
  4769.9  314.83  4810.2  313.07  4830.3  313.84  4880.6  310.88  4910.8  310.32
  4920.9  310.83  4961.2  307.85  4998.4  305.56  5001.2  305.06  5004.4  305.56
  5031.6  305.85  5061.8  307.27  5152.4  306.01  5212.8  306.62  5333.5  306.37
  5468.1  307.98  5671.3  309.71  5868.7  313.15  5898.1  314.22  6007.5  314.29
    6072  315.83  6161.9  316.73  6176.3  316.35  6211.1  317.52  6229.8  317.04
#Mann= 3 ,-1 , 0
  4661.3     .05       0  4998.4    .035       0  5004.4     .05       0
Bank Sta=4961.2,5468.1
XS Rating Curve= 0 ,0
Exp/Cntr=0.3,0.1

Type RM Length L Ch R = 1 ,851     ,342,342,342
BEGIN DESCRIPTION:
Mapping XS d94d1e90
END DESCRIPTION:
XS GIS Cut Line= 5
      2287038.95     13408269.61      2286921.76     13408825.21
       2286926.1     13409137.71      2286952.14      13409233.2
      2287386.16     13409567.39
#Sta/Elev= 30
  4217.1  313.04  4234.7   313.4  4285.8  310.96    4480  306.87  4697.7  306.58
  4745.7  308.06  4755.9  306.07  4772.8  304.63  4775.5  304.13  4778.8  304.63
  4780.9  306.62  4797.7  305.53  4826.6  305.25  4852.9  307.22  4857.9  304.63
  4876.6  304.63  4916.6  307.61  4946.6  304.63  5127.7  304.63  5162.3  307.71
  5253.7  309.73    5289  311.47  5338.9  310.99  5359.7  312.53  5374.2  312.27
  5380.5  313.51  5481.1  312.75  5581.7   315.8    5617  314.96  5744.2  316.98
#Mann= 5 ,-1 , 0
  4217.1     .05       0  4697.7      .1       0  4772.8    .033       0
  4778.8      .1       0  4797.7     .05       0
Bank Sta=4745.7,5162.3
XS Rating Curve= 0 ,0
Exp/Cntr=0.3,0.1

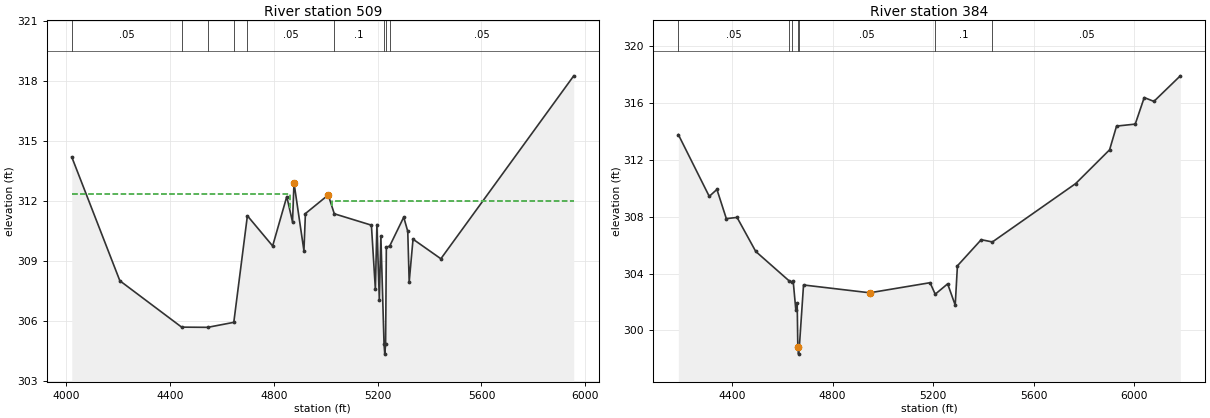
Type RM Length L Ch R = 1 ,509     ,125,125,125
BEGIN DESCRIPTION:
Mapping XS 987d58fe
END DESCRIPTION:
XS GIS Cut Line= 6
      2286960.83     13408226.23      2286813.25     13408872.95
      2286717.76     13408885.97      2286604.92     13409098.65
       2286613.6      13409233.2        2287273.     13409684.36
#Sta/Elev= 30
  4021.1  314.18  4206.4  307.99  4444.5  305.67    4545  305.66  4645.5  305.91
  4697.9  311.24  4795.2  309.73  4849.7   312.2  4871.8  310.93  4877.5  312.89
  4915.8  309.49  4921.5  311.35  5009.4  312.28  5032.8  311.34  5175.8  310.77
  5191.1  307.57    5197   310.8  5206.3  307.05  5212.3  310.22  5224.5  304.82
  5227.3  304.32  5230.5  304.82  5233.4  309.66  5246.4  309.73  5300.4  311.17
  5315.9  310.46  5321.4  307.93  5336.2  310.07  5443.5  309.09  5955.5  318.24
#Mann= 9 ,-1 , 0
  4021.1     .05       0  4444.5      .1       0    4545     .05       0
  4645.5      .1       0  4697.9     .05       0  5032.8      .1       0
  5224.5     .03       0  5230.5      .1       0  5246.4     .05       0
#XS Ineff= 2 , 0
       0  4862.5  312.35 5022.73       0  311.99
Permanent Ineff=
       T       T
Bank Sta=4877.5,5009.4
XS Rating Curve= 0 ,0
Exp/Cntr=0.3,0.1

Type RM Length L Ch R = 1 ,384     ,0,0,0
BEGIN DESCRIPTION:
UNT046 IN SUCR 1.0
END DESCRIPTION:
XS GIS Cut Line= 5
      2286765.51     13408217.57      2286526.79     13408868.61
      2286539.81     13409289.62      2286600.58     13409502.29
      2287186.47     13409810.43
#Sta/Elev= 30
  4185.9  313.79  4308.9  309.44  4339.4  309.93  4376.9  307.87  4419.5  307.96
    4494  305.56  4626.8  303.49  4636.7  303.43  4643.1  303.45  4653.6  301.41
  4658.9  301.92  4661.4  298.83  4664.2  298.33  4667.4  298.83  4684.1   303.2
  4947.6  302.65  5187.7  303.36  5208.2  302.55  5257.7  303.28  5287.8  301.78
  5296.6  304.55  5391.3  306.39  5435.8  306.23  5767.1  310.34  5902.2  312.72
  5929.9  314.39  6004.3  314.53  6040.1   316.4  6078.6  316.13  6183.7  317.93
#Mann= 7 ,-1 , 0
  4185.9     .05       0  4626.8      .1       0  4636.7     .05       0
  4661.4     .03       0  4667.4     .05       0  5208.2      .1       0
  5435.8     .05       0
Bank Sta=4661.4,4947.6
XS Rating Curve= 0 ,0
Exp/Cntr=0.3,0.1

Chan Stop Cuts=-1
Use User Specified Reach Order=0
Composite Channel Slope=5