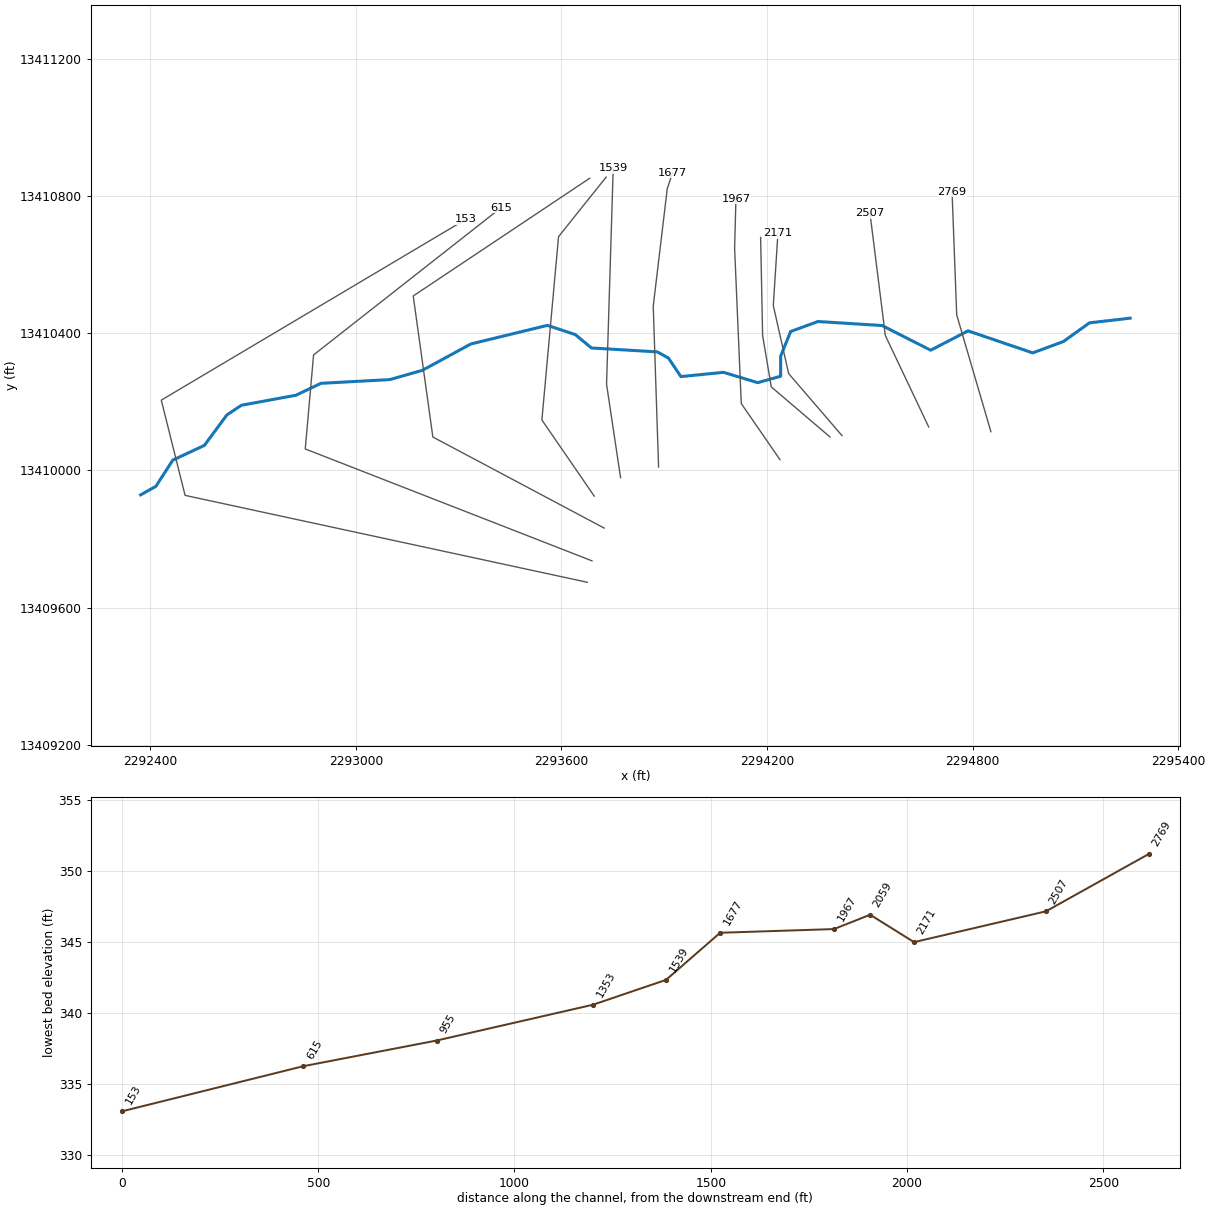
--- UNT047 IN SUCR.prj (project) ---

Proj Title=UNT047 IN SUCR Base Level Engineering
Current Plan=p01
Default Exp/Contr=0.3,0.1
English Units
Geom File=g01
Flow File=f01
Plan File=p01
Y Axis Title=Elevation
X Axis Title(PF)=Main Channel Distance
X Axis Title(XS)=Station
BEGIN DESCRIPTION:
UNT047 IN SUCR
END DESCRIPTION:
DSS File=dss
DSS Export Rating Curves= 0
DSS Export Rating Curve Sorted= 0
DSS Export Volume Flow Curves= 0
DXF OffsetX= 0
DXF OffsetY= 0
DXF ScaleX= 1
DXF ScaleY= 10

--- UNT047 IN SUCR.p01 (plan) ---

Plan Title=Multiple Run
Program Version=4.10
Short Identifier=Multiple Run
Geom File=g01
Flow File=f01
Subcritical Flow
K Sum by GR= 0
Std Step Tol= 0.01
Critical Tol= 0.01
Num of Std Step Trials= 20
Max Error Tol= 0.3
Flow Tol Ratio= 0.001
Split Flow NTrial= 30
Split Flow Tol= 0.02
Split Flow Ratio= 0.02
Log Output Level= 0
Friction Slope Method= 1
Unsteady Friction Slope Method= 2
Unsteady Bridges Friction Slope Method= 1
Parabolic Critical Depth
Global Vel Dist= 1 , 1 , 1
Global Log Level= 0
CheckData=True
Encroach Param=-1 ,0,0, 0
BEGIN DESCRIPTION:
Multiple Run
END DESCRIPTION:
Computation Interval=1HOUR
Output Interval=1HOUR
Run HTab= 0
Run UNet= 0
Run PostProcess= 0
Run WQNet= 0
UNET Theta= 1
UNET Theta Warmup= 1
UNET ZTol= 0.02
UNET ZSATol= 0.05
UNET MxIter= 20
UNET MaxInSteps= 0
UNET DtIC= 0
UNET DtMin= 0
UNET MaxCRTS= 20
UNET WFStab= 2
UNET SFStab= 1
UNET WFX= 1
UNET SFX= 1
UNET DSS MLevel= 4
UNET DZMax Abort= 100
UNET Convert EG Bridges= 0
UNET Use Existing IB Tables=-1
UNET Froude Reduction=False
UNET Froude Limit= 1
UNET Froude Power= 10
UNET Time Slicing=0,0, 5
UNET Junction Losses=0
Instantaneous Interval=1HOUR
DSS File=dss
Write IC File= 0
Write IC File at Sim End=0
Echo Input=False
Echo Parameters=False
Echo Output=False
Write Detailed= 0
WQ AD Non Conservative
WQ ULTIMATE=-1
WQ Max Comp Step=1HOUR
WQ Output Interval=15MIN
WQ Output Selected Increments= 0
WQ Output face flow=0
WQ Output face velocity=0
WQ Output face area=0
WQ Output face dispersion=0
WQ Output cell volume=0
WQ Output cell surface area=0
WQ Output cell continuity=0
WQ Output cumulative cell continuity=0
WQ Output face conc=0
WQ Output face dconc_dx=0
WQ Output face courant=0
WQ Output face peclet=0
WQ Output face adv mass=0
WQ Output face disp mass=0
WQ Output cell mass=0
WQ Output cell source sink temp=0
WQ Output cell source sink nsm=0
WQ Output MaxMinRange=-1
WQ Daily Max Min Mean=-1
WQ Daily Range=0
WQ Daily Time=0
WQ Create Restart=0
WQ Fixed Restart=0
WQ System Summary=0
WQ Use Fixed Temperature=0
Sorting and Armoring Iterations= 10
XS Update Threshold= 0.02
Hydraulics Update Threshold= 0.02
Energy Slope Method= 1
Volume Change Method= 0
XS Weighting Method= 0
Number of US Weighted Cross Sections= 1
Number of DS Weighted Cross Sections= 1
Upstream XS Weight=0.25
Main XS Weight=0.5
Downstream XS Weight=0.25
Number of DS XS's Weighted with US Boundary= 1
Upstream Boundary Weight= 1
Weight of XSs Associated with US Boundary= 0
Number of US XS's Weighted with DS Boundary= 1
Downstream Boundary Weight= 0.5
Weight of XSs Associated with DS Boundary= 0.5
Sediment Output Level= 4
Mass or Volume Output= 0
Output Increment Type= 1
Profile and TS Output Increment= 10
XS Output Flag= 0
XS Output Increment= 10
Disregard all LS=0
Disregard all Conn=0
Disregard all Breaches=0
Disregard all Pumps=0

--- UNT047 IN SUCR.f01 (steady flow) ---

Flow Title=Multiple
Program Version=4.10
Number of Profiles= 7
Profile Names=10-year,25-year,50-year,1pct_min,100-year,1pct_plu,500-year
River Rch & RM=UNT047 IN SUCR,Reach-1         ,2769
     614     873    1091     997    1348    1823    2065
River Rch & RM=UNT047 IN SUCR,Reach-1         ,1539
     623     885    1106    1010    1367    1848    2092
Boundary for River Rch & Prof#=UNT047 IN SUCR,Reach-1         , 1
Up Type= 0
Dn Type= 3
Dn Slope=0.0067
Boundary for River Rch & Prof#=UNT047 IN SUCR,Reach-1         , 2
Up Type= 0
Dn Type= 3
Dn Slope=0.0067
Boundary for River Rch & Prof#=UNT047 IN SUCR,Reach-1         , 3
Up Type= 0
Dn Type= 3
Dn Slope=0.0067
Boundary for River Rch & Prof#=UNT047 IN SUCR,Reach-1         , 4
Up Type= 0
Dn Type= 3
Dn Slope=0.0067
Boundary for River Rch & Prof#=UNT047 IN SUCR,Reach-1         , 5
Up Type= 0
Dn Type= 3
Dn Slope=0.0067
Boundary for River Rch & Prof#=UNT047 IN SUCR,Reach-1         , 6
Up Type= 0
Dn Type= 3
Dn Slope=0.0067
Boundary for River Rch & Prof#=UNT047 IN SUCR,Reach-1         , 7
Up Type= 0
Dn Type= 3
Dn Slope=0.0067
DSS Import GetInterval= 0
DSS Import GetPeak= 0
DSS Import FillOption= 0

--- UNT047 IN SUCR.g01 (geometry) ---

Geom Title=Existing Conditions
Program Version=4.10

River Reach=UNT047 IN SUCR  ,Reach-1
Reach XY= 30
      2295259.58     13410444.17      2295140.84     13410430.55
      2295064.93     13410376.05       2294975.4     13410342.96
      2294786.59     13410407.19      2294677.59     13410350.74
      2294535.51     13410422.76      2294348.65     13410434.44
      2294268.84     13410405.24      2294239.65     13410333.23
      2294239.65     13410274.83      2294172.88     13410256.09
      2294073.05     13410286.19      2293948.59     13410273.82
      2293912.13     13410327.99      2293879.66     13410345.83
      2293687.48     13410357.28      2293640.27     13410396.37
      2293559.16     13410423.25      2293335.83     13410369.02
      2293194.28     13410292.14      2293098.79     13410265.01
      2292898.06     13410254.16      2292825.36     13410219.44
      2292665.85     13410190.14      2292623.53     13410161.93
      2292557.93     13410073.04      2292465.71     13410030.08
       2292416.4     13409953.69       2292371.9     13409928.81

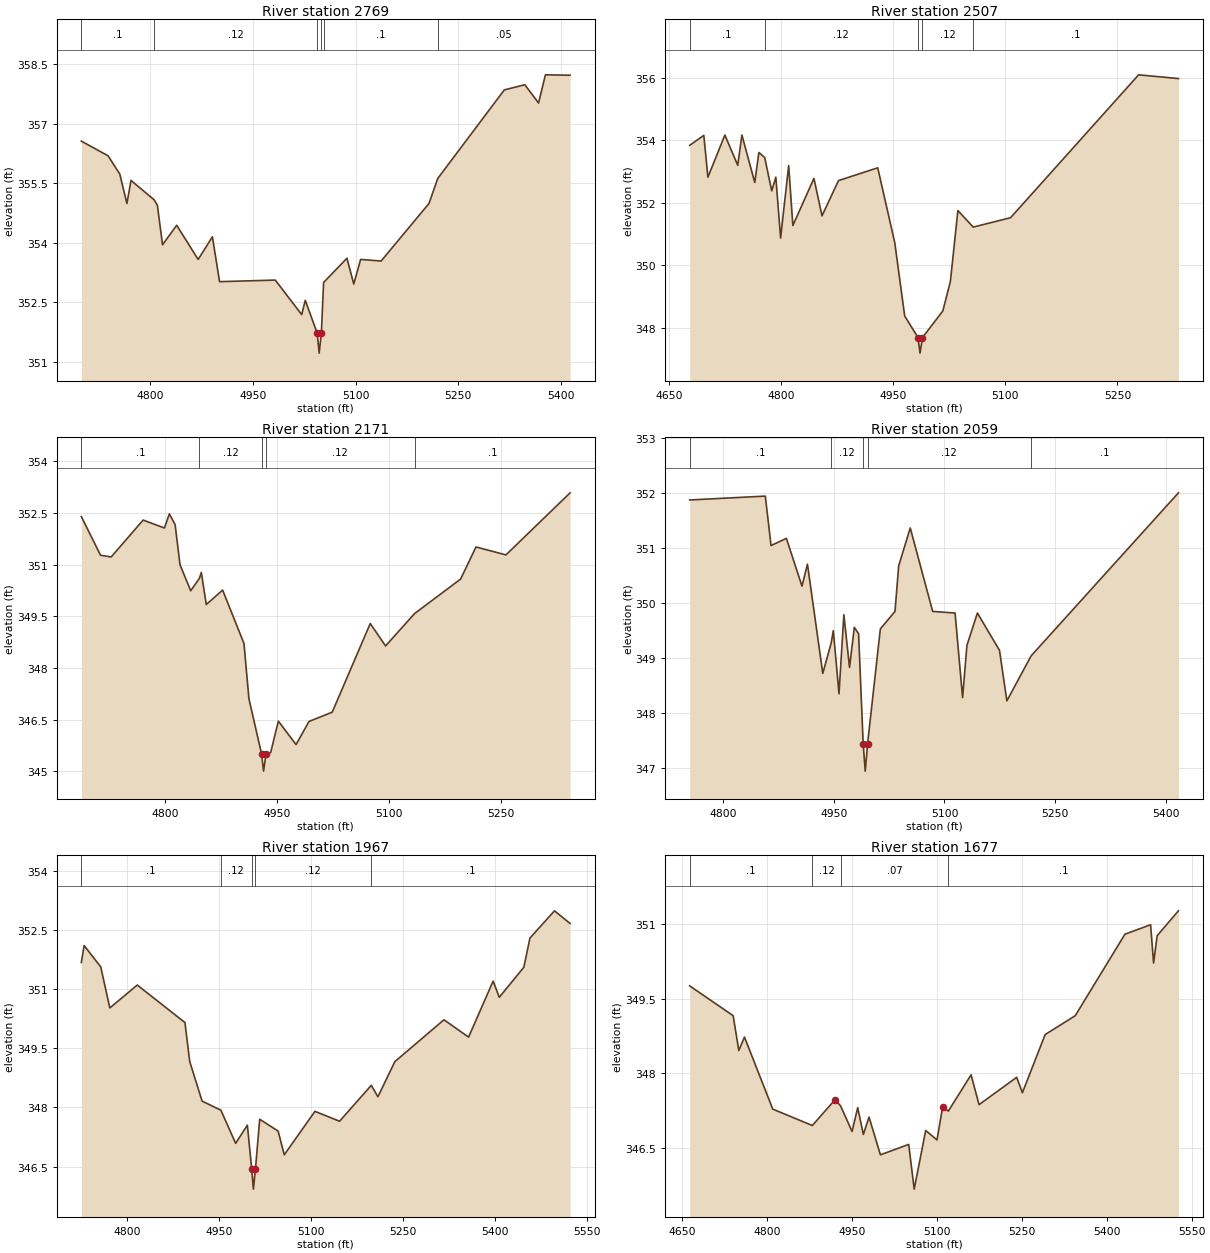
Type RM Length L Ch R = 1 ,2769    ,262,262,262
BEGIN DESCRIPTION:
UNT047 IN SUCR 1.0
END DESCRIPTION:
XS GIS Cut Line= 3
      2294853.31     13410112.92      2294753.51      13410453.9
      2294739.92     13410812.96
#Sta/Elev= 30
  4699.1  356.56  4738.2  356.19  4755.3  355.73  4765.7  354.99  4771.7  355.57
  4805.7  355.08  4810.3  354.94  4817.8  353.95  4838.5  354.44  4869.9  353.58
  4890.7  354.15  4901.2  353.02  4982.6  353.06  5021.3  352.19  5026.5  352.55
    5044  351.72  5046.8  351.22    5050  351.72  5053.3     353  5087.4  353.61
  5097.4  352.96  5107.4  353.58  5137.4  353.54  5207.4  354.99  5220.2  355.62
  5317.5  357.85  5347.5  357.98  5367.6  357.52  5377.6  358.23  5413.7  358.22
#Mann= 6 ,-1 , 0
  4699.1      .1       0  4805.7     .12       0    5044     .07       0
    5050     .12       0  5053.3      .1       0  5220.2     .05       0
Bank Sta=5044,5050
XS Rating Curve= 0 ,0
Exp/Cntr=0.3,0.1

Type RM Length L Ch R = 1 ,2507    ,336,336,336
BEGIN DESCRIPTION:
Mapping XS 909917f4
END DESCRIPTION:
XS GIS Cut Line= 3
      2294671.78     13410126.86      2294545.24     13410393.56
      2294500.47     13410749.76
#Sta/Elev= 30
  4677.5  353.84  4696.4  354.16  4701.9  352.82  4724.6  354.17  4741.8   353.2
  4747.4  354.17  4764.6  352.65  4770.1  353.61  4777.9  353.45  4787.3  352.38
  4792.8  352.82  4799.2  350.87    4810  353.19  4815.6  351.27  4843.8  352.78
  4854.6  351.58  4876.7  352.71  4929.2  353.12    4952  350.72  4965.3  348.37
  4983.1  347.68  4985.8  347.18  4989.1  347.68  5016.3  348.53  5026.4  349.47
  5036.5  351.75    5057  351.22    5107  351.52  5278.4   356.1  5331.7  355.98
#Mann= 5 ,-1 , 0
  4677.5      .1       0  4777.9     .12       0  4983.1     .07       0
  4989.1     .12       0    5057      .1       0
Bank Sta=4983.1,4989.1
XS Rating Curve= 0 ,0
Exp/Cntr=0.3,0.1

Type RM Length L Ch R = 1 ,2171    ,112,112,112
BEGIN DESCRIPTION:
Mapping XS 03f62e35
END DESCRIPTION:
XS GIS Cut Line= 4
      2294418.74     13410101.58      2294263.01     13410282.62
      2294218.24     13410481.15      2294231.82     13410692.59
#Sta/Elev= 30
  4688.4  352.39  4714.1  351.27  4728.3  351.22  4771.1  352.29  4799.6  352.06
  4806.2  352.47  4813.9  352.16  4820.5  350.99  4834.8  350.24  4846.4   350.6
    4849  350.77  4855.6  349.84  4877.5  350.26  4906.1  348.71  4912.7  347.11
  4929.6  345.51  4932.3  345.01  4935.6  345.51  4941.8  345.55  4952.1  346.46
  4975.8  345.78  4993.1  346.45  5024.2  346.72  5075.1  349.29  5095.6  348.64
  5134.5  349.58  5196.1  350.58  5216.6  351.51  5256.7  351.28  5342.6  353.08
#Mann= 5 ,-1 , 0
  4688.4      .1       0  4846.4     .12       0  4929.6     .07       0
  4935.6     .12       0  5134.5      .1       0
Bank Sta=4929.6,4935.6
XS Rating Curve= 0 ,0
Exp/Cntr=0.3,0.1

Type RM Length L Ch R = 1 ,2059    ,92,92,92
BEGIN DESCRIPTION:
Mapping XS 08b99688
END DESCRIPTION:
XS GIS Cut Line= 4
      2294383.69      13410097.7       2294212.4     13410243.69
      2294187.09     13410393.56      2294181.26     13410679.64
#Sta/Elev= 30
  4754.3  351.88  4856.9  351.95  4864.7  351.05  4885.5  351.18  4906.7  350.31
  4914.1  350.71  4934.9  348.72  4946.4  349.28  4949.2   349.5  4956.9  348.35
  4963.5  349.79  4971.2  348.83  4977.7  349.56  4983.5  349.44  4989.7  347.44
  4992.5  346.94  4995.7  347.44    5013  349.53  5032.9  349.85  5037.9  350.68
  5053.6  351.37    5084  349.85  5114.4  349.82  5124.6  348.28  5130.5  349.23
  5144.7  349.82  5174.7  349.14  5184.7  348.22  5217.6  349.04  5417.5  352.01
#Mann= 5 ,-1 , 0
  4754.3      .1       0  4946.4     .12       0  4989.7     .07       0
  4995.7     .12       0  5217.6      .1       0
Bank Sta=4989.7,4995.7
XS Rating Curve= 0 ,0
Exp/Cntr=0.3,0.1

Type RM Length L Ch R = 1 ,1967    ,290,290,290
BEGIN DESCRIPTION:
Mapping XS 0adc9f9f
END DESCRIPTION:
XS GIS Cut Line= 4
      2294237.68     13410031.56      2294124.81     13410195.03
      2294105.34     13410648.55      2294109.23     13410792.21
#Sta/Elev= 30
  4726.1  351.67  4730.6   352.1  4757.7  351.56  4772.5  350.52  4817.2   351.1
  4894.9  350.15  4902.7  349.16  4922.8  348.16  4953.4  347.93  4977.5  347.09
  4996.6  347.55  5003.7  346.43  5006.4  345.93  5009.7  346.43  5016.7   347.7
  5046.7   347.4  5056.7   346.8  5106.7   347.9  5146.8  347.65  5198.5  348.56
  5209.3  348.27  5236.9  349.16  5316.9  350.22    5357  349.78    5397   351.2
    5407  350.79    5447  351.55    5457  352.29    5497  352.98  5522.4  352.66
#Mann= 5 ,-1 , 0
  4726.1      .1       0  4953.4     .12       0  5003.7     .07       0
  5009.7     .12       0  5198.5      .1       0
Bank Sta=5003.7,5009.7
XS Rating Curve= 0 ,0
Exp/Cntr=0.3,0.1

Type RM Length L Ch R = 1 ,1677    ,138,138,138
BEGIN DESCRIPTION:
Mapping XS e110a220
END DESCRIPTION:
XS GIS Cut Line= 4
      2293883.45     13410010.09      2293867.88     13410479.21
      2293908.76     13410821.78      2293924.32     13410868.47
#Sta/Elev= 30
  4663.1  349.76  4739.9  349.16  4749.9  348.46  4759.9  348.73  4809.9  347.28
  4879.8  346.95    4920  347.47    4930  347.34    4950  346.83    4960  347.31
    4970  346.77    4980  347.12  5000.1  346.36  5050.1  346.57  5059.8  345.67
  5080.1  346.85  5100.1  346.66  5110.1  347.33  5120.1  347.24  5160.3  347.97
  5174.4  347.37  5240.9  347.92    5251  347.61  5291.2  348.78  5344.4  349.16
  5432.2   350.8  5477.5  350.99  5482.8  350.22  5489.1  350.77  5526.7  351.27
#Mann= 4 ,-1 , 0
  4663.1      .1       0  4879.8     .12       0    4930     .07       0
  5120.1      .1       0
Bank Sta=4920,5110.1
XS Rating Curve= 0 ,0
Exp/Cntr=0.3,0.1

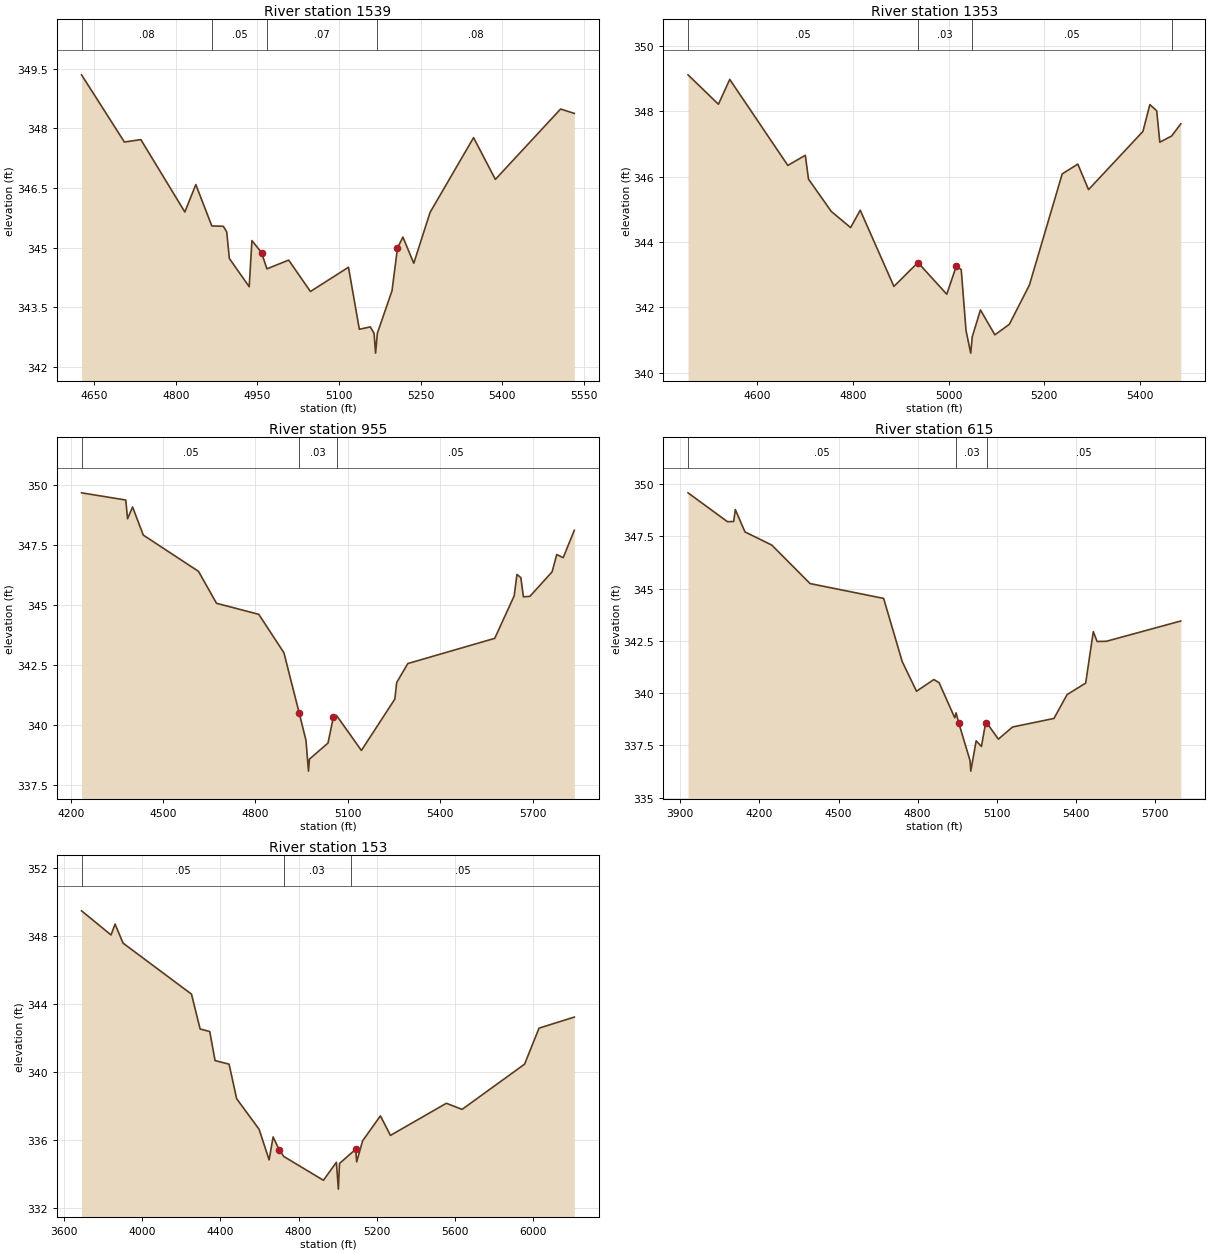
Type RM Length L Ch R = 1 ,1539    ,186,186,186
BEGIN DESCRIPTION:
Mapping XS 78350414
END DESCRIPTION:
XS GIS Cut Line= 3
      2293772.51     13409978.97      2293731.63     13410251.48
      2293751.09     13410882.02
#Sta/Elev= 30
  4626.4  349.35  4705.2  347.66  4735.5  347.72  4816.4   345.9  4836.6  346.59
    4866  345.55  4887.2  345.54  4893.4   345.4  4898.3  344.73  4934.8  344.02
  4939.8  345.18  4957.4  344.88  4967.4  344.47  5007.4  344.69  5047.4   343.9
  5117.4  344.51  5137.4  342.95  5157.5  343.01  5164.5  342.85  5167.2  342.35
  5170.5  342.85  5197.5  343.92  5207.5  344.99  5217.5  345.27  5237.5  344.61
  5267.5  345.89  5347.5  347.77  5387.6  346.72  5507.6  348.49  5532.8  348.38
#Mann= 4 ,-1 , 0
  4626.4     .08       0    4866     .05       0  4967.4     .07       0
  5170.5     .08       0
Bank Sta=4957.4,5207.5
XS Rating Curve= 0 ,0
Exp/Cntr=0.3,0.1

Type RM Length L Ch R = 1 ,1353    ,398,398,398
BEGIN DESCRIPTION:
Mapping XS 184c4e32
END DESCRIPTION:
XS GIS Cut Line= 4
      2293695.68     13409925.09       2293542.9     13410147.31
      2293591.51     13410682.03      2293730.38     13410855.62
#Sta/Elev= 30
  4456.1  349.11  4519.6  348.21  4543.2  348.97  4664.5  346.34    4701  346.65
  4707.7  345.92  4755.4  344.93  4795.6  344.44  4815.7  344.97    4886  342.64
  4936.2  343.37  4996.4   342.4  5016.5  343.27  5026.6  343.15  5036.6  341.29
  5046.4   340.6  5049.6   341.1  5066.7  341.92  5096.8  341.16    5127  341.48
  5168.9  342.68  5237.4  346.08    5270  346.38  5292.4   345.6    5406  347.38
  5420.4   348.2  5434.8  348.01  5441.2  347.05    5466  347.24    5485  347.61
#Mann= 4 ,-1 , 0
  4456.1     .05       0  4936.2     .03       0  5049.6     .05       0
    5466     .08       0
Bank Sta=4936.2,5016.5
XS Rating Curve= 0 ,0
Exp/Cntr=0.3,0.1

Type RM Length L Ch R = 1 ,955     ,340,340,340
BEGIN DESCRIPTION:
Mapping XS a90c75ae
END DESCRIPTION:
XS GIS Cut Line= 4
      2293724.75     13409831.84      2293224.71     13410097.49
      2293167.42     13410508.95      2293682.25     13410852.17
#Sta/Elev= 30
  4235.3  349.67    4379  349.37  4384.7  348.59    4401  349.08  4435.8  347.91
  4615.1   346.4  4673.6  345.07  4810.9  344.61  4892.6  343.01  4942.2   340.5
  4964.2  339.36  4972.3  338.08  4975.5  338.58  5035.8  339.25  5053.3  340.34
  5063.4   340.4  5144.2  338.94  5252.8  341.08  5258.8  341.77  5294.9  342.56
  5577.3  343.61  5640.4  345.38  5649.4  346.27    5662  346.14  5670.4  345.34
  5691.5  345.36  5763.6  346.38  5778.6   347.1  5799.6  346.97  5835.7  348.11
#Mann= 3 ,-1 , 0
  4235.3     .05       0  4942.2     .03       0  5063.4     .05       0
Bank Sta=4942.2,5053.3
XS Rating Curve= 0 ,0
Exp/Cntr=0.3,0.1

Type RM Length L Ch R = 1 ,615     ,462,462,462
BEGIN DESCRIPTION:
Mapping XS 9d270a07
END DESCRIPTION:
XS GIS Cut Line= 4
      2293689.09     13409736.32      2292852.31     13410062.71
      2292876.61     13410337.01        2293424.     13410766.61
#Sta/Elev= 30
  3929.1  349.58  4078.7   348.2  4102.3  348.21  4108.6  348.78  4145.2  347.71
  4247.1  347.08  4392.1  345.24  4671.2  344.53  4741.7  341.51    4796  340.09
  4861.6  340.65  4881.6   340.5  4941.1  338.82  4946.1  339.06 4955.97  338.59
  4999.1  336.77  5001.9  336.27  5022.2  337.72  5042.3  337.45    5058  338.57
    5063  338.57  5106.5   337.8  5160.2  338.38  5317.4  338.79  5367.2  339.93
  5437.7  340.48  5466.6  342.94  5481.1  342.47  5516.3  342.48  5798.5  343.45
#Mann= 3 ,-1 , 0
  3929.1     .05       0  4946.1     .03       0    5063     .05       0
Bank Sta=4955.97,5058
XS Rating Curve= 0 ,0
Exp/Cntr=0.3,0.1

Type RM Length L Ch R = 1 ,153     ,0,0,0
BEGIN DESCRIPTION:
UNT047 IN SUCR 2.0
END DESCRIPTION:
XS GIS Cut Line= 4
      2293675.26     13409673.81      2292501.61     13409927.29
      2292432.17     13410205.07      2293320.47     13410732.27
#Sta/Elev= 30
  3690.5  349.46  3841.4  348.04  3861.9  348.68  3902.8  347.56  4252.7  344.56
  4296.9  342.51  4346.1  342.36  4373.4  340.65    4445  340.44  4483.7  338.41
  4598.5  336.61  4649.7  334.81  4670.1  336.16  4700.8  335.41  4724.9  335.01
  4927.4  333.61  4993.8  334.67  5003.9  333.09  5009.8   334.6    5066  335.17
  5092.3  335.43  5097.4  334.69  5127.8  335.93  5218.9   337.4  5270.2  336.25
  5556.1  338.14  5636.6  337.78  5956.1  340.44  6030.2  342.56  6210.5  343.21
#Mann= 3 ,-1 , 0
  3690.5     .05       0  4724.9     .03       0    5066     .05       0
Bank Sta=4700.8,5092.3
XS Rating Curve= 0 ,0
Exp/Cntr=0.3,0.1

Chan Stop Cuts=-1
Use User Specified Reach Order=0
Composite Channel Slope=5