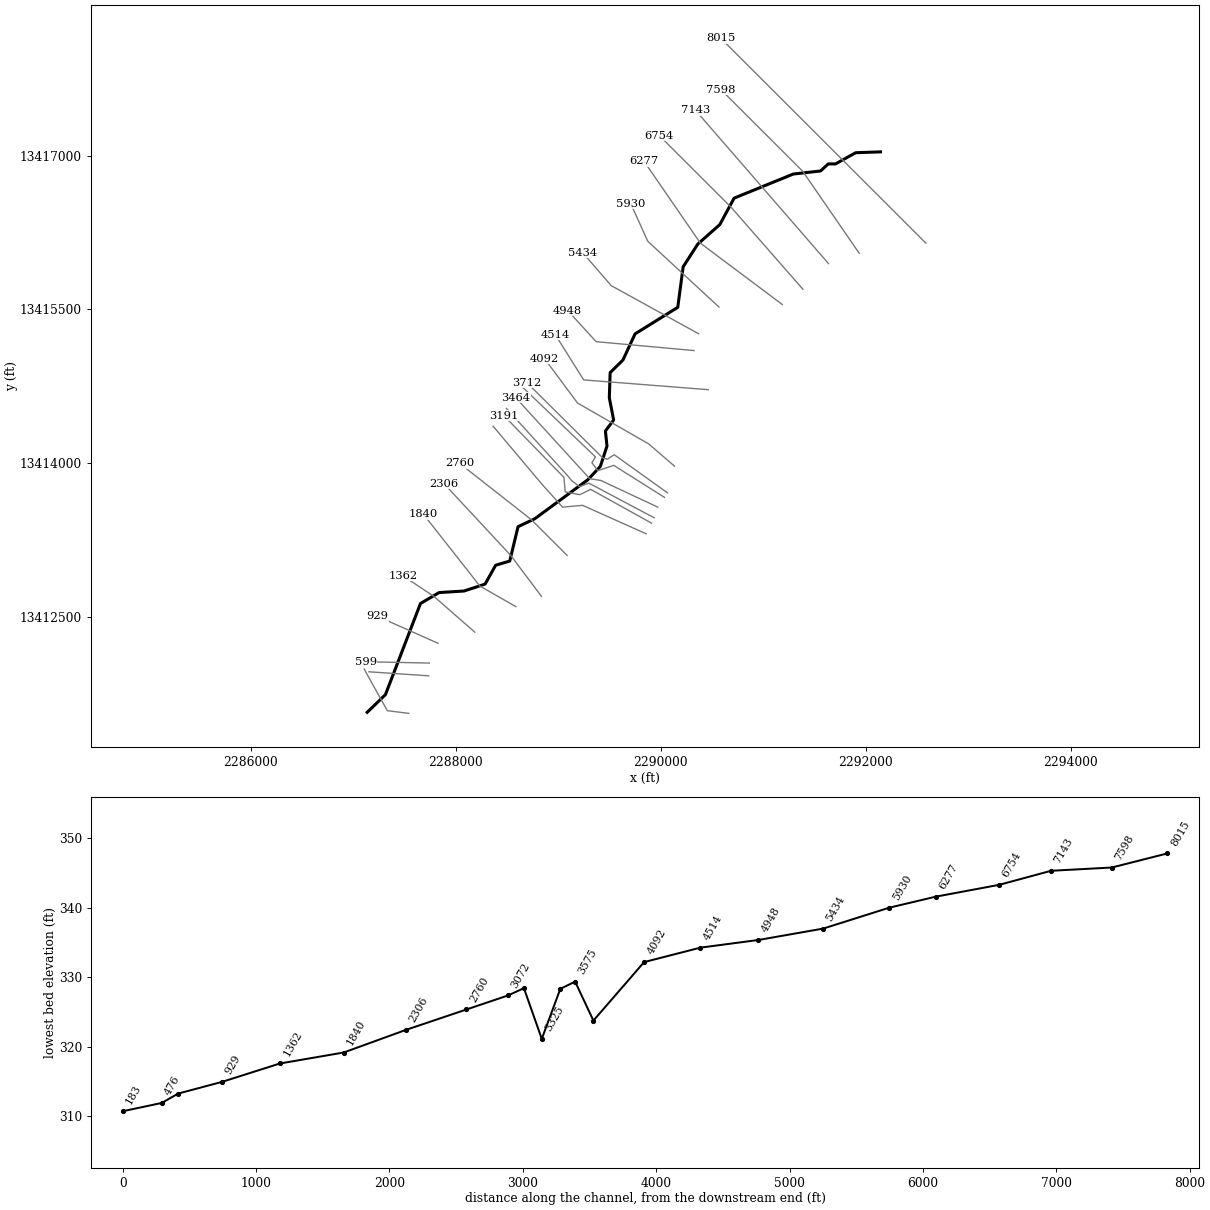
--- UNT048 IN SUCR.prj (project) ---

Proj Title=UNT048 IN SUCR Base Level Engineering
Current Plan=p01
Default Exp/Contr=0.3,0.1
English Units
Geom File=g01
Flow File=f01
Plan File=p01
Y Axis Title=Elevation
X Axis Title(PF)=Main Channel Distance
X Axis Title(XS)=Station
BEGIN DESCRIPTION:
UNT048 IN SUCR
END DESCRIPTION:
DSS Export Rating Curves= 0
DSS Export Rating Curve Sorted= 0
DSS Export Volume Flow Curves= 0
DXF OffsetX= 0
DXF OffsetY= 0
DXF ScaleX= 1
DXF ScaleY= 10

--- UNT048 IN SUCR.p01 (plan) ---

Plan Title=Multiple Run
Short Identifier=Multiple
Geom File=g01
Flow File=f01
Subcritical Flow
K Sum by GR= 0
Std Step Tol= 0.01
Critical Tol= 0.01
Num of Std Step Trials= 20
Max Error Tol= 0.3
Flow Tol Ratio= 0.001
Split Flow NTrial= 30
Split Flow Tol= 0.02
Split Flow Ratio= 0.02
Log Output Level= 0
Friction Slope Method= 1
Unsteady Friction Slope Method= 2
Unsteady Bridges Friction Slope Method= 1
Parabolic Critical Depth
Global Vel Dist=  1 , 1 , 1
Global Log Level= 0
CheckData=True
Encroach Param= -1, 0, 0, 0
BEGIN DESCRIPTION:
Multiple Run
END DESCRIPTION:

--- UNT048 IN SUCR.f01 (steady flow) ---

Flow Title=Multiple
Program Version=4.10
Number of Profiles= 7
Profile Names=10-year,25-year,50-year,1pct_min,100-year,1pct_plu,500-year
River Rch & RM=UNT048 IN SUCR,Reach-1         ,8015
     970    1415    1799    1671    2260    3056    3583
River Rch & RM=UNT048 IN SUCR,Reach-1         ,1840
     948    1382    1758    1633    2208    2986    3504
Boundary for River Rch & Prof#=UNT048 IN SUCR,Reach-1         , 1
Up Type= 0
Dn Type= 3
Dn Slope=0.006
Boundary for River Rch & Prof#=UNT048 IN SUCR,Reach-1         , 2
Up Type= 0
Dn Type= 3
Dn Slope=0.006
Boundary for River Rch & Prof#=UNT048 IN SUCR,Reach-1         , 3
Up Type= 0
Dn Type= 3
Dn Slope=0.006
Boundary for River Rch & Prof#=UNT048 IN SUCR,Reach-1         , 4
Up Type= 0
Dn Type= 3
Dn Slope=0.006
Boundary for River Rch & Prof#=UNT048 IN SUCR,Reach-1         , 5
Up Type= 0
Dn Type= 3
Dn Slope=0.006
Boundary for River Rch & Prof#=UNT048 IN SUCR,Reach-1         , 6
Up Type= 0
Dn Type= 3
Dn Slope=0.006
Boundary for River Rch & Prof#=UNT048 IN SUCR,Reach-1         , 7
Up Type= 0
Dn Type= 3
Dn Slope=0.006
DSS Import GetInterval= 0
DSS Import GetPeak= 0
DSS Import FillOption= 0

--- UNT048 IN SUCR.g01 (geometry) ---

Geom Title=Existing Conditions
Program Version=4.10

River Reach=UNT048 IN SUCR  ,Reach-1
Reach XY= 30
      2292145.14     13417038.04       2291903.1     13417029.81
      2291706.02     13416920.43      2291634.85     13416920.23
      2291560.71     13416851.43      2291294.56      13416821.6
      2290717.05     13416586.29      2290576.86     13416327.21
      2290363.21     13416138.24      2290219.94     13415915.61
      2290167.08     13415519.35       2289750.9     13415260.45
      2289632.07      13415004.2      2289507.65     13414881.97
      2289499.47     13414637.29      2289541.78      13414419.3
      2289461.48     13414311.88      2289476.87     13414164.84
      2289412.22     13413966.61      2289289.61     13413835.32
      2288772.03     13413454.46      2288609.27     13413377.42
      2288528.32     13413041.72      2288390.81     13413000.74
      2288287.78     13412816.55      2288082.31      13412748.9
      2287838.95     13412733.82       2287657.6     13412627.15
      2287315.94     13411737.59      2287137.72     13411564.28

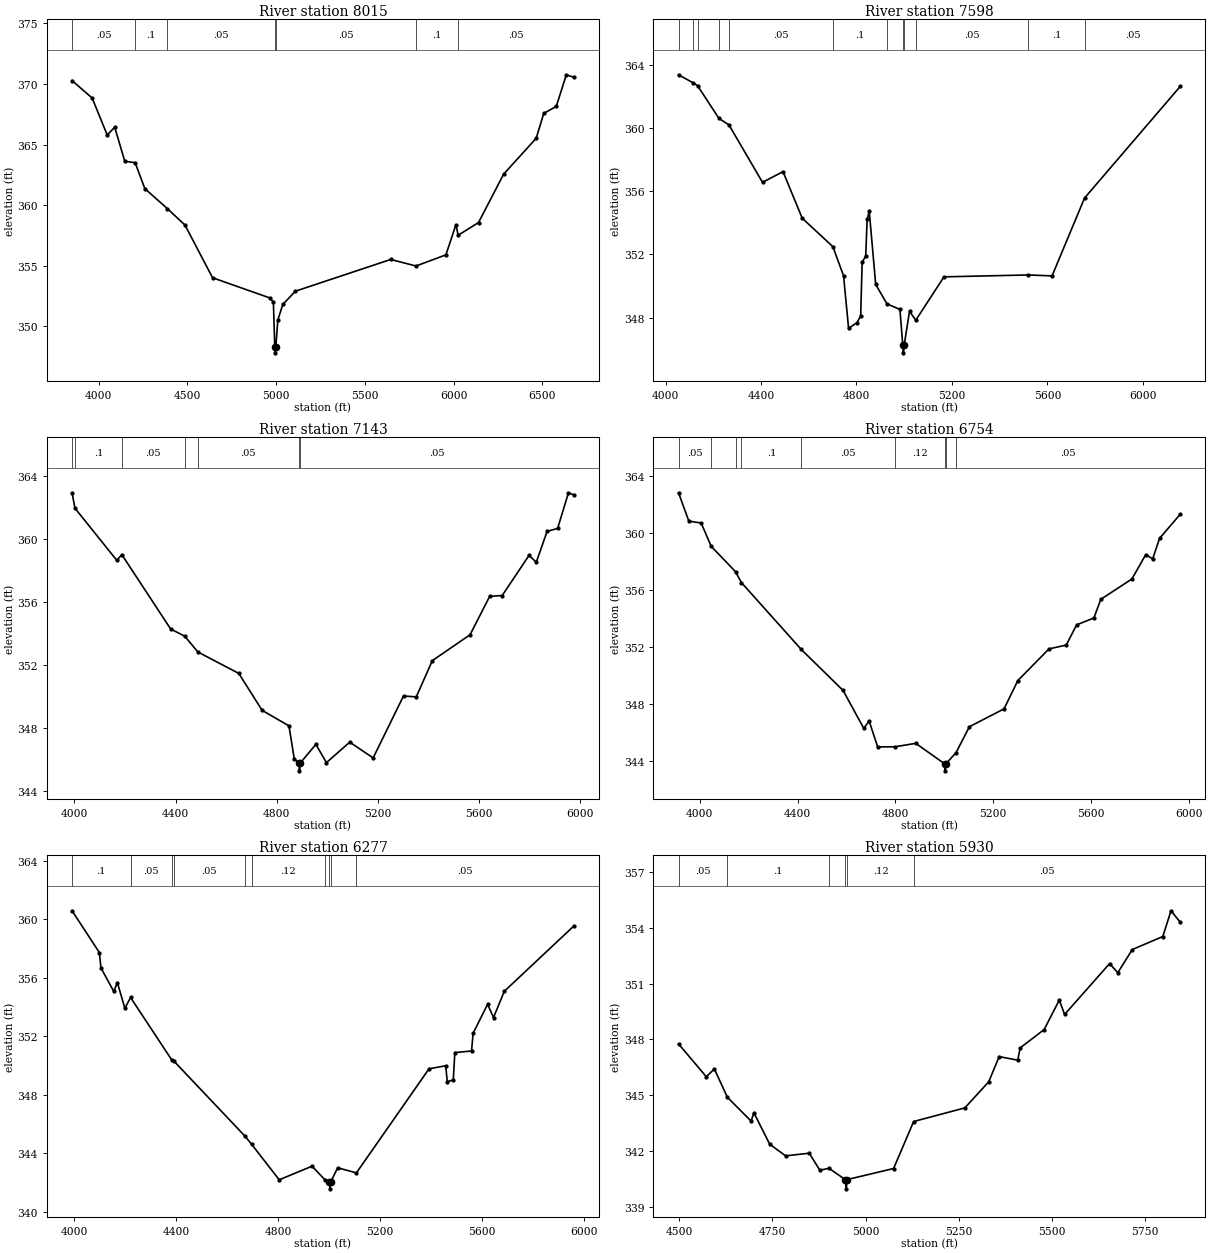
Type RM Length L Ch R = 1 ,8015    ,417,417,417
BEGIN DESCRIPTION:
UNT048 IN SUCR 18.0
END DESCRIPTION:
XS GIS Cut Line= 3
      2292587.74     13416146.84      2291787.72     13416946.85
      2290587.69     13418146.89
#Sta/Elev= 30
  3849.5  370.28  3962.7  368.84  4047.5  365.79  4089.9  366.43  4146.5  363.62
  4205.1   363.5  4259.6  361.36  4386.6  359.71  4485.9  358.35  4641.5     354
  4966.8  352.32  4984.4  351.96    4992   348.3  4994.8   347.8    4998   348.3
  5009.2   350.5  5037.5   351.8  5108.2  352.89  5645.6  355.51  5788.1  354.97
  5956.7  355.89  6013.3  358.38  6025.9  357.51  6140.6  358.56    6282  362.55
  6465.8  365.52  6508.2  367.57    6579  368.15  6635.5  370.76    6678  370.55
#Mann= 7 ,-1 , 0
  3849.5     .05       0  4205.1      .1       0  4386.6     .05       0
    4992     .03       0    4998     .05       0  5788.1      .1       0
  6025.9     .05       0
Bank Sta=4992,4998
XS Rating Curve= 0 ,0
Exp/Cntr=0.3,0.1

Type RM Length L Ch R = 1 ,7598    ,455,455,455
BEGIN DESCRIPTION:
UNT048 IN SUCR 17.0
END DESCRIPTION:
XS GIS Cut Line= 3
       2291937.7     13416046.88      2291387.72     13416846.85
       2290587.7     13417646.88
#Sta/Elev= 30
  4054.5  363.37  4113.2  362.88  4134.2  362.68  4223.7  360.61  4265.6   360.2
  4406.4  356.56  4492.2  357.24  4572.7  354.29  4701.2  352.49  4745.9  350.64
  4766.9  347.32  4802.7  347.69  4817.6  348.12  4823.7   351.5  4838.6  351.89
  4844.6  354.21  4853.5  354.73  4880.5   350.1  4927.7  348.87    4982  348.52
  4993.9  346.27  4996.6  345.77  4999.9  346.27  5022.3  348.41  5048.1  347.83
  5166.7  350.58  5520.2   350.7  5619.3  350.64  5755.5  355.57  6156.7  362.64
#Mann= 12 ,-1 , 0
  4054.5     .05       0  4113.2      .1       0  4134.2     .05       0
  4223.7      .1       0  4265.6     .05       0  4701.2      .1       0
  4927.7     .12       0  4993.9     .07       0  4999.9     .12       0
  5048.1     .05       0  5520.2      .1       0  5755.5     .05       0
Bank Sta=4993.9,4999.9
XS Rating Curve= 0 ,0
Exp/Cntr=0.3,0.1

Type RM Length L Ch R = 1 ,7143    ,389,389,389
BEGIN DESCRIPTION:
UNT048 IN SUCR 16.0
END DESCRIPTION:
XS GIS Cut Line= 3
      2291637.74     13415946.84      2290987.72     13416696.85
       2290337.7     13417446.88
#Sta/Elev= 30
  3990.5  362.93    4002  361.96  4167.6  358.65  4187.2  359.02  4380.4   354.3
  4436.3  353.84  4488.2  352.84  4650.1  351.48  4742.3  349.14  4848.6  348.15
  4869.5  346.05  4887.4   345.8  4890.1   345.3  4893.4   345.8    4955  346.98
  4996.7  345.82  5088.9  347.12  5181.5  346.12  5301.6  350.05    5352  349.99
  5415.6  352.29  5564.7  353.93  5642.6  356.37    5692  356.42  5798.3  358.97
  5826.8  358.53  5869.6  360.49  5911.3  360.68  5954.1  362.94  5975.5  362.81
#Mann= 7 ,-1 , 0
  3990.5     .05       0    4002      .1       0  4187.2     .05       0
  4436.3      .1       0  4488.2     .05       0  4887.4     .04       0
  4893.4     .05       0
Bank Sta=4887.4,4893.4
XS Rating Curve= 0 ,0
Exp/Cntr=0.3,0.1

Type RM Length L Ch R = 1 ,6754    ,477,477,477
BEGIN DESCRIPTION:
UNT048 IN SUCR 15.0
END DESCRIPTION:
XS GIS Cut Line= 3
      2291387.71     13415696.86      2290687.72     13416496.85
      2289987.69     13417196.89
#Sta/Elev= 30
  3913.2   362.8  3955.4  360.81  4005.7  360.68  4046.9  359.04  4146.3  357.26
  4170.3   356.5  4415.4   351.8  4586.6  348.92  4671.1  346.26  4692.9  346.78
    4728  344.96  4799.3  344.97  4883.7  345.21  5001.5  343.78  5004.2  343.28
  5007.5  343.78  5048.3  344.55  5103.5  346.38  5244.9  347.63  5301.5  349.62
  5428.8  351.84  5499.5  352.11  5541.9  353.53  5612.6  354.01  5640.9  355.32
  5768.2  356.75  5824.7  358.46    5853  358.16  5881.3   359.6  5966.2   361.3
#Mann= 9 ,-1 , 0
  3913.2     .05       0  4046.9      .1       0  4146.3     .05       0
  4170.3      .1       0  4415.4     .05       0  4799.3     .12       0
  5001.5     .07       0  5007.5     .12       0  5048.3     .05       0
Bank Sta=5001.5,5007.5
XS Rating Curve= 0 ,0
Exp/Cntr=0.3,0.1

Type RM Length L Ch R = 1 ,6277    ,347,347,347
BEGIN DESCRIPTION:
UNT048 IN SUCR 14.0
END DESCRIPTION:
XS GIS Cut Line= 3
      2291187.73     13415546.85      2290387.72     13416146.85
      2289837.74     13416946.83
#Sta/Elev= 30
  3990.6  360.59  4097.9  357.73  4104.1  356.68  4154.1  355.08  4168.7  355.67
  4197.9  353.92  4220.3  354.66  4383.1  350.36  4389.4  350.33  4668.3   345.2
  4695.7  344.62  4804.1  342.19  4933.3  343.12  4984.7  342.17  5001.1  342.07
  5003.9  341.57  5007.1  342.07  5033.9  343.01  5107.3  342.66  5392.5  349.78
  5458.1  349.99  5464.2   348.9  5487.9  349.02  5493.9  350.89  5559.6     351
  5565.7  352.21  5622.5  354.19  5645.9  353.29  5688.1  355.08  5961.4  359.55
#Mann= 10 ,-1 , 0
  3990.6      .1       0  4220.3     .05       0  4383.1      .1       0
  4389.4     .05       0  4668.3      .1       0  4695.7     .12       0
  4984.7      .1       0  5001.1     .07       0  5007.1      .1       0
  5107.3     .05       0
Bank Sta=5001.1,5007.1
XS Rating Curve= 0 ,0
Exp/Cntr=0.3,0.1

Type RM Length L Ch R = 1 ,5930    ,496,496,496
BEGIN DESCRIPTION:
UNT048 IN SUCR 13.0
END DESCRIPTION:
XS GIS Cut Line= 3
      2290569.11     13415522.75      2289874.66     13416165.12
      2289709.75     13416529.66
#Sta/Elev= 30
  4498.2  347.76  4572.8     346  4594.3  346.42  4629.2   344.9    4693  343.62
  4700.3  344.07  4742.9  342.38  4785.4  341.76  4848.9   341.9  4877.2  340.99
    4902  341.09  4945.1  340.49  4947.9  339.99  4951.1  340.49  5075.1  341.08
  5128.9   343.6  5266.2  344.33  5330.3  345.73  5358.3  347.08    5408  346.89
  5414.8  347.55    5479  348.53  5519.6  350.11  5533.9  349.34  5654.6  352.07
  5676.6  351.58  5715.4  352.82  5797.3  353.52  5819.3   354.9  5844.3  354.28
#Mann= 6 ,-1 , 0
  4498.2     .05       0  4629.2      .1       0    4902     .12       0
  4945.1     .07       0  4951.1     .12       0  5128.9     .05       0
Bank Sta=4945.1,4951.1
XS Rating Curve= 0 ,0
Exp/Cntr=0.3,0.1

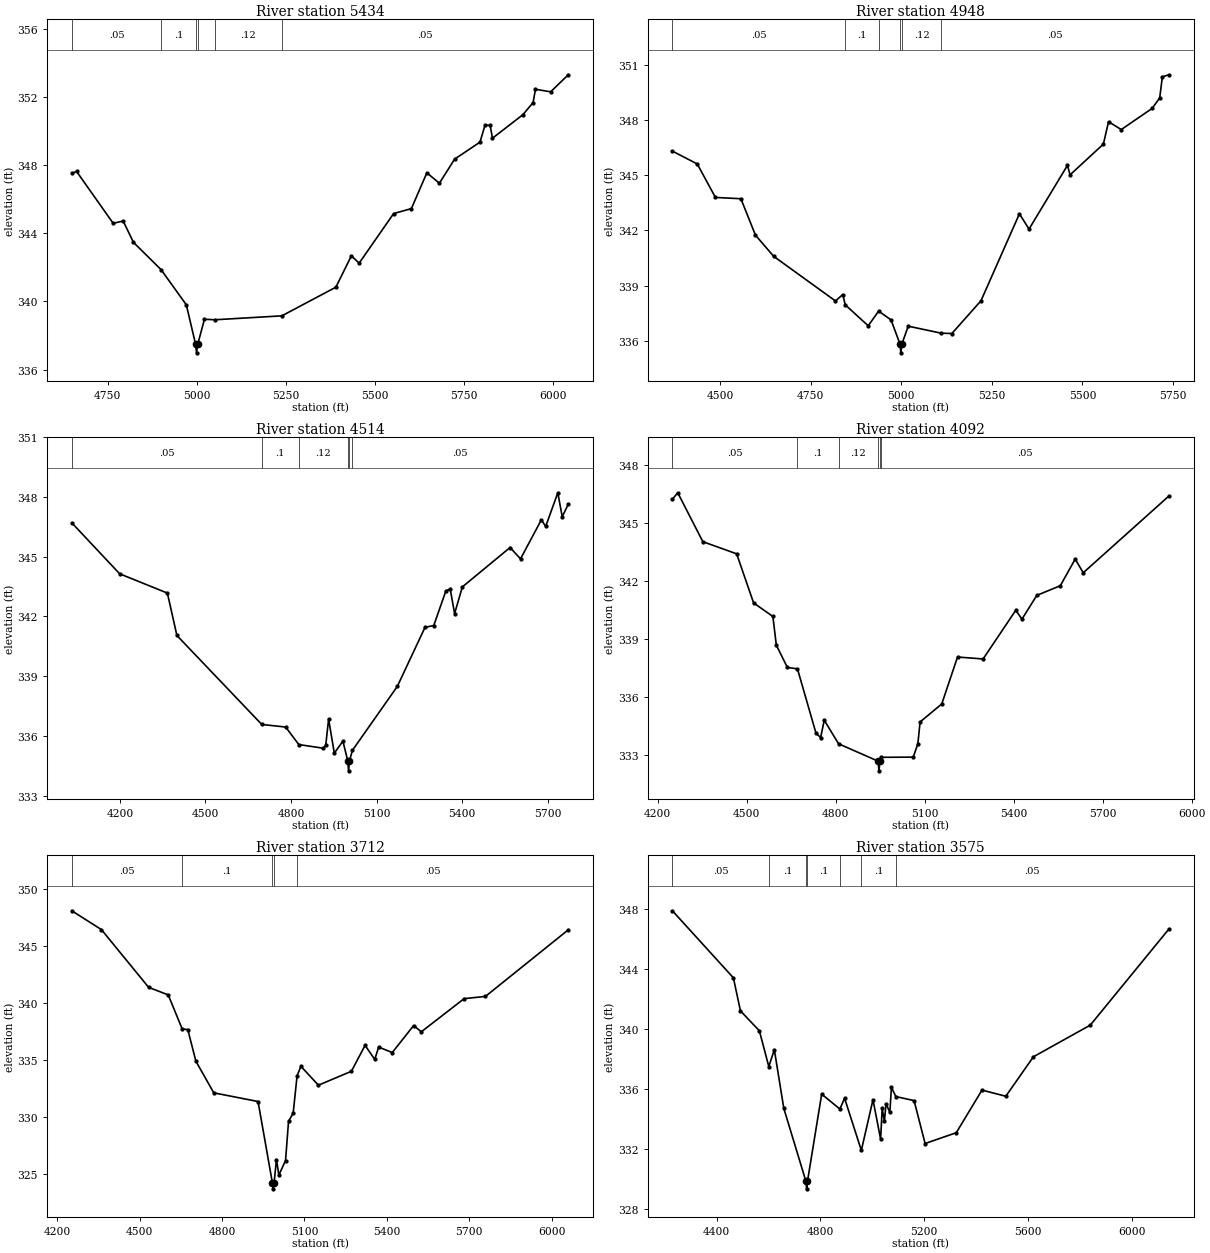
Type RM Length L Ch R = 1 ,5434    ,486,486,486
BEGIN DESCRIPTION:
UNT048 IN SUCR 12.0
END DESCRIPTION:
XS GIS Cut Line= 3
      2290369.43     13415262.36      2289518.76      13415731.1
      2289242.03     13416051.06
#Sta/Elev= 30
  4649.3  347.51  4662.7  347.62  4765.4  344.58  4793.6  344.71  4822.5  343.46
    4900  341.86  4970.9   339.8    4997  337.48  4999.7  336.98    5003  337.48
  5021.8  338.95  5051.3  338.92  5239.3  339.15  5390.9  340.83  5434.5  342.67
  5456.3  342.24  5553.2  345.15    5603  345.44  5646.5  347.54  5681.7  346.93
  5724.4  348.34  5795.7  349.34  5809.9  350.34  5824.2  350.32  5830.8  349.57
  5916.3  350.95  5944.8  351.66  5951.5  352.44  5994.2  352.29  6043.6  353.29
#Mann= 6 ,-1 , 0
  4649.3     .05       0    4900      .1       0    4997     .07       0
    5003      .1       0  5051.3     .12       0  5239.3     .05       0
Bank Sta=4997,5003
XS Rating Curve= 0 ,0
Exp/Cntr=0.3,0.1

Type RM Length L Ch R = 1 ,4948    ,434,434,434
BEGIN DESCRIPTION:
UNT048 IN SUCR 11.0
END DESCRIPTION:
XS GIS Cut Line= 3
      2290326.07     13415097.41      2289371.19     13415184.22
       2289093.4     13415488.05
#Sta/Elev= 30
  4368.2  346.31  4436.8  345.61    4487  343.79  4557.3  343.72  4597.5  341.74
  4647.7  340.59  4818.4  338.16  4838.5  338.51  4845.4  337.95  4908.8  336.81
  4937.5  337.61  4971.8  337.13  4996.1  335.84  4998.9  335.34  5002.1  335.84
  5019.2  336.79    5110  336.41  5139.7  336.39    5220  338.17  5326.2   342.9
  5352.7  342.07  5458.7  345.53  5466.1  345.02    5558  346.69  5572.2  347.91
  5607.3  347.48  5692.4  348.63  5713.4   349.2  5720.8  350.35  5738.7  350.46
#Mann= 6 ,-1 , 0
  4368.2     .05       0  4845.4      .1       0  4937.5     .12       0
  4996.1     .07       0  5002.1     .12       0    5110     .05       0
Bank Sta=4996.1,5002.1
XS Rating Curve= 0 ,0
Exp/Cntr=0.3,0.1

Type RM Length L Ch R = 1 ,4514    ,422,422,422
BEGIN DESCRIPTION:
UNT048 IN SUCR 10.0
END DESCRIPTION:
XS GIS Cut Line= 3
       2290464.9     13414715.47      2289249.66     13414810.96
      2288972.85     13415252.12
#Sta/Elev= 30
  4031.7   346.7  4199.4  344.14  4366.7  343.17    4400  341.04  4697.4  336.57
  4781.2  336.44  4827.2  335.56  4911.6  335.38  4921.6  335.52  4931.6  336.84
  4951.7  335.13  4981.8  335.73  4998.8  334.74  5001.6  334.24  5004.8  334.74
  5015.1  335.27  5172.4  338.48  5269.5  341.45  5300.2  341.54  5342.6  343.28
  5357.9  343.37  5373.2  342.14  5400.3  343.48  5567.6  345.46  5604.2  344.89
  5677.2  346.85  5692.5  346.52  5734.9  348.21  5750.3  347.01  5771.5  347.63
#Mann= 6 ,-1 , 0
  4031.7     .05       0  4697.4      .1       0  4827.2     .12       0
  4998.8     .07       0  5004.8     .12       0  5015.1     .05       0
Bank Sta=4998.8,5004.8
XS Rating Curve= 0 ,0
Exp/Cntr=0.3,0.1

Type RM Length L Ch R = 1 ,4092    ,380,380,380
BEGIN DESCRIPTION:
UNT048 IN SUCR 9.0
END DESCRIPTION:
XS GIS Cut Line= 4
      2290135.09     13413968.93      2289883.34     13414185.96
      2289188.89     13414585.26       2288867.7      13415019.3
#Sta/Elev= 30
  4249.7  346.22  4267.8  346.55  4352.3  344.02  4466.3  343.39  4523.4  340.85
  4588.4  340.15  4600.1  338.66  4637.3  337.51  4671.2  337.44  4733.5  334.12
  4749.3  333.88  4761.6  334.78  4809.8  333.56  4943.2  332.66  4945.9  332.16
  4949.2  332.66  4954.3  332.86  5061.5  332.87  5077.1  333.56  5084.6  334.69
  5157.6  335.62  5210.8  338.05    5297  337.95  5407.1  340.47  5427.9  340.01
    5478  341.24  5557.3  341.74  5607.4  343.12  5634.5  342.41  5923.1  346.38
#Mann= 6 ,-1 , 0
  4249.7     .05       0  4671.2      .1       0  4809.8     .12       0
  4943.2    .035       0  4949.2     .12       0  4954.3     .05       0
Bank Sta=4943.2,4949.2
XS Rating Curve= 0 ,0
Exp/Cntr=0.3,0.1

Type RM Length L Ch R = 1 ,3712    ,137,137,137
BEGIN DESCRIPTION:
Mapping XS ec711eaa
END DESCRIPTION:
XS GIS Cut Line= 6
      2290067.84     13413707.18      2289547.05     13414080.42
      2289481.94     13414037.02      2289442.88      13414045.7
      2289416.84      13414067.4      2288697.23     13414782.67
#Sta/Elev= 30
  4253.1   348.1    4361  346.45  4532.9  341.39  4604.2  340.73  4654.9  337.75
  4675.4  337.69  4704.9  334.92    4770  332.15  4931.2  331.39  4983.6  324.24
  4986.4  323.74  4989.6  324.24  4998.2  326.31    5007  324.95  5031.3  326.22
  5042.2  329.66  5059.1  330.37  5073.4  333.66  5087.4  334.47    5151  332.82
  5271.2  334.04  5320.8  336.31  5356.1  335.08  5370.2  336.16  5419.8  335.68
  5497.5  338.04  5525.8   337.5  5681.4   340.4  5759.2   340.6  6060.6  346.43
#Mann= 5 ,-1 , 0
  4253.1     .05       0  4654.9      .1       0  4983.6     .07       0
  4989.6      .1       0  5073.4     .05       0
Bank Sta=4983.6,4989.6
XS Rating Curve= 0 ,0
Exp/Cntr=0.3,0.1

Type RM Length L Ch R = 1 ,3575    ,111,111,111
BEGIN DESCRIPTION:
UNT048 IN SUCR 8.0
END DESCRIPTION:
XS GIS Cut Line= 6
      2290037.49     13413663.76      2289542.71     13413976.25
      2289386.46     13413924.17      2289330.03     13414002.29
      2289364.76     13414058.72      2288652.98     13414740.12
#Sta/Elev= 30
  4229.8  347.88  4464.9  343.41    4492  341.21    4565  339.88  4601.2   337.5
  4622.6  338.62  4659.1  334.71  4744.3  329.85  4747.1  329.35  4750.3  329.85
    4805  335.66    4875  334.67  4893.4  335.38  4957.8  331.91  5002.7  335.29
  5032.1  332.66  5038.2  334.71  5046.8  333.84  5052.9  335.03  5067.6  334.45
  5073.8  336.12  5090.6   335.5    5161  335.23  5203.5  332.37  5323.6  333.09
  5422.7  335.93  5514.5  335.52  5620.8  338.15    5840  340.26  6142.7  346.66
#Mann= 7 ,-1 , 0
  4229.8     .05       0  4601.2      .1       0  4744.3     .07       0
  4750.3      .1       0    4875     .05       0  4957.8      .1       0
  5090.6     .05       0
Bank Sta=4744.3,4750.3
XS Rating Curve= 0 ,0
Exp/Cntr=0.3,0.1

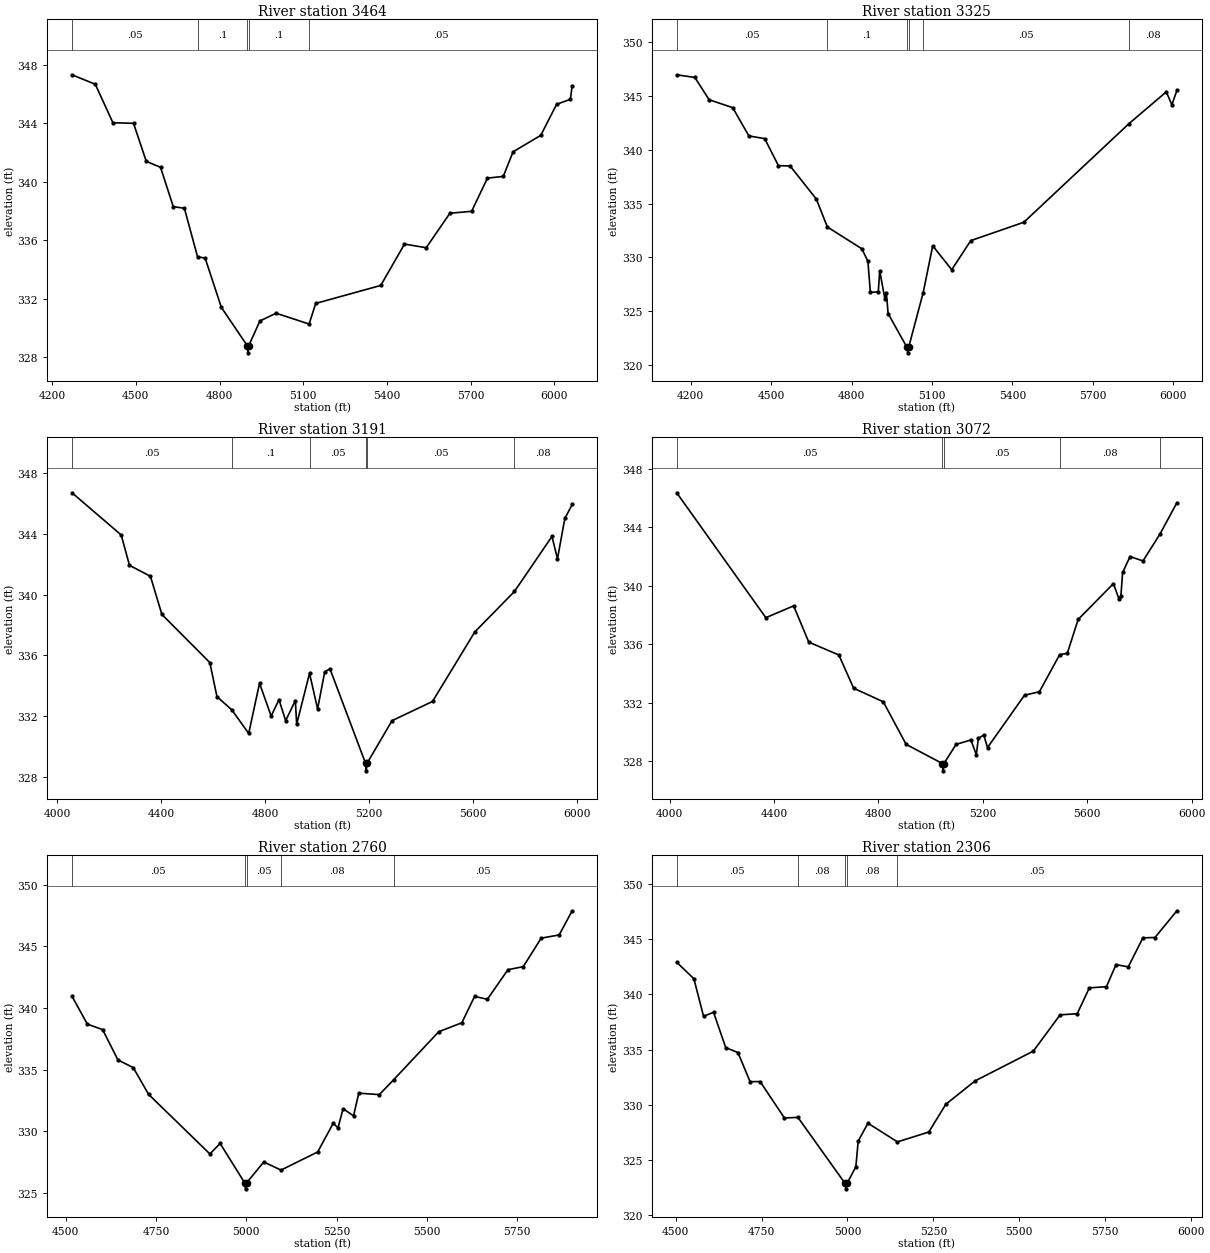
Type RM Length L Ch R = 1 ,3464    ,139,139,139
BEGIN DESCRIPTION:
Mapping XS fc85ecb5
END DESCRIPTION:
XS GIS Cut Line= 4
      2289972.44     13413568.25      2289416.84     13413828.68
      2289308.33     13413846.04      2288587.81     13414636.01
#Sta/Elev= 30
  4271.1  347.33  4354.7  346.68  4417.7  344.05  4491.7  344.01  4537.3  341.41
  4588.5     341  4634.1  338.31  4673.9   338.2  4721.1  334.88  4748.3  334.79
  4806.4  331.42  4898.9  328.81  4901.6  328.31  4904.9  328.81  4944.6  330.49
  5002.7  331.02  5120.9  330.28  5144.6  331.69  5377.7  332.92  5462.8  335.75
  5540.5   335.5  5625.6  337.86  5703.3  337.99  5760.1  340.26  5816.8  340.38
    5852  342.06  5951.3  343.19    6008  345.31  6057.3  345.65  6063.8  346.58
#Mann= 5 ,-1 , 0
  4271.1     .05       0  4721.1      .1       0  4898.9     .07       0
  4904.9      .1       0  5120.9     .05       0
Bank Sta=4898.9,4904.9
XS Rating Curve= 0 ,0
Exp/Cntr=0.3,0.1

Type RM Length L Ch R = 1 ,3325    ,134,134,134
BEGIN DESCRIPTION:
Mapping XS e838483e
END DESCRIPTION:
XS GIS Cut Line= 6
      2289937.63     13413464.12      2289299.65     13413802.64
      2289208.51     13413767.92      2289130.38     13413828.68
      2289095.66     13413872.09      2288496.68     13414531.83
#Sta/Elev= 30
  4147.9  346.98  4215.7  346.73  4268.9  344.66  4356.8  343.92  4417.1  341.29
  4476.1  341.04  4527.1  338.53    4571  338.49  4668.5  335.42  4709.8  332.82
  4838.4  330.79    4861  329.63  4870.1  326.73  4899.7  326.79    4905  328.74
  4924.4  326.12  4929.8  326.66  4936.4  324.76  5006.8  321.61  5009.6  321.11
  5012.8  321.61  5067.2  326.72  5102.7  331.07  5173.6  328.84  5244.5  331.55
  5442.5  333.26  5834.4  342.43  5973.7  345.39  5994.6  344.19  6013.3  345.52
#Mann= 6 ,-1 , 0
  4147.9     .05       0  4709.8      .1       0  5006.8     .07       0
  5012.8      .1       0  5067.2     .05       0  5834.4     .08       0
Bank Sta=5006.8,5012.8
XS Rating Curve= 0 ,0
Exp/Cntr=0.3,0.1

Type RM Length L Ch R = 1 ,3191    ,119,119,119
BEGIN DESCRIPTION:
UNT048 IN SUCR 7.0
END DESCRIPTION:
XS GIS Cut Line= 6
      2289911.61     13413412.03      2289317.01     13413741.88
      2289212.85     13413689.79      2289069.34     13413717.05
       2289056.6     13413859.07       2288471.9     13414461.08
#Sta/Elev= 30
  4057.5  346.69  4246.7  343.92  4278.7  341.92  4359.3   341.2  4403.4  338.69
  4587.7  335.53  4615.2  333.29  4672.3  332.42  4737.4  330.87    4779  334.17
  4823.7  332.01  4853.9  333.09  4879.5  331.71  4916.9  333.03  4921.9  331.47
  4971.4  334.82  5002.4  332.48  5029.9  334.92  5049.9  335.12  5186.8  328.91
  5189.6  328.41  5192.8  328.91  5288.9  331.71  5444.5  332.97  5607.1  337.54
  5759.7   340.2  5904.1  343.82  5925.3  342.35  5953.6     345  5981.9  345.92
#Mann= 6 ,-1 , 0
  4057.5     .05       0  4672.3      .1       0  4971.4     .05       0
  5186.8    .035       0  5192.8     .05       0  5759.7     .08       0
Bank Sta=5186.8,5192.8
XS Rating Curve= 0 ,0
Exp/Cntr=0.3,0.1

Type RM Length L Ch R = 1 ,3072    ,312,312,312
BEGIN DESCRIPTION:
Mapping XS fe2341cc
END DESCRIPTION:
XS GIS Cut Line= 5
      2289859.55     13413307.85      2289238.89     13413585.63
      2289043.57     13413568.27      2288848.26     13413785.28
      2288366.49      13414358.2
#Sta/Elev= 30
  4026.9  346.37  4368.5  337.83    4475  338.64  4532.9  336.16  4648.3  335.28
  4704.8  333.01  4818.5  332.08    4906  329.17    5045  327.86  5047.8  327.36
    5051  327.86  5097.4  329.17  5154.2  329.47  5175.1  328.46  5182.6  329.58
  5203.5  329.81  5217.8  328.95  5359.6  332.53  5416.8  332.77  5494.5  335.31
  5523.5  335.39  5565.1  337.71  5700.4  340.16  5721.2  339.12    5729  339.34
  5735.5  340.92  5764.1  342.01  5813.6  341.71  5878.7  343.55  5943.5  345.69
#Mann= 5 ,-1 , 0
  4026.9     .05       0    5045    .035       0    5051     .05       0
  5494.5     .08       0  5878.7     .05       0
Bank Sta=5045,5051
XS Rating Curve= 0 ,0
Exp/Cntr=0.3,0.1

Type RM Length L Ch R = 1 ,2760    ,454,454,454
BEGIN DESCRIPTION:
UNT048 IN SUCR 6.0
END DESCRIPTION:
XS GIS Cut Line= 3
      2289087.74     13413096.83      2288737.72     13413446.85
      2288037.74     13413996.84
#Sta/Elev= 30
  4517.1  340.96  4559.6   338.7    4602  338.25  4644.4  335.79  4686.8  335.17
  4729.3     333    4899  328.17  4927.3  329.02    4995  325.84  4997.7  325.34
    5001  325.84  5048.2  327.52    5096  326.86  5197.4  328.33  5240.7  330.66
  5253.7  330.28  5267.9  331.84  5296.8  331.26  5311.3   333.1  5368.2  332.98
    5408  334.19  5532.7  338.08  5596.8  338.81  5632.1  340.95  5667.3  340.71
  5724.3  343.11  5766.8  343.36  5816.5  345.67  5866.2  345.93  5902.3  347.89
#Mann= 5 ,-1 , 0
  4517.1     .05       0    4995    .035       0    5001     .05       0
    5096     .08       0    5408     .05       0
Bank Sta=4995,5001
XS Rating Curve= 0 ,0
Exp/Cntr=0.3,0.1

Type RM Length L Ch R = 1 ,2306    ,466,466,466
BEGIN DESCRIPTION:
UNT048 IN SUCR 5.0
END DESCRIPTION:
XS GIS Cut Line= 3
      2288837.69     13412696.89      2288537.72     13413096.85
      2287887.72     13413796.85
#Sta/Elev= 30
  4503.2  342.91  4553.2  341.42  4581.3  338.02  4610.4  338.38  4645.9  335.18
  4681.3  334.74  4716.7   332.1  4745.9  332.11  4816.7  328.81  4855.8  328.87
  4992.9   322.9  4995.6   322.4  4998.9   322.9  5024.4   324.4  5031.2  326.72
  5059.6  328.34  5145.4  326.65  5236.5  327.54  5286.3  330.06  5371.3  332.17
  5540.9  334.87  5618.6  338.15  5668.4  338.25  5703.6  340.59  5753.4   340.7
  5781.3   342.7  5816.9  342.49  5859.5  345.12  5894.6  345.15  5958.4  347.57
#Mann= 5 ,-1 , 0
  4503.2     .05       0  4855.8     .08       0  4992.9     .07       0
  4998.9     .08       0  5145.4     .05       0
Bank Sta=4992.9,4998.9
XS Rating Curve= 0 ,0
Exp/Cntr=0.3,0.1

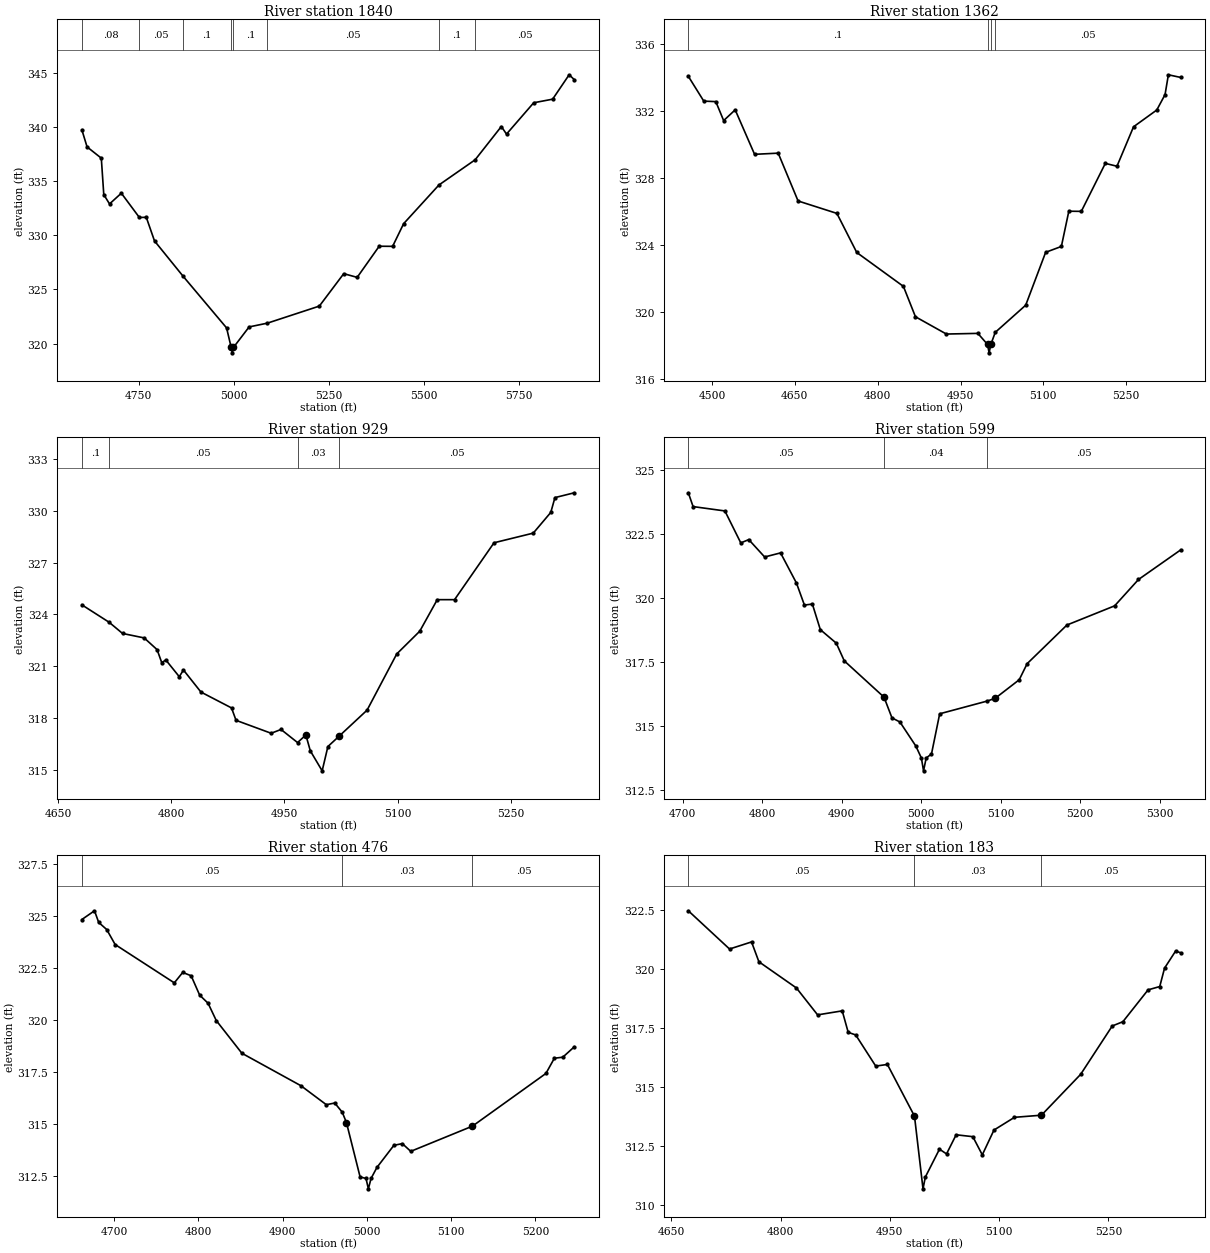
Type RM Length L Ch R = 1 ,1840    ,478,478,478
BEGIN DESCRIPTION:
UNT048 IN SUCR 4.0
END DESCRIPTION:
XS GIS Cut Line= 3
      2288587.75     13412596.84      2288237.72     13412796.85
       2287687.7     13413496.88
#Sta/Elev= 30
  4601.1  339.72  4614.8  338.14  4652.2   337.1  4658.7  333.74  4673.8  332.88
  4704.8  333.87  4752.2  331.63  4770.3  331.65  4791.9  329.47  4867.3   326.2
  4981.2  321.45  4993.3  319.65  4996.1  319.15  4999.3  319.65  5040.4  321.54
  5088.6  321.89  5224.8  323.46  5288.9  326.45  5324.2  326.11    5382  328.98
  5417.3  328.97  5446.2  331.06    5539  334.63    5634  336.95  5702.8  340.02
  5716.4  339.32  5787.8  342.21  5837.5  342.54  5880.9  344.79  5894.5  344.34
#Mann= 8 ,-1 , 0
  4601.1     .08       0  4752.2     .05       0  4867.3      .1       0
  4993.3     .07       0  4999.3      .1       0  5088.6     .05       0
    5539      .1       0    5634     .05       0
Bank Sta=4993.3,4999.3
XS Rating Curve= 0 ,0
Exp/Cntr=0.3,0.1

Type RM Length L Ch R = 1 ,1362    ,433,433,433
BEGIN DESCRIPTION:
UNT048 IN SUCR 3.0
END DESCRIPTION:
XS GIS Cut Line= 3
       2288187.7     13412346.87      2287787.72     13412696.85
      2287487.75     13412896.83
#Sta/Elev= 30
    4457  334.05    4485  332.57  4506.8  332.54    4521  331.41  4541.9  332.05
    4577   329.4  4619.8  329.47  4655.8  326.62  4726.1  325.88  4762.1  323.55
  4846.6  321.53  4868.4  319.72  4924.4  318.69  4981.4  318.73    4999  318.07
  5001.8  317.57    5005  318.07  5012.9  318.79  5068.1  320.41  5104.2  323.56
  5132.7  323.91  5146.2  326.01  5168.8     326  5212.3  328.86  5233.4  328.69
  5263.4  331.04  5305.5  332.04  5320.5  332.96  5326.5  334.14    5349  333.98
#Mann= 4 ,-1 , 0
    4457      .1       0    4999     .07       0    5005      .1       0
  5012.9     .05       0
Bank Sta=4999,5005
XS Rating Curve= 0 ,0
Exp/Cntr=0.3,0.1

Type RM Length L Ch R = 1 ,929     ,330,330,330
BEGIN DESCRIPTION:
Mapping XS 6c8c8cdc
END DESCRIPTION:
XS GIS Cut Line= 2
      2287828.85     13412238.57      2287232.72     13412503.88
#Sta/Elev= 30
  4681.7  324.56  4717.8  323.55  4735.6   322.9  4764.3  322.64  4781.4  321.96
  4787.5  321.21    4793  321.36  4810.8  320.39  4816.3  320.78  4839.5   319.5
    4880  318.58    4886  317.86  4932.5  317.11  4945.6  317.33  4967.5  316.57
  4978.5  317.01  4984.4  316.09  5000.1  314.93  5007.7  316.34  5022.3  316.93
  5059.6  318.45  5098.9  321.71  5129.4  323.03  5152.6  324.86  5175.5  324.86
  5227.8  328.16  5279.8  328.72    5303  329.92  5308.5  330.78  5334.2  331.06
#Mann= 4 ,-1 , 0
  4681.7      .1       0  4717.8     .05       0  4967.5     .03       0
  5022.3     .05       0
Bank Sta=4978.5,5022.3
XS Rating Curve= 0 ,0
Exp/Cntr=0.3,0.1

Type RM Length L Ch R = 1 ,599     ,123,123,123
BEGIN DESCRIPTION:
Mapping XS 8a53563b
END DESCRIPTION:
XS GIS Cut Line= 2
      2287743.73     13412045.29      2287124.57     13412058.39
#Sta/Elev= 30
  4707.1  324.11  4713.1  323.57  4753.1   323.4  4773.1  322.15  4783.1  322.28
  4803.1   321.6  4823.1  321.76  4843.1  320.58  4853.1  319.72  4863.1  319.76
  4873.1  318.76  4893.2  318.23  4903.2  317.54  4953.2  316.12  4963.2  315.31
  4973.2  315.15  4993.2  314.21  5000.2  313.74  5002.9  313.24  5006.2  313.74
  5012.9   313.9  5023.2  315.47  5083.2  315.97  5093.2  316.08  5123.2   316.8
  5133.2  317.43  5183.2  318.94  5243.2  319.69  5273.2  320.72  5326.4  321.88
#Mann= 3 ,-1 , 0
  4707.1     .05       0  4953.2     .04       0  5083.2     .05       0
Bank Sta=4953.2,5093.2
XS Rating Curve= 0 ,0
Exp/Cntr=0.3,0.1

Type RM Length L Ch R = 1 ,476     ,293,293,293
BEGIN DESCRIPTION:
UNT048 IN SUCR 2.0
END DESCRIPTION:
XS GIS Cut Line= 2
      2287737.16     13411920.81      2287154.08     13411960.12
#Sta/Elev= 30
  4661.8  324.82  4676.8  325.24  4681.8  324.68  4691.3  324.34  4701.3  323.62
  4771.5  321.78  4781.5  322.28  4791.5  322.12  4801.6  321.19  4811.6   320.8
  4821.3  319.97  4851.7   318.4  4921.8  316.84  4951.9  315.93  4961.9  316.01
  4970.8  315.57  4975.8  315.07    4992  312.46    4999  312.39  5001.8  311.89
    5005  312.39    5012  312.92  5032.1  313.98  5042.1  314.06  5052.1  313.69
  5125.3   314.9  5212.5  317.43  5222.5  318.16  5232.5  318.21  5246.2  318.71
#Mann= 3 ,-1 , 0
  4661.8     .05       0  4970.8     .03       0  5125.3     .05       0
Bank Sta=4975.8,5125.3
XS Rating Curve= 0 ,0
Exp/Cntr=0.3,0.1

Type RM Length L Ch R = 1 ,183     ,0,0,0
BEGIN DESCRIPTION:
UNT048 IN SUCR 1.0
END DESCRIPTION:
XS GIS Cut Line= 3
      2287543.87     13411553.93      2287334.25     13411580.13
      2287108.22     13411986.32
#Sta/Elev= 30
  4673.3  322.48  4729.9  320.86  4760.1  321.16  4770.2  320.32  4821.7  319.21
  4850.8  318.07  4884.6  318.24  4892.8  317.33  4903.1  317.22  4930.6   315.9
  4946.6  315.97  4983.8  313.78  4995.5   310.7  4998.7   311.2  5018.1  312.38
  5027.8  312.18    5041  312.99  5063.9  312.91  5076.9  312.14  5092.9  313.19
  5121.1  313.73  5158.1  313.82  5211.9  315.55  5255.3   317.6  5269.9  317.78
  5304.5  319.13  5320.5  319.27  5327.1  320.05  5342.2  320.77  5349.4   320.7
#Mann= 3 , 0 , 0
  4673.3     .05       0  4983.8     .03       0  5158.1     .05       0
Bank Sta=4983.8,5158.1
XS Rating Curve= 0 ,0
Exp/Cntr=0.3,0.1

Chan Stop Cuts=-1
Use User Specified Reach Order=0
Composite Channel Slope=5