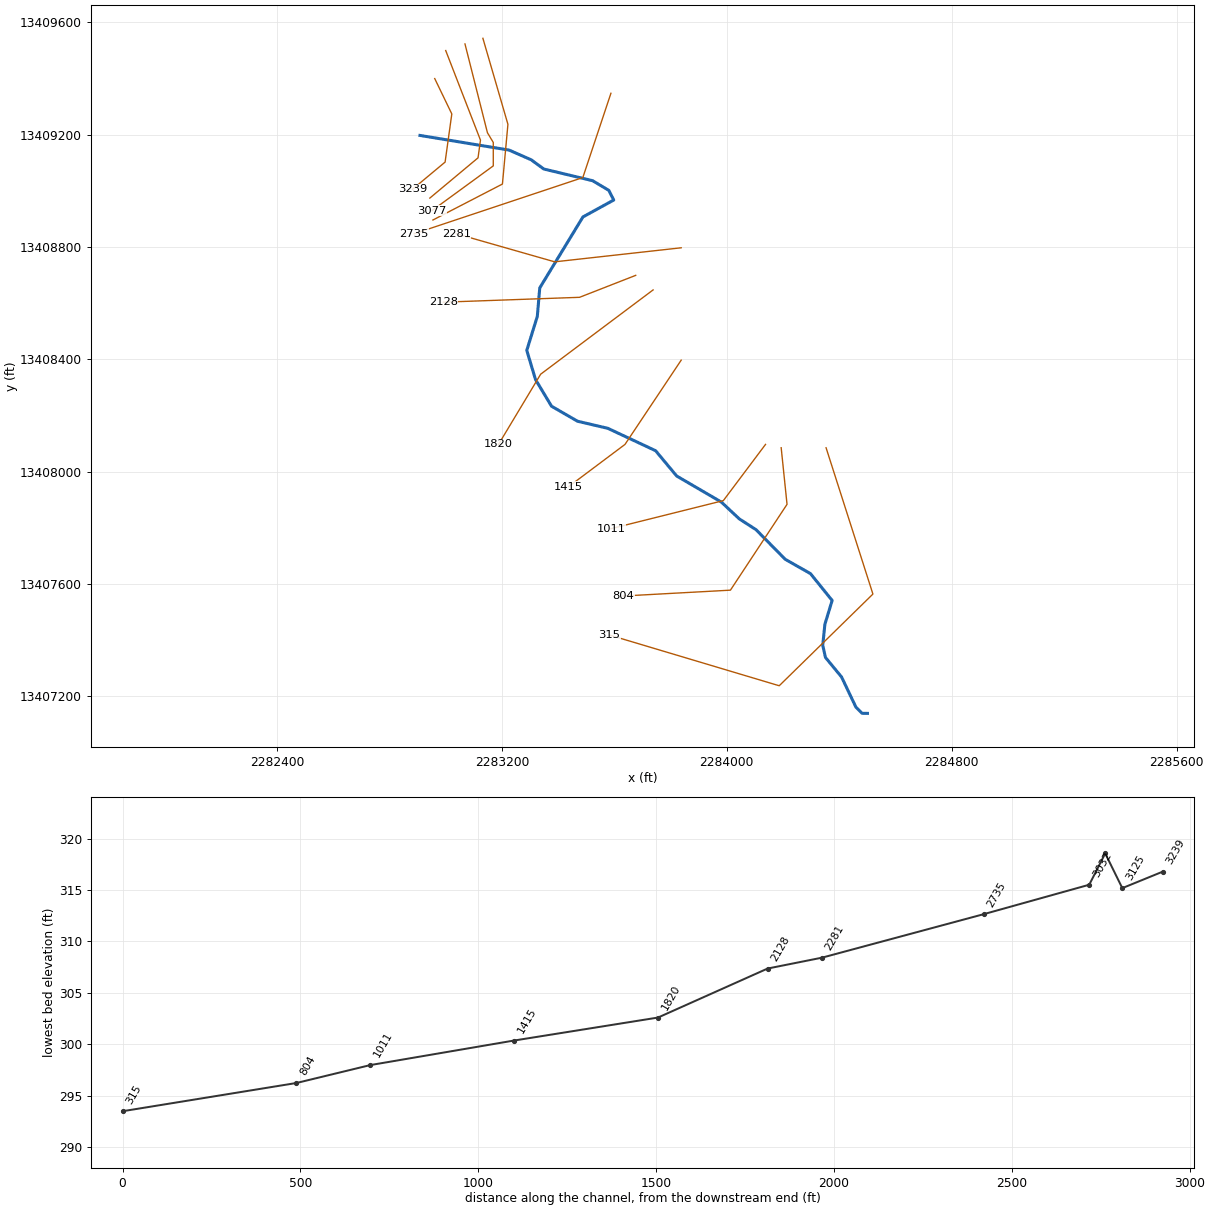
--- UNT050 IN SUCR.prj (project) ---

Proj Title=UNT050 IN SUCR Base Level Engineering
Current Plan=p01
Default Exp/Contr=0.3,0.1
English Units
Geom File=g01
Flow File=f01
Plan File=p01
BEGIN DESCRIPTION:
UNT050 IN SUCR
END DESCRIPTION:

--- UNT050 IN SUCR.p01 (plan) ---

Plan Title=Multiple Run
Short Identifier=Multiple
Geom File=g01
Flow File=f01
Subcritical Flow
K Sum by GR= 0
Std Step Tol= 0.01
Critical Tol= 0.01
Num of Std Step Trials= 20
Max Error Tol= 0.3
Flow Tol Ratio= 0.001
Split Flow NTrial= 30
Split Flow Tol= 0.02
Split Flow Ratio= 0.02
Log Output Level= 0
Friction Slope Method= 1
Unsteady Friction Slope Method= 2
Unsteady Bridges Friction Slope Method= 1
Parabolic Critical Depth
Global Vel Dist=  1 , 1 , 1
Global Log Level= 0
CheckData=True
Encroach Param= -1, 0, 0, 0
BEGIN DESCRIPTION:
Multiple Run
END DESCRIPTION:

--- UNT050 IN SUCR.f01 (steady flow) ---

Flow Title=Multiple
Number of Profiles=7
Profile Names=10-year,25-year,50-year,1pct_min,100-year,1pct_plu,500-year
River Rch & RM= UNT050 IN SUCR,Reach-1,3239
     199     270     327     292     395     534     583
River Rch & RM= UNT050 IN SUCR,Reach-1,2281
     219     299     363     326     440     595     655
Boundary for River Rch & Prof#=UNT050 IN SUCR,Reach-1,1
Up Type=0
Dn Type=3
Dn Slope=0.005
Boundary for River Rch & Prof#=UNT050 IN SUCR,Reach-1,2
Up Type=0
Dn Type=3
Dn Slope=0.005
Boundary for River Rch & Prof#=UNT050 IN SUCR,Reach-1,3
Up Type=0
Dn Type=3
Dn Slope=0.005
Boundary for River Rch & Prof#=UNT050 IN SUCR,Reach-1,4
Up Type=0
Dn Type=3
Dn Slope=0.005
Boundary for River Rch & Prof#=UNT050 IN SUCR,Reach-1,5
Up Type=0
Dn Type=3
Dn Slope=0.005
Boundary for River Rch & Prof#=UNT050 IN SUCR,Reach-1,6
Up Type=0
Dn Type=3
Dn Slope=0.005
Boundary for River Rch & Prof#=UNT050 IN SUCR,Reach-1,7
Up Type=0
Dn Type=3
Dn Slope=0.005

--- UNT050 IN SUCR.g01 (geometry) ---

Geom Title=Existing Conditions

River Reach=UNT050 IN SUCR,Reach-1
Reach XY= 30
      2282908.34     13409196.85      2283225.52     13409144.65
      2283304.00     13409110.08      2283348.78     13409077.33
      2283522.39     13409035.73      2283580.28     13409001.23
      2283597.72     13408966.85      2283488.23     13408906.74
      2283334.44     13408653.97      2283325.82     13408552.70
      2283288.31     13408431.64      2283319.52     13408327.60
      2283376.36     13408232.90      2283468.78     13408179.44
      2283576.62     13408154.20      2283746.68     13408074.44
      2283821.48     13407984.55      2283980.54     13407891.72
      2284044.32     13407831.86      2284104.09     13407793.24
      2284207.76     13407688.01      2284297.73     13407636.84
      2284374.80     13407541.35      2284348.90     13407456.35
      2284341.37     13407381.73      2284351.08     13407338.37
      2284408.24     13407269.00      2284459.46     13407161.36
      2284481.16     13407139.66      2284500.38     13407139.40

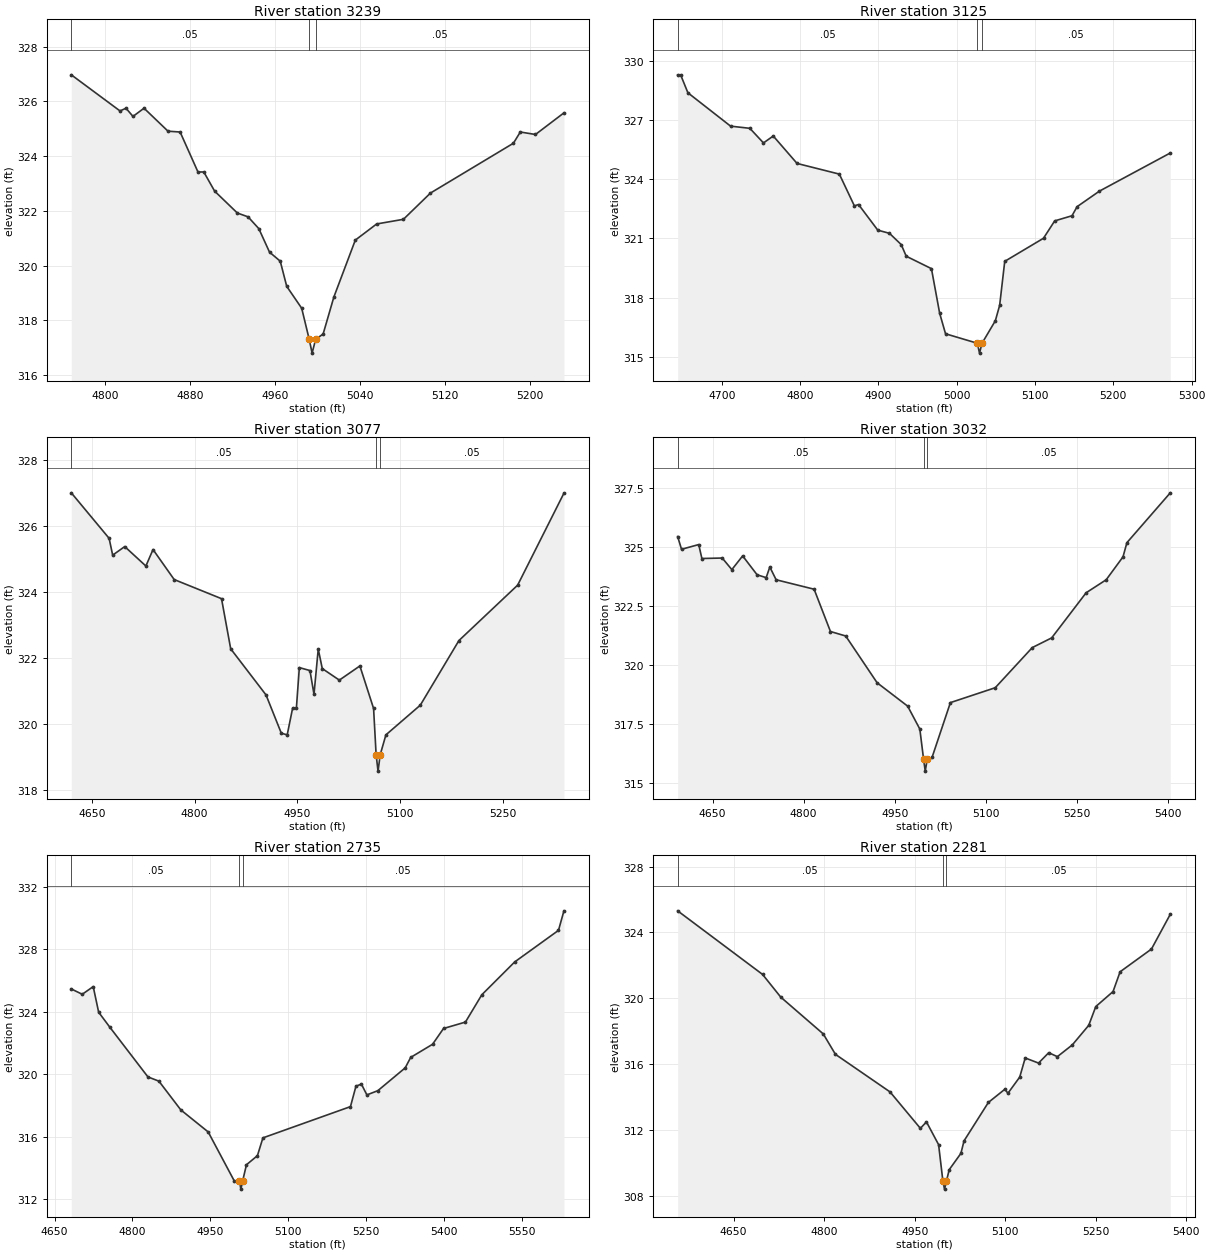
Type RM Length L Ch R = 1,3239,114,114,114
BEGIN DESCRIPTION:
UNT050 IN SUCR 7.0
END DESCRIPTION:
XS GIS Cut Line= 4
      2282960.83     13409399.19      2283021.58     13409273.34
      2282997.71     13409101.90      2282881.59     13409005.13
#Sta/Elev= 30
  4768.1  326.97  4814.0  325.65  4819.6  325.75  4826.2  325.45  4836.6  325.75
  4859.2  324.91  4870.6  324.88  4887.4  323.42  4892.9  323.42  4903.1  322.72
  4924.5  321.92  4934.6  321.78  4944.7  321.35  4954.8  320.49  4964.9  320.16
  4971.0  319.24  4985.1  318.44  4992.2  317.30  4994.9  316.80  4998.2  317.30
  5005.3  317.50  5015.4  318.85  5035.6  320.93  5055.7  321.52  5080.9  321.69
  5106.4  322.65  5184.5  324.47  5191.0  324.88  5205.3  324.79  5232.1  325.58
#Mann=3,-1,0
  4768.1    0.05       0  4992.2    0.03       0  4998.2    0.05       0
Bank Sta=4992.2,4998.2
Exp/Cntr=0.3,0.1

Type RM Length L Ch R = 1,3125,48,48,48
BEGIN DESCRIPTION:
Mapping XS eb374466
END DESCRIPTION:
XS GIS Cut Line= 4
      2282999.89     13409499.03      2283123.58     13409180.03
      2283114.90     13409117.09      2282943.44     13408973.85
#Sta/Elev= 30
  4643.6  329.29  4647.4  329.29  4656.7  328.38  4711.2  326.69  4735.8  326.58
  4753.2  325.84  4765.7  326.19  4796.1  324.80  4850.1  324.26  4869.3  322.65
  4874.6  322.72  4899.2  321.42  4914.1  321.26  4929.1  320.69  4935.5  320.10
  4967.7  319.47  4978.2  317.21  4985.7  316.17  5026.3  315.69  5029.1  315.19
  5032.3  315.69  5049.3  316.83  5054.8  317.61  5061.3  319.84  5110.8  321.01
  5125.1  321.89  5147.2  322.15  5153.7  322.61  5182.3  323.40  5272.7  325.33
#Mann=3,-1,0
  4643.6    0.05       0  5026.3    0.03       0  5032.3    0.05       0
Bank Sta=5026.3,5032.3
Exp/Cntr=0.3,0.1

Type RM Length L Ch R = 1,3077,45,45,45
BEGIN DESCRIPTION:
Mapping XS aff1f325
END DESCRIPTION:
XS GIS Cut Line= 5
      2283068.46     13409522.47      2283148.32     13409206.50
      2283169.15     13409171.78      2283169.15     13409088.45
      2282951.52     13408929.54
#Sta/Elev= 30
  4620.1  327.01  4675.3  325.63  4680.5  325.12  4698.1  325.38  4729.0  324.79
  4739.4  325.29  4770.3  324.38  4839.4  323.80  4852.8  322.28  4904.4  320.88
  4926.7  319.72  4935.3  319.67  4943.2  320.48  4948.7  320.48  4953.0  321.71
  4968.5  321.62  4974.4  320.90  4980.6  322.27  4986.5  321.68  5011.4  321.33
  5041.4  321.76  5061.4  320.47  5065.1  319.07  5067.9  318.57  5071.1  319.07
  5079.4  319.67  5129.6  320.57  5186.0  322.53  5271.7  324.21  5339.3  327.00
#Mann=3,-1,0
  4620.1    0.05       0  5065.1    0.03       0  5071.1    0.05       0
Bank Sta=5065.1,5071.1
Exp/Cntr=0.3,0.1

Type RM Length L Ch R = 1,3032,297,297,297
BEGIN DESCRIPTION:
Mapping XS a6c723c5
END DESCRIPTION:
XS GIS Cut Line= 4
      2283132.25     13409542.49      2283221.24     13409236.45
      2283201.71     13409023.78      2282954.35     13408895.76
#Sta/Elev= 30
  4592.6  325.45  4599.0  324.91  4627.3  325.11  4632.5  324.52  4666.0  324.54
  4681.8  324.05  4699.6  324.63  4723.4  323.83  4738.3  323.71  4744.3  324.16
  4754.7  323.62  4817.2  323.22  4844.1  321.43  4869.2  321.24  4920.9  319.26
  4971.2  318.27  4991.2  317.30  4997.4  316.02  5000.1  315.52  5003.4  316.02
  5011.3  316.10  5041.5  318.42  5115.3  319.05  5176.3  320.75  5208.2  321.16
  5264.9  323.07  5297.9  323.62  5325.6  324.59  5332.0  325.19  5403.4  327.30
#Mann=3,-1,0
  4592.6    0.05       0  4997.4    0.03       0  5003.4    0.05       0
Bank Sta=4997.4,5003.4
Exp/Cntr=0.3,0.1

Type RM Length L Ch R = 1,2735,454,454,454
BEGIN DESCRIPTION:
UNT050 IN SUCR 6.0
END DESCRIPTION:
XS GIS Cut Line= 3
      2283587.73     13409346.89      2283487.72     13409046.85
      2282887.74     13408846.86
#Sta/Elev= 30
  4682.2  325.46  4703.3  325.12  4724.4  325.61  4734.9  323.97  4756.0  323.03
  4829.8  319.83  4850.9  319.56  4893.1  317.72  4945.8  316.31  4995.8  313.19
  5006.0  313.15  5008.8  312.65  5012.0  313.15  5019.5  314.21  5040.6  314.79
  5051.2  315.93  5219.8  317.93  5230.4  319.24  5240.9  319.37  5251.4  318.68
  5272.5  318.95  5325.2  320.41  5335.8  321.08  5377.9  321.92  5399.0  322.93
  5441.2  323.34  5472.8  325.09  5536.1  327.19  5620.4  329.21  5630.9  330.46
#Mann=3,-1,0
  4682.2    0.05       0  5006.0    0.03       0  5012.0    0.05       0
Bank Sta=5006,5012
Exp/Cntr=0.3,0.1

Type RM Length L Ch R = 1,2281,153,153,153
BEGIN DESCRIPTION:
UNT050 IN SUCR 5.0
END DESCRIPTION:
XS GIS Cut Line= 3
      2283837.69     13408796.85      2283387.72     13408746.85
      2283037.77     13408846.84
#Sta/Elev= 30
  4557.1  325.31  4697.9  321.45  4728.1  320.07  4798.5  317.84  4818.7  316.60
  4909.2  314.32  4959.5  312.11  4969.6  312.50  4989.7  311.12  4996.8  308.92
  4999.5  308.42  5002.8  308.92  5007.3  309.60  5026.7  310.59  5031.9  311.35
  5072.2  313.68  5099.5  314.48  5104.7  314.24  5124.2  315.22  5133.3  316.38
  5155.4  316.07  5172.3  316.70  5186.6  316.46  5211.3  317.17  5238.6  318.36
  5250.3  319.50  5278.9  320.41  5290.6  321.61  5342.6  322.99  5373.8  325.10
#Mann=3,-1,0
  4557.1    0.05       0  4996.8    0.03       0  5002.8    0.05       0
Bank Sta=4996.8,5002.8
Exp/Cntr=0.3,0.1

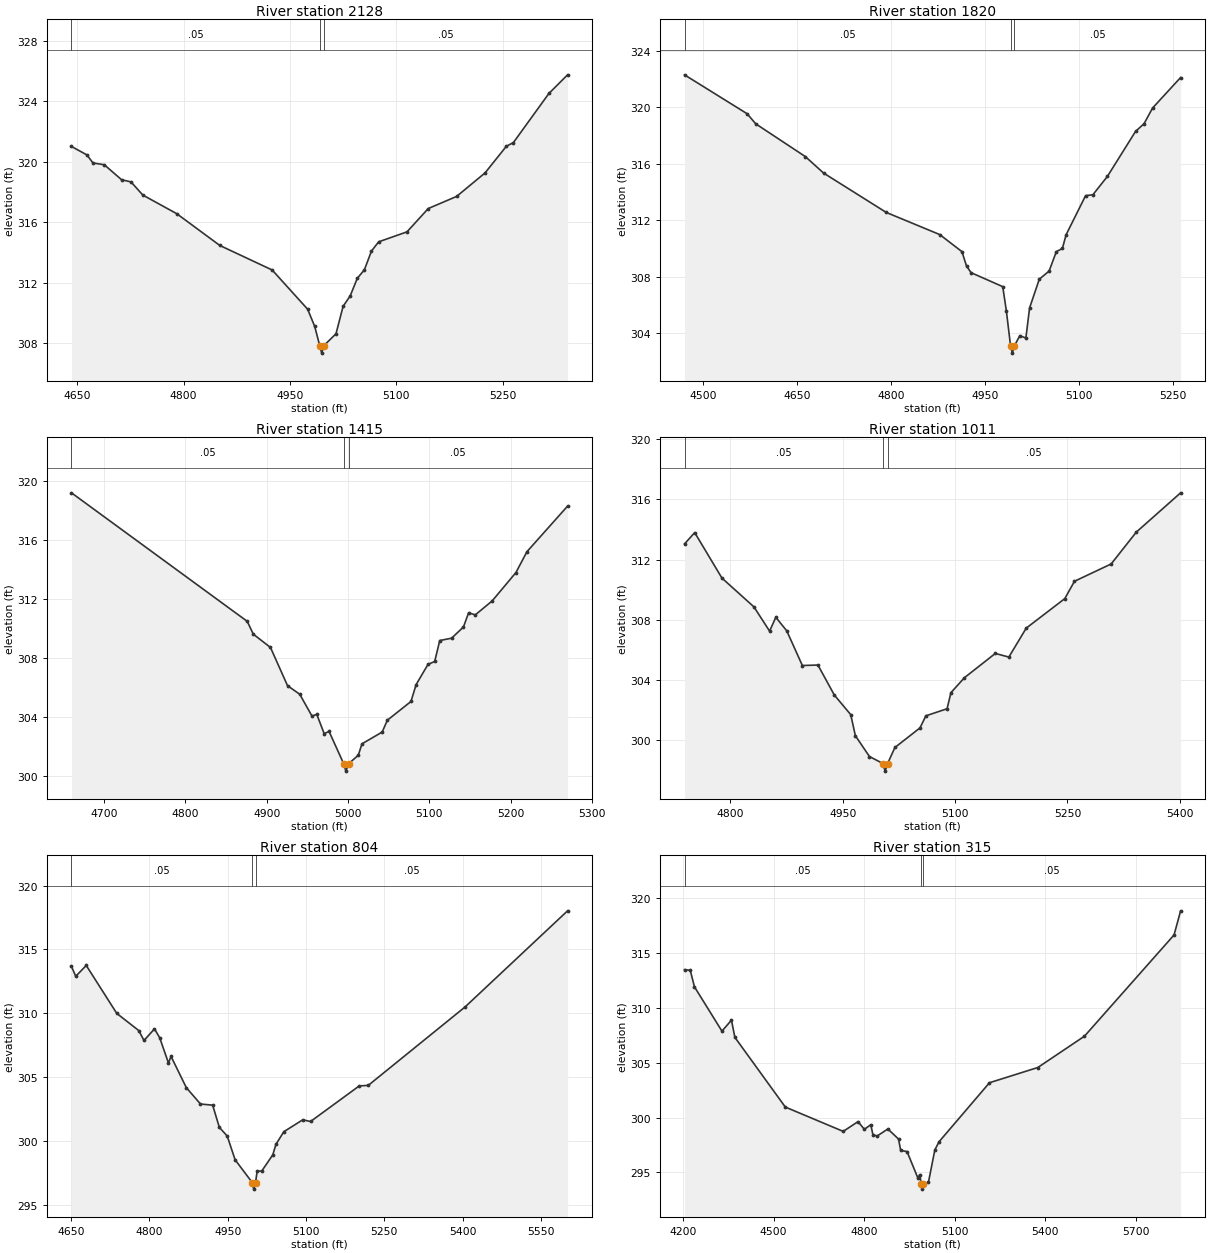
Type RM Length L Ch R = 1,2128,308,308,308
BEGIN DESCRIPTION:
Mapping XS 25541d7a
END DESCRIPTION:
XS GIS Cut Line= 3
      2283675.89     13408698.70      2283476.21     13408620.56
      2282991.44     13408603.25
#Sta/Elev= 30
  4642.0  321.01  4663.8  320.45  4672.3  319.92  4688.3  319.80  4712.7  318.81
  4725.9  318.67  4742.6  317.80  4790.4  316.57  4851.2  314.47  4925.0  312.85
  4975.0  310.26  4985.0  309.12  4992.0  307.86  4994.8  307.36  4998.0  307.86
  5015.0  308.64  5025.0  310.45  5035.0  311.14  5045.0  312.30  5055.0  312.86
  5065.0  314.10  5075.1  314.71  5115.1  315.37  5145.1  316.91  5185.1  317.71
  5225.1  319.26  5255.2  321.02  5265.2  321.27  5315.2  324.51  5341.5  325.74
#Mann=3,-1,0
  4642.0    0.05       0  4992.0    0.03       0  4998.0    0.05       0
Bank Sta=4992,4998
Exp/Cntr=0.3,0.1

Type RM Length L Ch R = 1,1820,405,405,405
BEGIN DESCRIPTION:
UNT050 IN SUCR 4.0
END DESCRIPTION:
XS GIS Cut Line= 3
      2283737.74     13408646.87      2283337.72     13408346.85
      2283187.70     13408096.83
#Sta/Elev= 30
  4470.5  322.31  4570.5  319.55  4584.1  318.84  4663.2  316.52  4692.4  315.35
  4792.4  312.56  4877.8  310.99  4913.2  309.78  4920.5  308.76  4927.8  308.29
  4978.3  307.30  4984.1  305.57  4990.8  303.09  4993.6  302.59  4996.8  303.09
  5005.5  303.83  5015.2  303.66  5021.1  305.79  5036.6  307.83  5052.2  308.40
  5063.8  309.78  5073.5  310.01  5079.4  310.98  5110.5  313.75  5122.1  313.81
  5145.4  315.12  5190.2  318.30  5203.8  318.85  5217.4  319.96  5262.1  322.12
#Mann=3,-1,0
  4470.5    0.05       0  4990.8    0.03       0  4996.8    0.05       0
Bank Sta=4990.8,4996.8
Exp/Cntr=0.3,0.1

Type RM Length L Ch R = 1,1415,404,404,404
BEGIN DESCRIPTION:
UNT050 IN SUCR 3.0
END DESCRIPTION:
XS GIS Cut Line= 3
      2283837.71     13408396.84      2283637.72     13408096.85
      2283437.75     13407946.87
#Sta/Elev= 30
  4659.7  319.21  4876.0  310.50  4883.5  309.63  4904.6  308.73  4925.6  306.14
  4940.6  305.56  4955.6  304.09  4961.6  304.19  4970.7  302.89  4976.7  303.04
  4994.7  300.85  4997.4  300.35  5000.7  300.85  5012.7  301.43  5017.2  302.20
  5042.1  303.00  5048.4  303.80  5077.5  305.07  5083.8  306.21  5098.4  307.58
  5106.7  307.78  5112.9  309.20  5127.5  309.36  5142.1  310.12  5148.4  311.08
  5156.7  310.94  5177.5  311.89  5206.7  313.81  5220.2  315.22  5270.2  318.31
#Mann=3,-1,0
  4659.7    0.05       0  4994.7    0.03       0  5000.7    0.05       0
Bank Sta=4994.7,5000.7
Exp/Cntr=0.3,0.1

Type RM Length L Ch R = 1,1011,207,207,207
BEGIN DESCRIPTION:
UNT050 IN SUCR 2.0
END DESCRIPTION:
XS GIS Cut Line= 3
      2284137.74     13408096.87      2283987.72     13407896.85
      2283587.75     13407796.86
#Sta/Elev= 30
  4738.8  313.04  4752.4  313.79  4788.8  310.77  4831.5  308.86  4852.4  307.25
  4860.7  308.17  4875.3  307.27  4896.1  304.97  4916.9  305.00  4938.8  303.01
  4960.7  301.71  4966.9  300.31  4985.7  298.93  5003.9  298.46  5006.6  297.96
  5009.9  298.46  5019.7  299.53  5053.2  300.83  5061.0  301.63  5089.3  302.10
  5094.5  303.17  5112.5  304.16  5153.7  305.77  5171.8  305.53  5195.0  307.45
  5246.5  309.41  5259.4  310.56  5308.4  311.71  5341.9  313.82  5401.1  316.43
#Mann=3,-1,0
  4738.8    0.05       0  5003.9    0.03       0  5009.9    0.05       0
Bank Sta=5003.9,5009.9
Exp/Cntr=0.3,0.1

Type RM Length L Ch R = 1,804,489,489,489
BEGIN DESCRIPTION:
Mapping XS a3f1349c
END DESCRIPTION:
XS GIS Cut Line= 4
      2284193.46     13408085.00      2284214.29     13407883.59
      2284012.90     13407578.03      2283631.81     13407557.24
#Sta/Elev= 30
  4650.9  313.67  4659.1  312.90  4679.2  313.75  4737.7  309.99  4779.7  308.65
  4789.8  307.87  4809.9  308.78  4819.9  308.08  4836.6  306.11  4841.6  306.62
  4870.9  304.17  4898.0  302.89  4921.3  302.80  4934.1  301.06  4949.2  300.38
  4964.3  298.52  4997.4  296.72  5000.1  296.22  5003.4  296.72  5006.4  297.61
  5015.5  297.65  5036.5  298.91  5042.5  299.73  5057.6  300.72  5093.7  301.65
  5108.8  301.52  5202.1  304.31  5219.3  304.35  5404.8  310.50  5601.0  318.03
#Mann=3,-1,0
  4650.9    0.05       0  4997.4    0.03       0  5003.4    0.05       0
Bank Sta=4997.4,5003.4
Exp/Cntr=0.3,0.1

Type RM Length L Ch R = 1,315,0,0,0
BEGIN DESCRIPTION:
UNT050 IN SUCR 1.0
END DESCRIPTION:
XS GIS Cut Line= 4
      2284353.18     13408084.97      2284519.85     13407564.14
      2284186.51     13407237.75      2283582.57     13407418.24
#Sta/Elev= 30
  4205.1  313.50  4224.1  313.44  4238.1  311.93  4329.1  307.89  4360.6  308.89
  4372.0  307.32  4539.1  300.96  4730.9  298.74  4779.9  299.63  4801.0  298.93
  4822.3  299.35  4829.3  298.44  4843.4  298.32  4878.9  298.96  4914.2  298.04
  4921.3  297.00  4942.4  296.90  4977.9  294.51  4984.9  294.79  4989.0  293.97
  4991.8  293.47  4995.0  293.97  5013.2  294.08  5034.5  297.05  5048.6  297.80
  5215.5  303.18  5375.7  304.57  5530.3  307.43  5827.1  316.67  5848.8  318.87
#Mann=3,-1,0
  4205.1    0.05       0  4989.0    0.03       0  4995.0    0.05       0
Bank Sta=4989,4995
Exp/Cntr=0.3,0.1

Chan Stop Cuts=-1