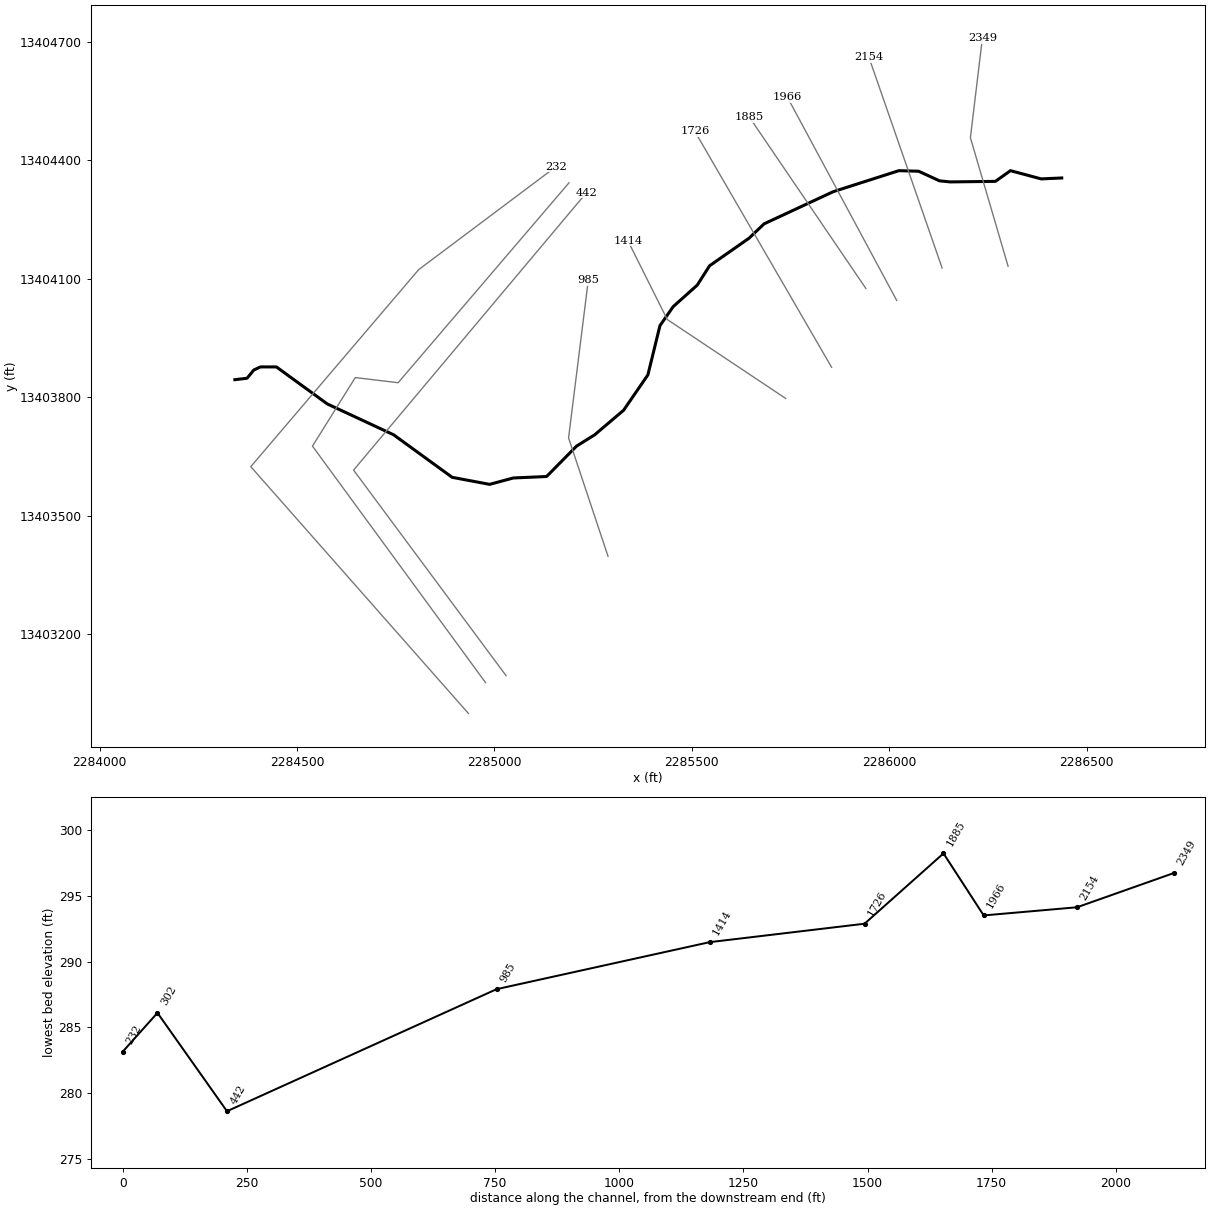
--- UNT051 IN SUCR.prj (project) ---

Proj Title=UNT051 IN SUCR Base Level Engineering
Current Plan=p01
Default Exp/Contr=0.3,0.1
English Units
Geom File=g01
Flow File=f01
Plan File=p01
BEGIN DESCRIPTION:
UNT051 IN SUCR
END DESCRIPTION:

--- UNT051 IN SUCR.p01 (plan) ---

Plan Title=Multiple Run
Short Identifier=Multiple
Geom File=g01
Flow File=f01
Subcritical Flow
K Sum by GR= 0
Std Step Tol= 0.01
Critical Tol= 0.01
Num of Std Step Trials= 20
Max Error Tol= 0.3
Flow Tol Ratio= 0.001
Split Flow NTrial= 30
Split Flow Tol= 0.02
Split Flow Ratio= 0.02
Log Output Level= 0
Friction Slope Method= 1
Unsteady Friction Slope Method= 2
Unsteady Bridges Friction Slope Method= 1
Parabolic Critical Depth
Global Vel Dist=  1 , 1 , 1
Global Log Level= 0
CheckData=True
Encroach Param= -1, 0, 0, 0
BEGIN DESCRIPTION:
Multiple Run
END DESCRIPTION:

--- UNT051 IN SUCR.f01 (steady flow) ---

Flow Title=Multiple
Number of Profiles=7
Profile Names=10-year,25-year,50-year,1pct_min,100-year,1pct_plu,500-year
River Rch & RM= UNT051 IN SUCR,Reach-1,2349
     301     417     513     464     628     849     948
Boundary for River Rch & Prof#=UNT051 IN SUCR,Reach-1,1
Up Type=0
Dn Type=3
Dn Slope=0.005
Boundary for River Rch & Prof#=UNT051 IN SUCR,Reach-1,2
Up Type=0
Dn Type=3
Dn Slope=0.005
Boundary for River Rch & Prof#=UNT051 IN SUCR,Reach-1,3
Up Type=0
Dn Type=3
Dn Slope=0.005
Boundary for River Rch & Prof#=UNT051 IN SUCR,Reach-1,4
Up Type=0
Dn Type=3
Dn Slope=0.005
Boundary for River Rch & Prof#=UNT051 IN SUCR,Reach-1,5
Up Type=0
Dn Type=3
Dn Slope=0.005
Boundary for River Rch & Prof#=UNT051 IN SUCR,Reach-1,6
Up Type=0
Dn Type=3
Dn Slope=0.005
Boundary for River Rch & Prof#=UNT051 IN SUCR,Reach-1,7
Up Type=0
Dn Type=3
Dn Slope=0.005

--- UNT051 IN SUCR.g01 (geometry) ---

Geom Title=Existing Conditions

River Reach=UNT051 IN SUCR,Reach-1
Reach XY= 30
      2286437.00     13404355.32      2286384.89     13404353.01
      2286307.19     13404373.87      2286268.92     13404346.76
      2286154.33     13404345.37      2286127.25     13404348.15
      2286074.47     13404372.45      2286024.47     13404373.84
      2285858.33     13404320.72      2285682.98     13404239.12
      2285644.93     13404202.79      2285544.90     13404132.91
      2285513.73     13404084.00      2285452.69     13404029.39
      2285419.23     13403981.26      2285388.68     13403856.64
      2285327.19     13403767.02      2285253.87     13403704.75
      2285207.92     13403676.10      2285132.08     13403599.10
      2285047.78     13403595.39      2284987.72     13403579.21
      2284892.83     13403597.06      2284744.47     13403704.83
      2284576.50     13403782.96      2284447.59     13403876.71
      2284407.23     13403876.71      2284390.30     13403868.89
      2284373.37     13403848.06      2284342.34     13403844.37

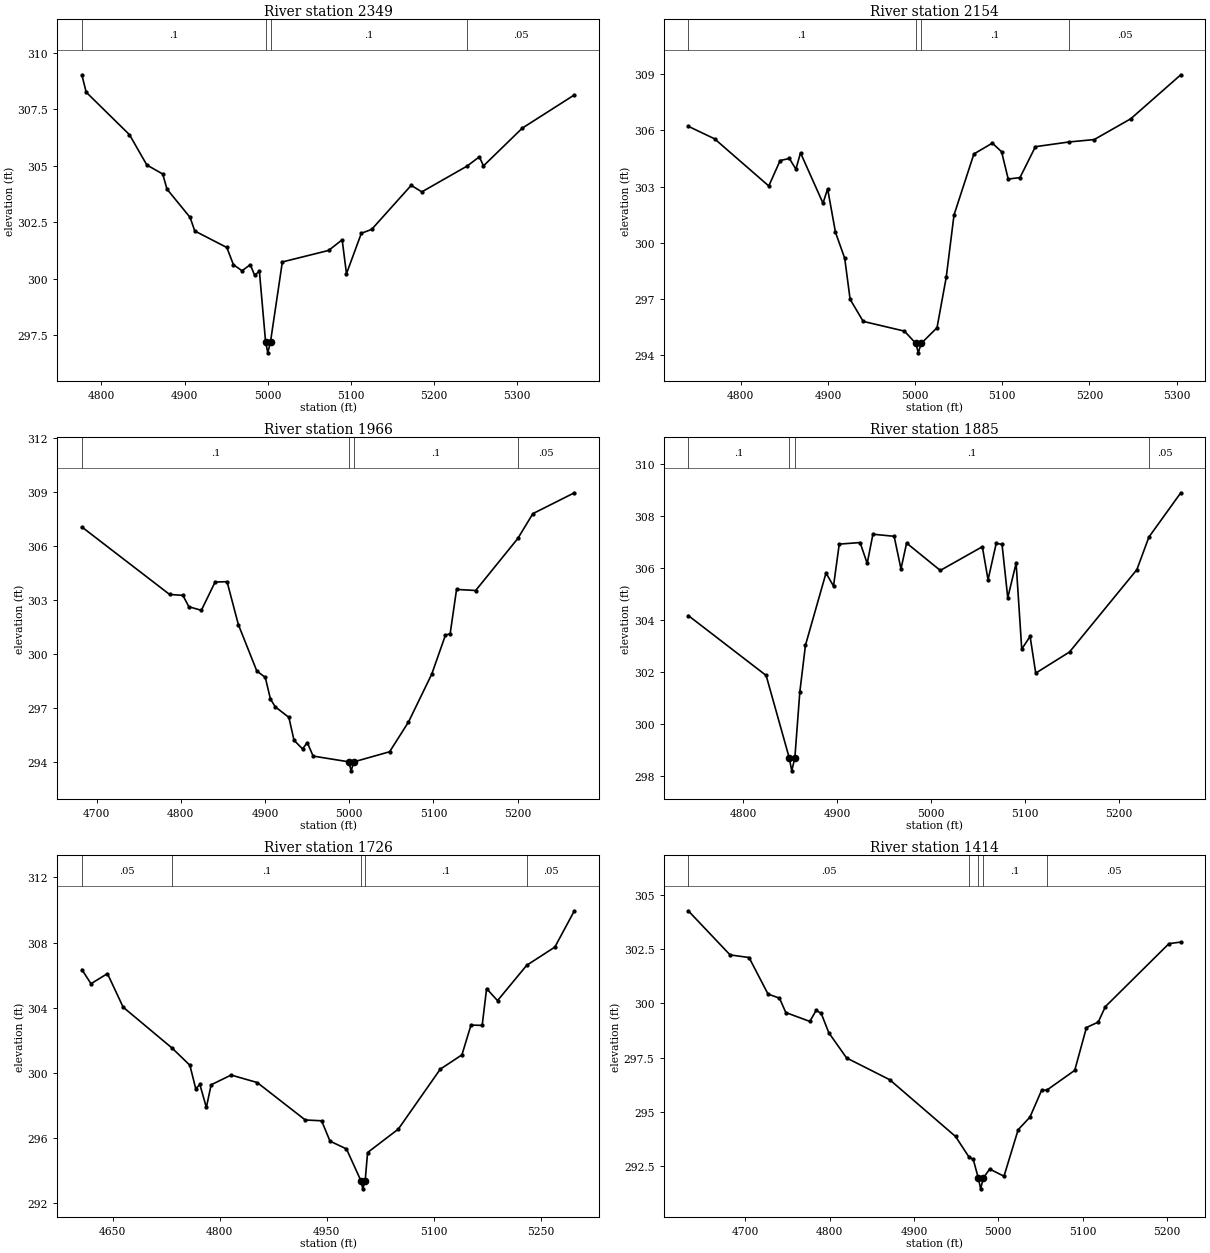
Type RM Length L Ch R = 1,2349,195,195,195
BEGIN DESCRIPTION:
UNT051 IN SUCR 5.0
END DESCRIPTION:
XS GIS Cut Line= 3
      2286301.11     13404131.83      2286205.61     13404457.37
      2286235.99     13404709.08
#Sta/Elev= 30
  4776.4  309.02  4781.6  308.25  4833.7  306.37  4854.6  305.03  4873.7  304.63
  4878.9  303.96  4906.7  302.71  4912.3  302.11  4950.9  301.38  4958.8  300.62
  4969.2  300.35  4979.1  300.62  4984.3  300.16  4990.1  300.32  4997.5  297.22
  5000.2  296.72  5003.5  297.22  5017.7  300.74  5073.4  301.25  5089.7  301.72
  5094.9  300.22  5112.8  302.01  5125.2  302.18  5172.8  304.13  5185.6  303.84
  5240.0  304.98  5254.8  305.39  5259.8  304.99  5306.5  306.66  5369.2  308.13
#Mann=4,-1,0
  4776.4     0.1       0  4997.5    0.07       0  5003.5     0.1       0
  5240.0    0.05       0
Bank Sta=4997.5,5003.5
Exp/Cntr=0.3,0.1

Type RM Length L Ch R = 1,2154,188,188,188
BEGIN DESCRIPTION:
Mapping XS af5860e1
END DESCRIPTION:
XS GIS Cut Line= 2
      2286133.97     13404127.29      2285948.54     13404661.10
#Sta/Elev= 30
  4739.7  306.22  4769.9  305.55  4832.1  303.03  4845.1  304.39  4855.7  304.50
  4863.2  303.93  4868.5  304.80  4894.3  302.11  4899.6  302.88  4908.6  300.56
  4919.2  299.17  4925.4  296.98  4940.4  295.80  4987.7  295.28  5000.9  294.62
  5003.6  294.12  5006.9  294.62  5025.1  295.46  5035.7  298.16  5044.6  301.48
  5067.4  304.74  5088.6  305.32  5099.2  304.86  5106.8  303.40  5120.3  303.48
  5138.0  305.13  5176.3  305.38  5205.5  305.51  5247.4  306.62  5304.8  308.97
#Mann=4,-1,0
  4739.7     0.1       0  5000.9    0.07       0  5006.9     0.1       0
  5176.3    0.05       0
Bank Sta=5000.9,5006.9
Exp/Cntr=0.3,0.1

Type RM Length L Ch R = 1,1966,81,81,81
BEGIN DESCRIPTION:
Mapping XS eafb17aa
END DESCRIPTION:
XS GIS Cut Line= 2
      2286018.98     13404045.05      2285741.98     13404560.09
#Sta/Elev= 30
  4682.6  307.05  4786.8  303.30  4802.6  303.25  4809.6  302.62  4824.5  302.42
  4840.8  303.99  4855.0  304.01  4868.4  301.63  4890.3  299.05  4900.4  298.69
  4906.5  297.49  4912.2  297.06  4928.4  296.47  4934.5  295.20  4944.6  294.72
  4950.3  295.07  4957.2  294.32  4999.6  294.00  5002.3  293.50  5005.6  294.00
  5048.0  294.56  5070.4  296.21  5098.0  298.87  5114.3  301.04  5119.9  301.12
  5127.5  303.58  5150.2  303.52  5200.2  306.41  5218.1  307.79  5267.4  308.95
#Mann=4,-1,0
  4682.6     0.1       0  4999.6    0.07       0  5005.6     0.1       0
  5200.2    0.05       0
Bank Sta=4999.6,5005.6
Exp/Cntr=0.3,0.1

Type RM Length L Ch R = 1,1885,159,159,159
BEGIN DESCRIPTION:
UNT051 IN SUCR 4.0
END DESCRIPTION:
XS GIS Cut Line= 2
      2285940.85     13404075.43      2285645.70     13404509.48
#Sta/Elev= 30
  4741.4  304.17  4824.4  301.87  4849.0  298.71  4851.7  298.21  4855.0  298.71
  4860.3  301.24  4866.3  303.03  4888.2  305.80  4896.2  305.30  4902.3  306.91
  4924.5  306.97  4932.1  306.17  4938.2  307.29  4960.8  307.21  4968.1  305.96
  4974.1  306.95  5010.0  305.90  5054.8  306.81  5060.9  305.54  5069.6  306.94
  5075.8  306.90  5081.9  304.85  5090.8  306.18  5096.8  302.88  5105.7  303.37
  5111.7  301.96  5147.7  302.77  5219.5  305.93  5232.3  307.18  5266.3  308.88
#Mann=4,-1,0
  4741.4     0.1       0  4849.0    0.07       0  4855.0     0.1       0
  5232.3    0.05       0
Bank Sta=4849,4855
Exp/Cntr=0.3,0.1

Type RM Length L Ch R = 1,1726,312,312,312
BEGIN DESCRIPTION:
Mapping XS 2396b84e
END DESCRIPTION:
XS GIS Cut Line= 2
      2285854.06     13403875.77      2285507.65     13404473.32
#Sta/Elev= 30
  4606.6  306.34  4619.4  305.47  4642.5  306.09  4664.5  304.03  4733.3  301.51
  4758.1  300.46  4766.3  299.02  4772.1  299.28  4781.2  297.87  4787.9  299.26
  4815.9  299.86  4852.5  299.40  4919.9  297.10  4942.8  297.05  4954.6  295.80
  4977.7  295.32  4997.9  293.37  5000.6  292.87  5003.9  293.37  5007.3  295.10
  5050.4  296.54  5109.2  300.22  5139.6  301.10  5152.3  302.93  5168.0  302.91
  5174.2  305.17  5189.5  304.43  5230.4  306.60  5269.9  307.72  5297.3  309.95
#Mann=5,-1,0
  4606.6    0.05       0  4733.3     0.1       0  4997.9    0.07       0
  5003.9     0.1       0  5230.4    0.05       0
Bank Sta=4997.9,5003.9
Exp/Cntr=0.3,0.1

Type RM Length L Ch R = 1,1414,429,429,429
BEGIN DESCRIPTION:
UNT051 IN SUCR 3.0
END DESCRIPTION:
XS GIS Cut Line= 3
      2285737.71     13403796.86      2285437.72     13403996.85
      2285337.70     13404196.90
#Sta/Elev= 30
  4632.3  304.26  4681.9  302.23  4704.4  302.11  4726.9  300.43  4740.5  300.24
  4748.0  299.58  4776.5  299.17  4784.0  299.68  4790.0  299.54  4799.0  298.65
  4820.1  297.49  4871.2  296.49  4949.3  293.88  4965.5  292.92  4970.3  292.83
  4976.3  291.97  4979.1  291.47  4982.3  291.97  4989.8  292.38  5006.8  292.05
  5023.6  294.19  5037.6  294.77  5051.5  296.01  5057.6  296.01  5090.7  296.92
  5104.6  298.89  5118.6  299.14  5127.0  299.85  5202.5  302.75  5216.5  302.82
#Mann=5,-1,0
  4632.3    0.05       0  4965.5     0.1       0  4976.3    0.07       0
  4982.3     0.1       0  5057.6    0.05       0
Bank Sta=4976.3,4982.3
Exp/Cntr=0.3,0.1

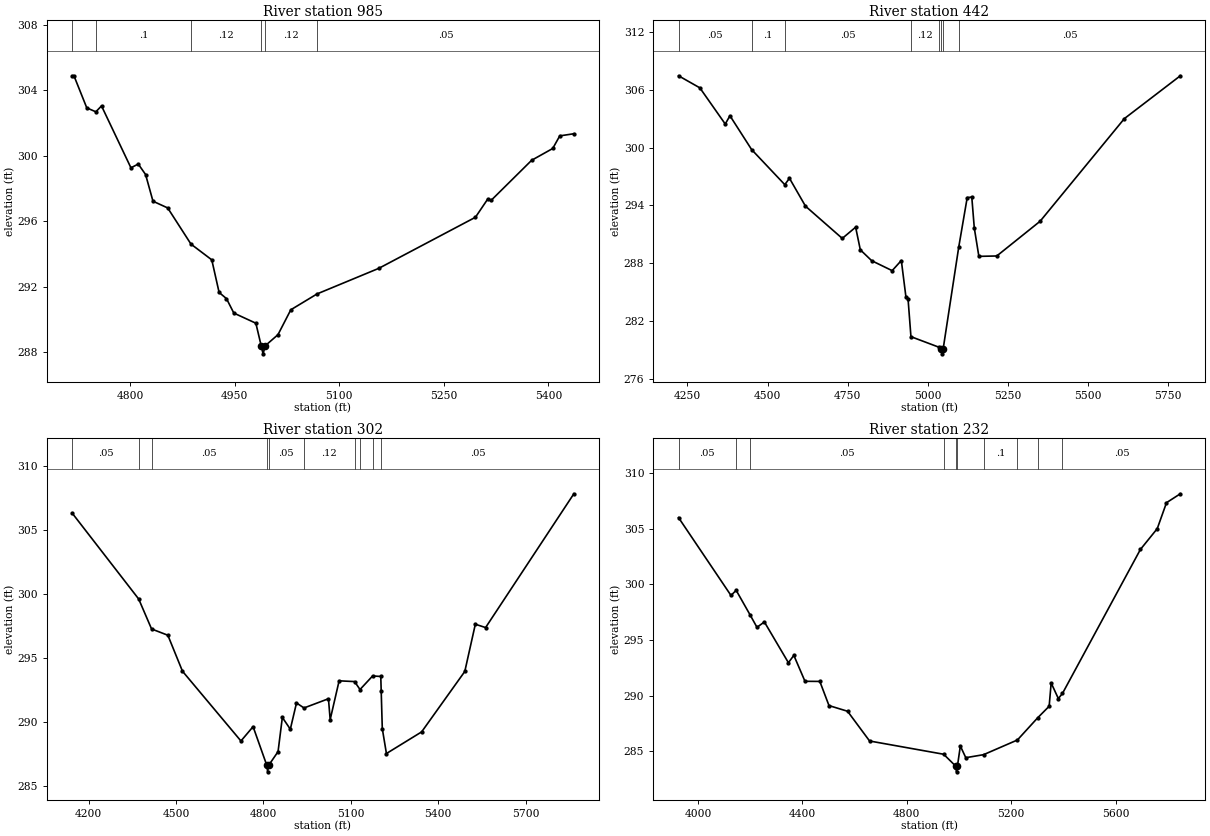
Type RM Length L Ch R = 1,985,543,543,543
BEGIN DESCRIPTION:
UNT051 IN SUCR 2.0
END DESCRIPTION:
XS GIS Cut Line= 3
      2285287.73     13403396.83      2285187.72     13403696.85
      2285237.72     13404096.89
#Sta/Elev= 30
  4717.1  304.88  4719.8  304.88  4738.2  302.92  4751.2  302.68  4759.3  303.04
  4801.5  299.26  4812.0  299.49  4822.5  298.85  4833.1  297.22  4854.2  296.81
  4887.6  294.60  4917.4  293.64  4927.9  291.65  4938.5  291.27  4949.0  290.39
  4980.6  289.77  4988.2  288.40  4990.9  287.90  4994.2  288.40  5012.3  289.07
  5030.7  290.59  5068.4  291.56  5156.8  293.12  5295.4  296.24  5313.0  297.35
  5318.1  297.28  5376.0  299.72  5406.2  300.44  5416.3  301.21  5436.5  301.34
#Mann=6,-1,0
  4717.1    0.05       0  4751.2     0.1       0  4887.6    0.12       0
  4988.2    0.07       0  4994.2    0.12       0  5068.4    0.05       0
Bank Sta=4988.2,4994.2
Exp/Cntr=0.3,0.1

Type RM Length L Ch R = 1,442,140,140,140
BEGIN DESCRIPTION:
Mapping XS 67e0f2d3
END DESCRIPTION:
XS GIS Cut Line= 3
      2285029.42     13403094.49      2284643.11     13403615.36
      2285233.05     13404318.07
#Sta/Elev= 30
  4222.3  307.44  4288.8  306.19  4368.1  302.44  4382.7  303.30  4450.5  299.79
  4553.9  296.16  4568.5  296.82  4618.5  293.93  4733.3  290.59  4775.0  291.75
  4789.6  289.41  4825.1  288.28  4889.0  287.25  4917.6  288.30  4931.9  284.54
  4938.5  284.36  4947.6  280.41  5035.5  279.31  5042.1  279.13  5044.9  278.63
  5048.1  279.13  5096.8  289.70  5123.2  294.82  5137.5  294.87  5145.3  291.67
  5159.6  288.73  5215.5  288.77  5350.8  292.37  5613.6  303.00  5788.3  307.44
#Mann=8,-1,0
  4222.3    0.05       0  4450.5     0.1       0  4553.9    0.05       0
  4947.6    0.12       0  5035.5     0.1       0  5042.1    0.07       0
  5048.1     0.1       0  5096.8    0.05       0
Bank Sta=5042.1,5048.1
Exp/Cntr=0.3,0.1

Type RM Length L Ch R = 1,302,70,70,70
BEGIN DESCRIPTION:
Mapping XS dfcdc552
END DESCRIPTION:
XS GIS Cut Line= 5
      2284977.33     13403077.14      2284538.95     13403676.12
      2284647.45     13403849.73      2284755.96     13403836.71
      2285188.82     13404343.16
#Sta/Elev= 30
  4143.4  306.32  4372.1  299.60  4416.3  297.26  4472.2  296.77  4522.4  293.96
  4723.1  288.51  4764.8  289.63  4812.0  286.60  4814.7  286.10  4818.0  286.60
  4850.5  287.68  4865.2  290.35  4892.6  289.43  4913.8  291.48  4939.6  291.09
  5023.5  291.81  5029.4  290.18  5060.1  293.21  5113.2  293.15  5131.8  292.53
  5175.1  293.59  5203.1  293.55  5204.6  292.38  5208.3  289.48  5222.5  287.53
  5343.3  289.22  5491.5  293.94  5527.7  297.63  5562.9  297.37  5865.9  307.82
#Mann=10,-1,0
  4143.4    0.05       0  4372.1     0.1       0  4416.3    0.05       0
  4812.0    0.07       0  4818.0    0.05       0  4939.6    0.12       0
  5113.2     0.1       0  5131.8    0.05       0  5175.1     0.1       0
  5204.6    0.05       0
Bank Sta=4812,4818
Exp/Cntr=0.3,0.1

Type RM Length L Ch R = 1,232,0,0,0
BEGIN DESCRIPTION:
UNT051 IN SUCR 1.0
END DESCRIPTION:
XS GIS Cut Line= 4
      2284933.88     13402999.07      2284382.70     13403624.04
      2284808.04     13404123.17      2285155.26     13404383.58
#Sta/Elev= 30
  3925.3  305.98  4126.3  298.99  4146.2  299.45  4200.1  297.22  4225.9  296.13
  4254.3  296.61  4346.4  292.95  4367.2  293.61  4409.9  291.28  4466.8  291.27
  4501.9  289.10  4573.1  288.59  4657.5  285.92  4941.3  284.73  4988.1  283.65
  4990.8  283.15  4994.1  283.65  5005.3  285.47  5026.2  284.42  5094.2  284.69
  5224.0  286.01  5301.2  287.99  5345.7  289.04  5353.4  291.13  5380.9  289.73
  5396.7  290.19  5695.4  303.12  5760.0  304.99  5795.4  307.32  5848.4  308.12
#Mann=10,-1,0
  3925.3    0.05       0  4146.2     0.1       0  4200.1    0.05       0
  4941.3    0.12       0  4988.1    0.07       0  4994.1    0.12       0
  5094.2     0.1       0  5224.0    0.05       0  5301.2     0.1       0
  5396.7    0.05       0
Bank Sta=4988.1,4994.1
Exp/Cntr=0.3,0.1

Chan Stop Cuts=-1