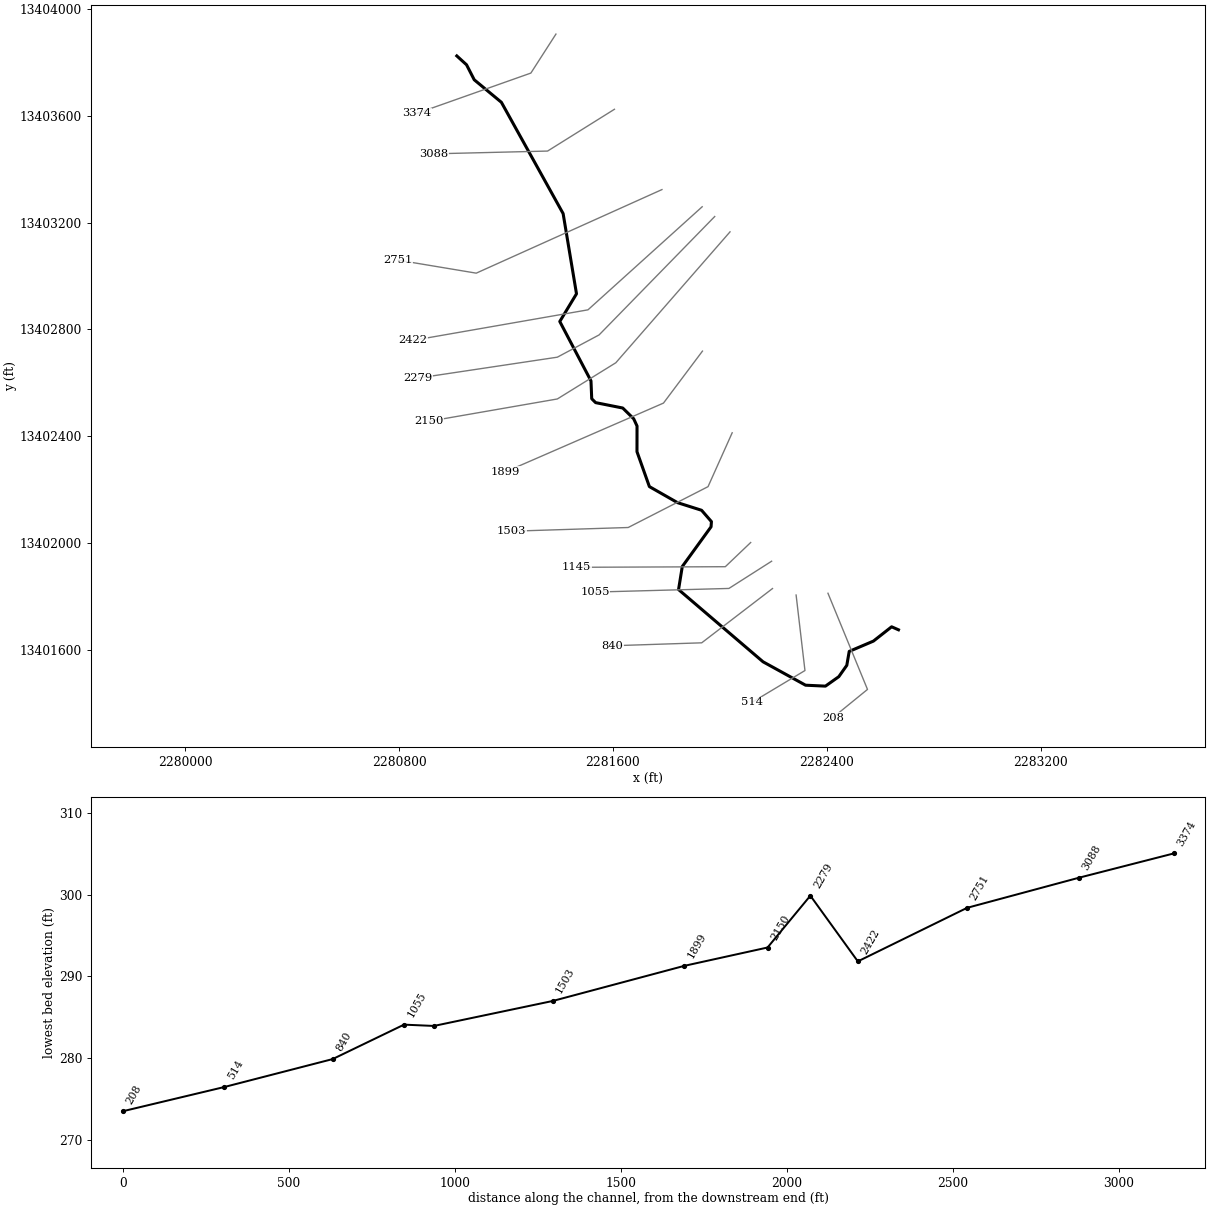
--- UNT052 IN SUCR.prj (project) ---

Proj Title=UNT052 IN SUCR Base Level Engineering
Current Plan=p01
Default Exp/Contr=0.3,0.1
English Units
Geom File=g01
Flow File=f01
Plan File=p01
BEGIN DESCRIPTION:
UNT052 IN SUCR
END DESCRIPTION:

--- UNT052 IN SUCR.p01 (plan) ---

Plan Title=Multiple Run
Short Identifier=Multiple
Geom File=g01
Flow File=f01
Subcritical Flow
K Sum by GR= 0
Std Step Tol= 0.01
Critical Tol= 0.01
Num of Std Step Trials= 20
Max Error Tol= 0.3
Flow Tol Ratio= 0.001
Split Flow NTrial= 30
Split Flow Tol= 0.02
Split Flow Ratio= 0.02
Log Output Level= 0
Friction Slope Method= 1
Unsteady Friction Slope Method= 2
Unsteady Bridges Friction Slope Method= 1
Parabolic Critical Depth
Global Vel Dist=  1 , 1 , 1
Global Log Level= 0
CheckData=True
Encroach Param= -1, 0, 0, 0
BEGIN DESCRIPTION:
Multiple Run
END DESCRIPTION:

--- UNT052 IN SUCR.f01 (steady flow) ---

Flow Title=Multiple
Number of Profiles=7
Profile Names=10-year,25-year,50-year,1pct_min,100-year,1pct_plu,500-year
River Rch & RM= UNT052 IN SUCR,Reach-1,3374
     123     163     196     173     234     316     339
Boundary for River Rch & Prof#=UNT052 IN SUCR,Reach-1,1
Up Type=0
Dn Type=3
Dn Slope=0.005
Boundary for River Rch & Prof#=UNT052 IN SUCR,Reach-1,2
Up Type=0
Dn Type=3
Dn Slope=0.005
Boundary for River Rch & Prof#=UNT052 IN SUCR,Reach-1,3
Up Type=0
Dn Type=3
Dn Slope=0.005
Boundary for River Rch & Prof#=UNT052 IN SUCR,Reach-1,4
Up Type=0
Dn Type=3
Dn Slope=0.005
Boundary for River Rch & Prof#=UNT052 IN SUCR,Reach-1,5
Up Type=0
Dn Type=3
Dn Slope=0.005
Boundary for River Rch & Prof#=UNT052 IN SUCR,Reach-1,6
Up Type=0
Dn Type=3
Dn Slope=0.005
Boundary for River Rch & Prof#=UNT052 IN SUCR,Reach-1,7
Up Type=0
Dn Type=3
Dn Slope=0.005

--- UNT052 IN SUCR.g01 (geometry) ---

Geom Title=Existing Conditions

River Reach=UNT052 IN SUCR,Reach-1
Reach XY= 30
      2281016.02     13403823.02      2281052.43     13403789.88
      2281081.17     13403733.81      2281182.71     13403649.58
      2281413.62     13403233.35      2281463.62     13402933.35
      2281401.12     13402829.88      2281517.78     13402607.66
      2281520.56     13402540.99      2281535.14     13402526.41
      2281636.53     13402506.27      2281677.51     13402465.99
      2281690.01     13402438.91      2281689.82     13402342.95
      2281736.20     13402212.41      2281841.55     13402152.32
      2281931.41     13402123.86      2281968.22     13402081.50
      2281966.84     13402062.04      2281859.19     13401913.44
      2281845.30     13401827.33      2282161.27     13401557.19
      2282320.30     13401469.69      2282394.61     13401466.22
      2282444.61     13401501.63      2282474.47     13401544.00
      2282483.50     13401596.08      2282574.02     13401634.61
      2282642.09     13401688.10      2282667.72     13401676.85

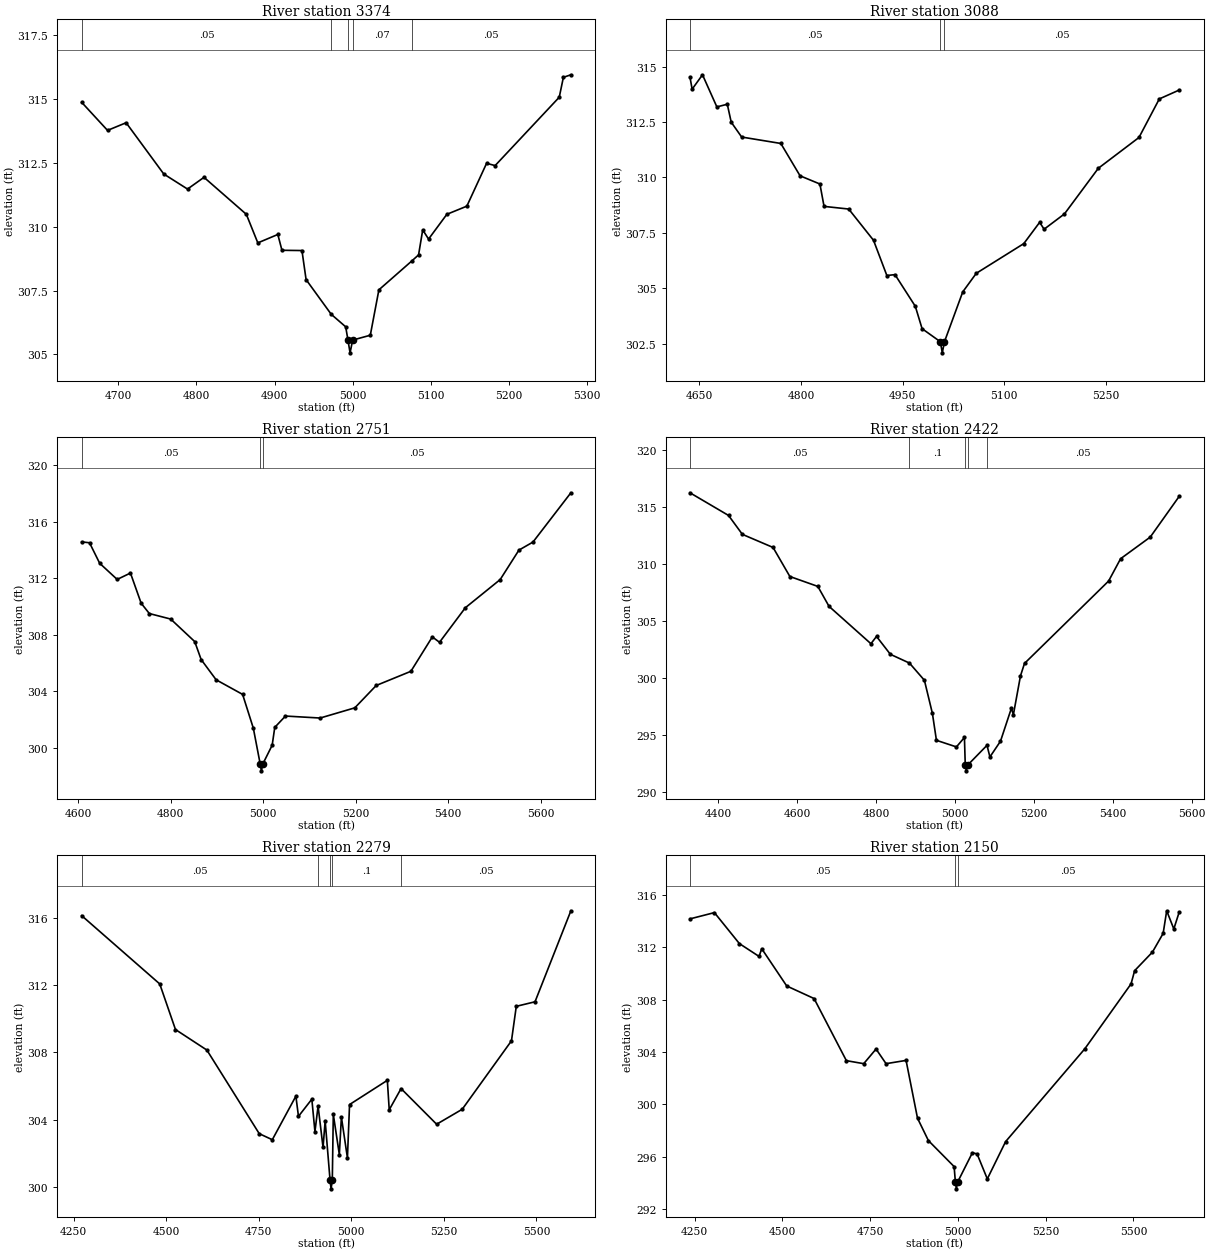
Type RM Length L Ch R = 1,3374,286,286,286
BEGIN DESCRIPTION:
UNT052 IN SUCR 6.0
END DESCRIPTION:
XS GIS Cut Line= 3
      2281386.73     13403904.69      2281293.00     13403758.88
      2280865.96     13403607.85
#Sta/Elev= 30
  4653.1  314.88  4686.2  313.78  4710.0  314.08  4758.2  312.07  4788.6  311.48
  4809.7  311.94  4863.9  310.49  4878.6  309.37  4904.2  309.70  4909.5  309.08
  4935.1  309.07  4940.4  307.93  4972.6  306.57  4991.1  306.08  4994.0  305.56
  4996.7  305.06  5000.0  305.56  5022.6  305.75  5033.6  307.53  5075.7  308.66
  5084.4  308.90  5089.7  309.88  5097.2  309.52  5120.6  310.49  5146.2  310.81
  5171.5  312.49  5182.4  312.40  5264.5  315.08  5269.8  315.86  5279.4  315.96
#Mann=5,-1,0
  4653.1    0.05       0  4972.6    0.07       0  4994.0    0.07       0
  5000.0    0.07       0  5075.7    0.05       0
Bank Sta=4994,5000
Exp/Cntr=0.3,0.1

Type RM Length L Ch R = 1,3088,337,337,337
BEGIN DESCRIPTION:
Mapping XS 2bd7f654
END DESCRIPTION:
XS GIS Cut Line= 3
      2281605.51     13403623.47      2281355.50     13403467.21
      2280928.45     13403456.79
#Sta/Elev= 30
  4636.0  314.53  4639.2  313.98  4654.5  314.63  4675.7  313.18  4691.1  313.30
  4696.9  312.49  4712.3  311.82  4770.1  311.53  4798.5  310.07  4827.8  309.70
  4833.9  308.69  4870.3  308.57  4906.9  307.16  4926.6  305.57  4938.6  305.61
  4968.6  304.18  4978.6  303.17  5005.6  302.58  5008.4  302.08  5011.6  302.58
  5038.6  304.83  5058.6  305.67  5128.7  307.01  5152.1  307.97  5158.7  307.66
  5188.7  308.35  5238.7  310.41  5298.7  311.80  5328.7  313.54  5358.0  313.94
#Mann=3,-1,0
  4636.0    0.05       0  5005.6    0.03       0  5011.6    0.05       0
Bank Sta=5005.6,5011.6
Exp/Cntr=0.3,0.1

Type RM Length L Ch R = 1,2751,329,329,329
BEGIN DESCRIPTION:
UNT052 IN SUCR 5.0
END DESCRIPTION:
XS GIS Cut Line= 3
      2281783.17     13403323.14      2281088.68     13403010.62
      2280796.97     13403059.24
#Sta/Elev= 30
  4607.7  314.56  4624.6  314.50  4646.6  313.05  4684.4  311.91  4713.1  312.36
  4736.2  310.23  4753.9  309.50  4800.1  309.11  4852.0  307.52  4865.9  306.25
  4898.3  304.82  4955.5  303.79  4978.7  301.40  4993.4  298.89  4996.1  298.39
  4999.4  298.89  5019.4  300.20  5025.0  301.46  5048.1  302.26  5123.1  302.12
  5198.0  302.84  5244.3  304.42  5319.2  305.42  5365.5  307.85  5381.1  307.47
  5436.9  309.91  5512.2  311.90  5552.7  313.98  5583.1  314.55  5665.0  318.03
#Mann=3,-1,0
  4607.7    0.05       0  4993.4    0.03       0  4999.4    0.05       0
Bank Sta=4993.4,4999.4
Exp/Cntr=0.3,0.1

Type RM Length L Ch R = 1,2422,143,143,143
BEGIN DESCRIPTION:
Mapping XS a84e5d0b
END DESCRIPTION:
XS GIS Cut Line= 3
      2281933.65     13403258.90      2281506.54     13402873.46
      2280851.46     13402759.08
#Sta/Elev= 30
  4328.1  316.24  4425.9  314.25  4461.0  312.59  4538.8  311.44  4581.4  308.89
  4652.3  308.02  4680.7  306.27  4786.9  302.99  4801.1  303.63  4836.2  302.06
  4884.6  301.29  4922.5  299.78  4942.8  296.87  4953.0  294.51  5003.7  293.93
  5024.0  294.76  5026.1  292.33  5028.8  291.83  5032.1  292.33  5081.2  294.07
  5088.6  293.05  5115.4  294.43  5143.0  297.32  5148.1  296.76  5166.1  300.17
  5176.3  301.26  5389.5  308.49  5419.9  310.45  5495.1  312.35  5568.4  315.92
#Mann=5,-1,0
  4328.1    0.05       0  4884.6     0.1       0  5026.1    0.07       0
  5032.1     0.1       0  5081.2    0.05       0
Bank Sta=5026.1,5032.1
Exp/Cntr=0.3,0.1

Type RM Length L Ch R = 1,2279,129,129,129
BEGIN DESCRIPTION:
UNT052 IN SUCR 4.0
END DESCRIPTION:
XS GIS Cut Line= 4
      2281980.47     13403222.39      2281548.20     13402779.71
      2281391.95     13402696.38      2280871.88     13402618.37
#Sta/Elev= 30
  4271.5  316.12  4482.4  312.06  4524.9  309.35  4609.7  308.13  4751.2  303.16
  4786.5  302.80  4850.2  305.39  4857.2  304.19  4893.3  305.21  4901.7  303.28
  4910.2  304.80  4923.6  302.34  4929.3  303.92  4942.6  300.38  4945.3  299.88
  4948.6  300.38  4951.3  304.31  4967.6  301.92  4973.2  304.14  4989.5  301.72
  4995.2  304.89  5097.3  306.33  5102.4  304.58  5134.4  305.84  5230.5  303.72
  5299.6  304.61  5432.7  308.68  5445.7  310.73  5496.3  311.00  5593.2  316.41
#Mann=5,-1,0
  4271.5    0.05       0  4910.2     0.1       0  4942.6    0.07       0
  4948.6     0.1       0  5134.4    0.05       0
Bank Sta=4942.6,4948.6
Exp/Cntr=0.3,0.1

Type RM Length L Ch R = 1,2150,251,251,251
BEGIN DESCRIPTION:
Mapping XS 3fad9aa5
END DESCRIPTION:
XS GIS Cut Line= 4
      2282037.78     13403165.11      2281610.70     13402675.54
      2281391.95     13402540.13      2280912.79     13402456.79
#Sta/Elev= 30
  4237.0  314.17  4306.6  314.65  4377.8  312.28  4433.8  311.30  4441.4  311.89
  4512.6  309.04  4590.5  308.08  4682.5  303.33  4731.9  303.10  4767.0  304.22
  4795.5  303.10  4852.5  303.35  4885.1  298.93  4916.1  297.22  4989.4  295.23
  4993.0  294.03  4995.8  293.53  4999.0  294.03  5041.4  296.29  5054.8  296.20
  5083.9  294.29  5136.0  297.14  5361.4  304.23  5493.3  309.20  5503.5  310.21
  5554.2  311.63  5584.7  313.06  5594.8  314.79  5615.1  313.40  5630.3  314.68
#Mann=3,-1,0
  4237.0    0.05       0  4993.0    0.03       0  4999.0    0.05       0
Bank Sta=4993,4999
Exp/Cntr=0.3,0.1

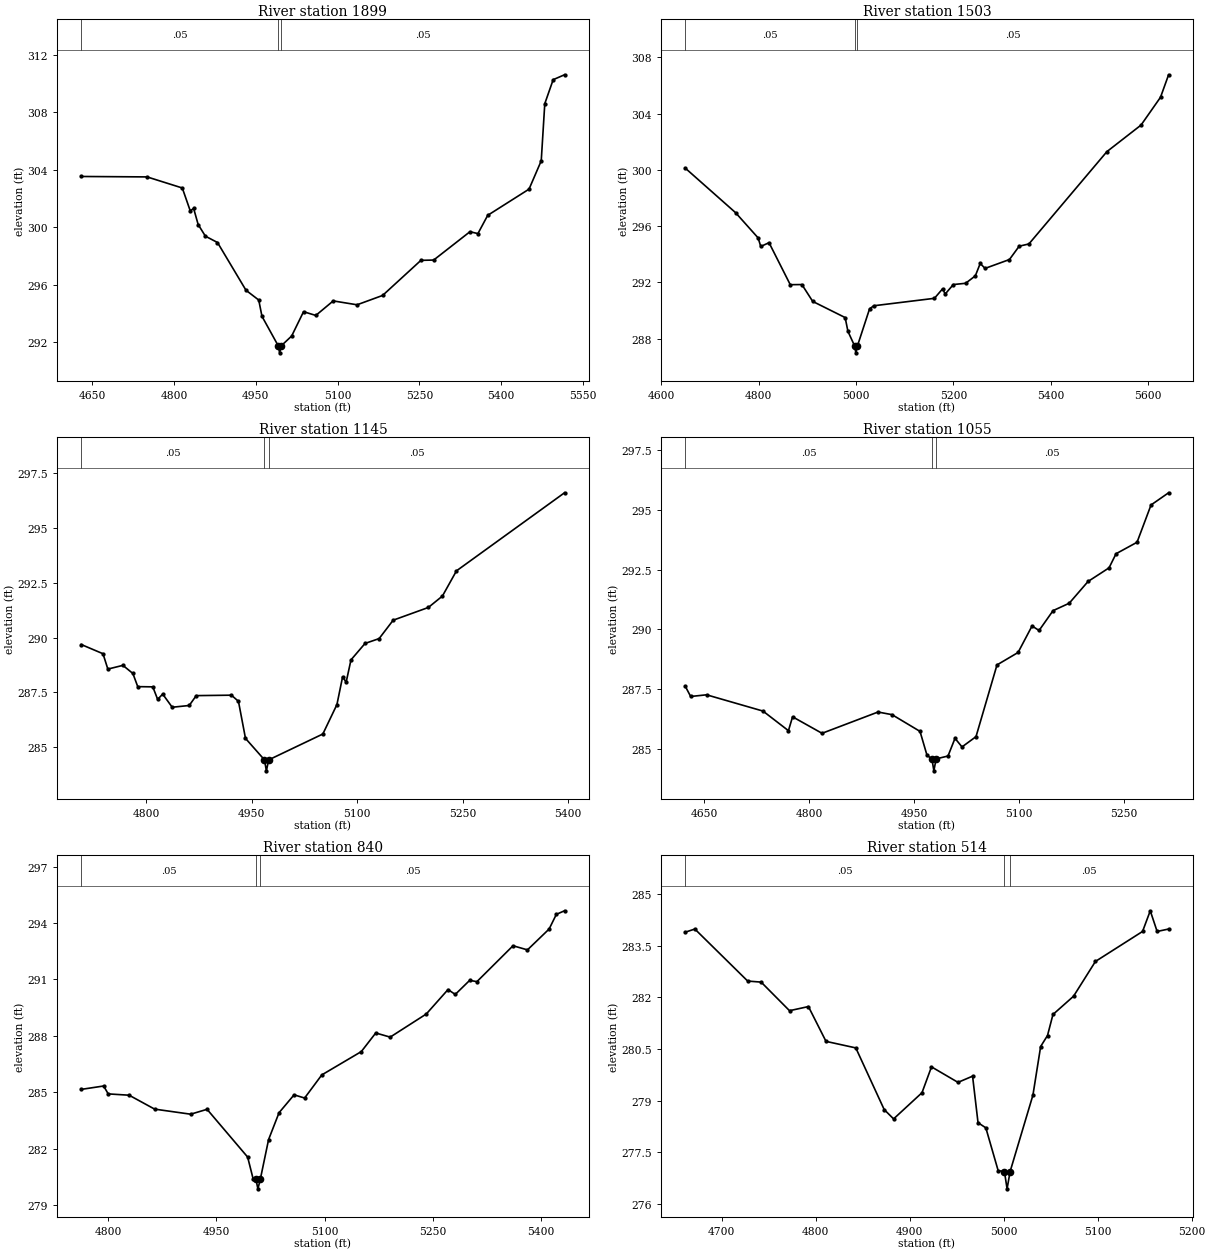
Type RM Length L Ch R = 1,1899,396,396,396
BEGIN DESCRIPTION:
UNT052 IN SUCR 3.0
END DESCRIPTION:
XS GIS Cut Line= 3
      2281934.71     13402719.13      2281788.89     13402524.71
      2281198.61     13402267.77
#Sta/Elev= 30
  4629.6  303.54  4750.4  303.51  4815.0  302.74  4829.6  301.15  4835.8  301.32
  4844.1  300.20  4857.4  299.39  4879.6  298.95  4931.9  295.63  4955.3  294.95
  4961.2  293.82  4990.9  291.78  4993.6  291.28  4996.9  291.78  5015.7  292.45
  5037.5  294.14  5060.0  293.88  5092.0  294.89  5135.7  294.62  5182.6  295.27
  5252.9  297.71  5276.3  297.73  5342.9  299.70  5357.5  299.57  5375.5  300.84
  5451.3  302.66  5473.7  304.63  5480.2  308.60  5495.6  310.27  5516.4  310.61
#Mann=3,-1,0
  4629.6    0.05       0  4990.9    0.03       0  4996.9    0.05       0
Bank Sta=4990.9,4996.9
Exp/Cntr=0.3,0.1

Type RM Length L Ch R = 1,1503,358,358,358
BEGIN DESCRIPTION:
UNT052 IN SUCR 2.0
END DESCRIPTION:
XS GIS Cut Line= 4
      2282045.84     13402413.62      2281955.56     13402212.21
      2281656.95     13402059.43      2281221.11     13402045.60
#Sta/Elev= 30
  4649.6  300.12  4752.6  296.96  4799.0  295.16  4804.4  294.55  4821.4  294.82
  4865.0  291.83  4888.9  291.84  4911.1  290.64  4977.7  289.49  4983.4  288.51
  4997.0  287.48  4999.7  286.98  5003.0  287.48  5027.8  290.11  5036.4  290.33
  5161.0  290.86  5177.6  291.53  5183.2  291.17  5199.8  291.84  5225.0  291.93
  5245.0  292.46  5255.0  293.34  5265.0  292.99  5315.0  293.62  5335.0  294.57
  5355.0  294.73  5515.1  301.30  5585.2  303.19  5625.2  305.17  5641.8  306.77
#Mann=3,-1,0
  4649.6    0.05       0  4997.0    0.03       0  5003.0    0.05       0
Bank Sta=4997,5003
Exp/Cntr=0.3,0.1

Type RM Length L Ch R = 1,1145,90,90,90
BEGIN DESCRIPTION:
Mapping XS f625f2e2
END DESCRIPTION:
XS GIS Cut Line= 3
      2282115.00     13402003.27      2282020.14     13401912.82
      2281464.11     13401910.62
#Sta/Elev= 30
  4707.6  289.68  4738.5  289.26  4745.4  288.56  4766.8  288.73  4781.0  288.36
  4787.9  287.76  4809.3  287.75  4816.2  287.18  4823.4  287.42  4836.9  286.82
  4861.1  286.90  4871.1  287.35  4921.1  287.37  4931.1  287.09  4941.1  285.40
  4968.1  284.42  4970.8  283.92  4974.1  284.42  5051.1  285.60  5071.1  286.94
  5079.2  288.21  5084.2  287.96  5091.1  288.98  5111.1  289.73  5131.1  289.95
  5151.1  290.79  5201.1  291.37  5221.1  291.89  5241.1  293.04  5394.7  296.60
#Mann=3,-1,0
  4707.6    0.05       0  4968.1    0.03       0  4974.1    0.05       0
Bank Sta=4968.1,4974.1
Exp/Cntr=0.3,0.1

Type RM Length L Ch R = 1,1055,215,215,215
BEGIN DESCRIPTION:
Mapping XS 1517ed7c
END DESCRIPTION:
XS GIS Cut Line= 3
      2282193.29     13401933.33      2282033.61     13401831.54
      2281532.66     13401817.95
#Sta/Elev= 30
  4623.2  287.61  4630.8  287.19  4653.5  287.26  4734.1  286.58  4770.5  285.76
  4776.4  286.34  4818.5  285.65  4898.5  286.54  4918.5  286.43  4958.5  285.73
  4968.5  284.73  4975.5  284.58  4978.3  284.08  4981.5  284.58  4998.5  284.70
  5008.5  285.44  5018.5  285.08  5038.5  285.51  5068.5  288.51  5098.6  289.03
  5118.6  290.14  5128.6  289.95  5148.6  290.78  5171.7  291.09  5198.6  292.00
  5228.6  292.57  5238.6  293.16  5268.6  293.64  5288.6  295.20  5313.7  295.71
#Mann=3,-1,0
  4623.2    0.05       0  4975.5    0.03       0  4981.5    0.05       0
Bank Sta=4975.5,4981.5
Exp/Cntr=0.3,0.1

Type RM Length L Ch R = 1,840,326,326,326
BEGIN DESCRIPTION:
Mapping XS 635e7290
END DESCRIPTION:
XS GIS Cut Line= 3
      2282196.64     13401831.18      2281931.88     13401628.20
      2281596.47     13401617.17
#Sta/Elev= 30
  4763.0  285.15  4794.0  285.33  4800.3  284.91  4829.3  284.84  4864.6  284.10
  4914.5  283.83  4937.2  284.09  4993.4  281.55  5001.0  280.39  5004.9  280.36
  5007.6  279.86  5010.9  280.36  5022.4  282.48  5036.9  283.91  5057.7  284.86
  5072.3  284.69  5096.1  285.92  5150.8  287.16  5170.8  288.15  5190.8  287.93
  5240.8  289.16  5270.9  290.46  5280.9  290.20  5300.9  290.95  5310.9  290.88
  5360.9  292.79  5380.9  292.57  5410.9  293.68  5420.9  294.46  5432.2  294.65
#Mann=3,-1,0
  4763.0    0.05       0  5004.9    0.03       0  5010.9    0.05       0
Bank Sta=5004.9,5010.9
Exp/Cntr=0.3,0.1

Type RM Length L Ch R = 1,514,306,306,306
BEGIN DESCRIPTION:
Mapping XS 45d4be07
END DESCRIPTION:
XS GIS Cut Line= 3
      2282284.90     13401806.88      2282317.99     13401524.50
      2282121.04     13401406.33
#Sta/Elev= 30
  4661.4  283.89  4671.5  283.98  4727.7  282.47  4742.0  282.44  4772.2  281.61
  4792.3  281.73  4811.0  280.72  4842.7  280.53  4872.9  278.74  4882.9  278.47
  4913.1  279.23  4923.2  279.98  4951.4  279.53  4966.9  279.71  4972.7  278.36
  4981.0  278.21  4994.1  276.97  5000.8  276.94  5003.6  276.44  5006.8  276.94
  5031.1  279.16  5039.3  280.57  5046.6  280.89  5052.4  281.50  5074.3  282.03
  5097.6  283.04  5147.7  283.91  5155.9  284.51  5163.2  283.91  5175.4  283.98
#Mann=3,-1,0
  4661.4    0.05       0  5000.8    0.03       0  5006.8    0.05       0
Bank Sta=5000.8,5006.8
Exp/Cntr=0.3,0.1

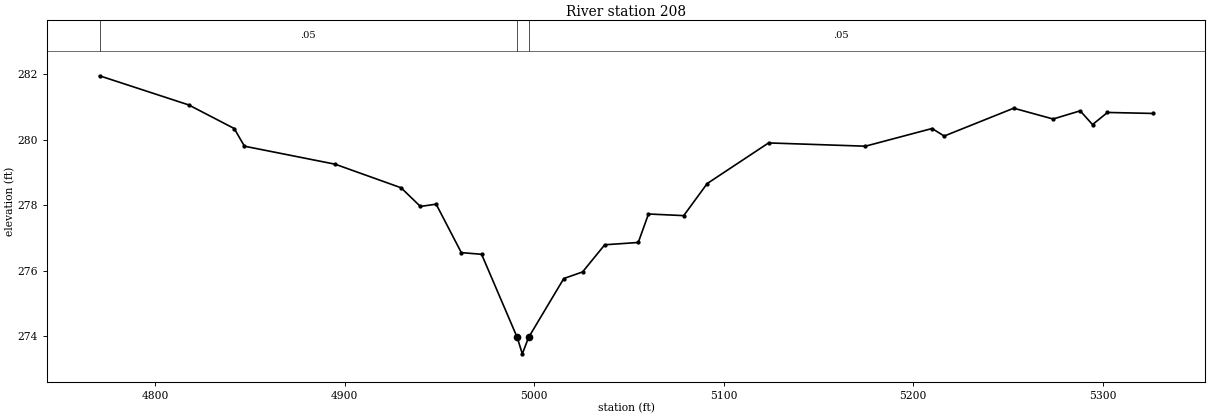
Type RM Length L Ch R = 1,208,0,0,0
BEGIN DESCRIPTION:
UNT052 IN SUCR 1.0
END DESCRIPTION:
XS GIS Cut Line= 3
      2282404.04     13401813.54      2282551.87     13401453.90
      2282422.20     13401348.41
#Sta/Elev= 30
  4770.5  281.96  4817.6  281.07  4841.6  280.35  4847.0  279.81  4894.9  279.26
  4929.7  278.54  4939.9  277.97  4948.2  278.04  4961.5  276.56  4972.2  276.51
  4991.0  273.97  4993.7  273.47  4997.0  273.97  5015.6  275.77  5025.5  275.97
  5037.2  276.80  5054.9  276.87  5060.3  277.74  5078.9  277.69  5091.3  278.67
  5123.7  279.91  5174.8  279.81  5210.0  280.35  5216.4  280.12  5253.1  280.97
  5273.9  280.64  5288.2  280.89  5294.7  280.47  5302.6  280.84  5326.5  280.81
#Mann=3,-1,0
  4770.5    0.05       0  4991.0    0.03       0  4997.0    0.05       0
Bank Sta=4991,4997
Exp/Cntr=0.3,0.1

Chan Stop Cuts=-1