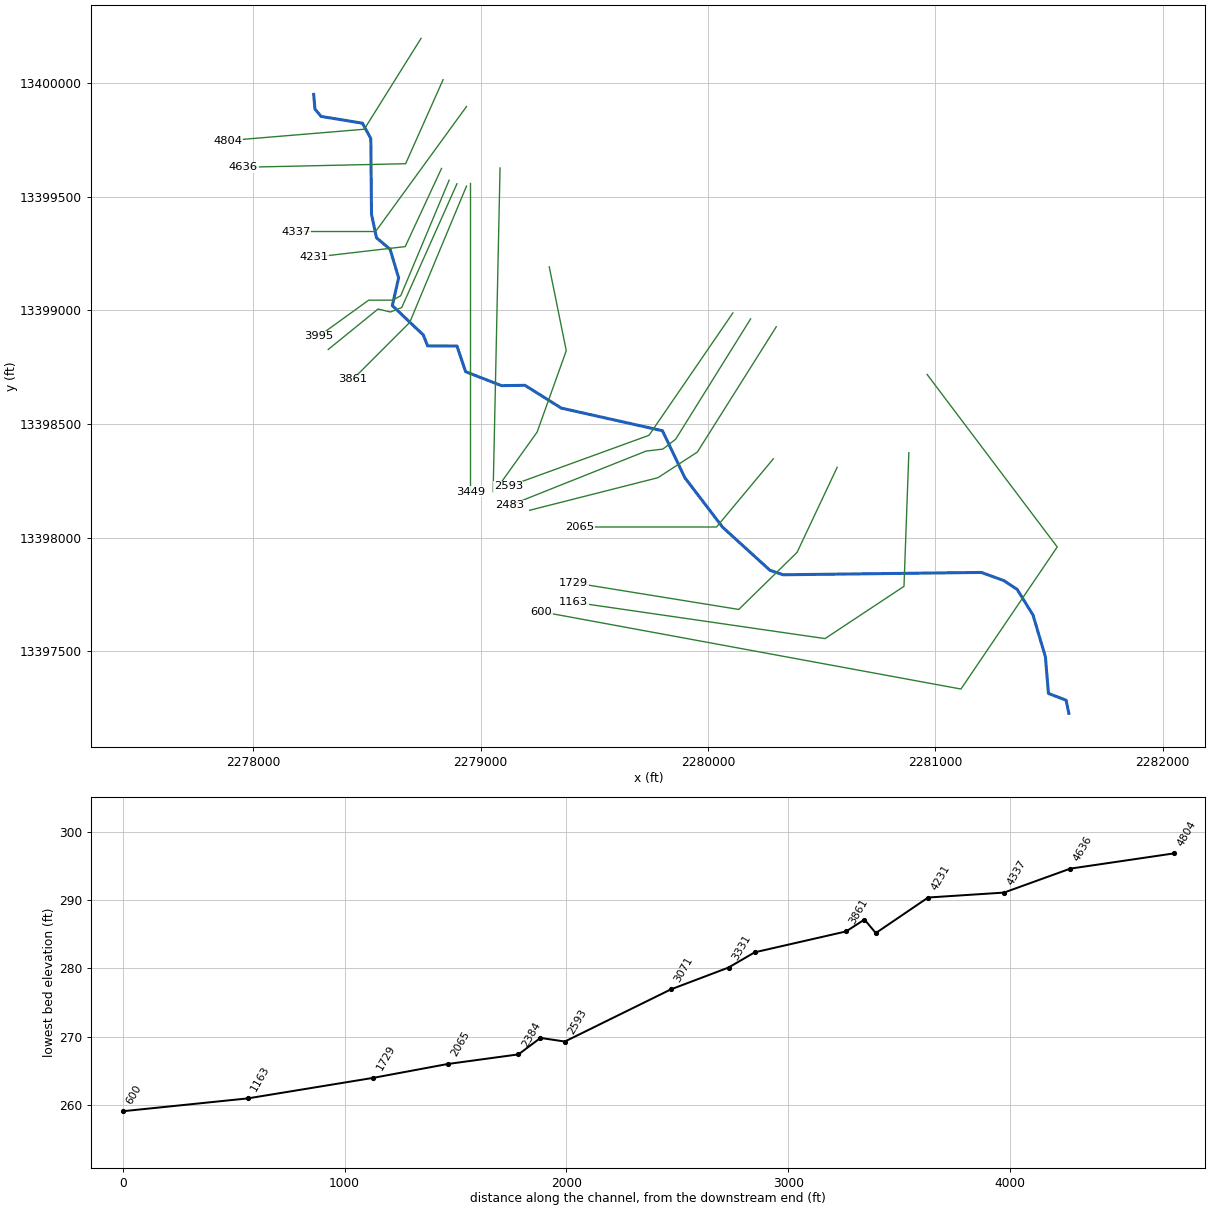
--- UNT053 IN SUCR.prj (project) ---

Proj Title=UNT053 IN SUCR Base Level Engineering
Current Plan=p01
Default Exp/Contr=0.3,0.1
English Units
Geom File=g01
Flow File=f01
Plan File=p01
Y Axis Title=Elevation
X Axis Title(PF)=Main Channel Distance
X Axis Title(XS)=Station
BEGIN DESCRIPTION:
UNT053 IN SUCR
END DESCRIPTION:
DSS Export Rating Curves= 0
DSS Export Rating Curve Sorted= 0
DSS Export Volume Flow Curves= 0
DXF OffsetX= 0
DXF OffsetY= 0
DXF ScaleX= 1
DXF ScaleY= 10

--- UNT053 IN SUCR.p01 (plan) ---

Plan Title=Multiple Run
Short Identifier=Multiple
Geom File=g01
Flow File=f01
Subcritical Flow
K Sum by GR= 0
Std Step Tol= 0.01
Critical Tol= 0.01
Num of Std Step Trials= 20
Max Error Tol= 0.3
Flow Tol Ratio= 0.001
Split Flow NTrial= 30
Split Flow Tol= 0.02
Split Flow Ratio= 0.02
Log Output Level= 0
Friction Slope Method= 1
Unsteady Friction Slope Method= 2
Unsteady Bridges Friction Slope Method= 1
Parabolic Critical Depth
Global Vel Dist=  1 , 1 , 1
Global Log Level= 0
CheckData=True
Encroach Param= -1, 0, 0, 0
BEGIN DESCRIPTION:
Multiple Run
END DESCRIPTION:

--- UNT053 IN SUCR.f01 (steady flow) ---

Flow Title=Multiple
Program Version=4.10
Number of Profiles= 7
Profile Names=10-year,25-year,50-year,1pct_min,100-year,1pct_plu,500-year
River Rch & RM=UNT053 IN SUCR,Reach-1         ,4804
      88     114     135     117     159     214     223
River Rch & RM=UNT053 IN SUCR,Reach-1         ,3331
     165     223     270     241     325     440     479
Boundary for River Rch & Prof#=UNT053 IN SUCR,Reach-1         , 1
Up Type= 0
Dn Type= 3
Dn Slope=0.0036
Boundary for River Rch & Prof#=UNT053 IN SUCR,Reach-1         , 2
Up Type= 0
Dn Type= 3
Dn Slope=0.0036
Boundary for River Rch & Prof#=UNT053 IN SUCR,Reach-1         , 3
Up Type= 0
Dn Type= 3
Dn Slope=0.0036
Boundary for River Rch & Prof#=UNT053 IN SUCR,Reach-1         , 4
Up Type= 0
Dn Type= 3
Dn Slope=0.0036
Boundary for River Rch & Prof#=UNT053 IN SUCR,Reach-1         , 5
Up Type= 0
Dn Type= 3
Dn Slope=0.0036
Boundary for River Rch & Prof#=UNT053 IN SUCR,Reach-1         , 6
Up Type= 0
Dn Type= 3
Dn Slope=0.0036
Boundary for River Rch & Prof#=UNT053 IN SUCR,Reach-1         , 7
Up Type= 0
Dn Type= 3
Dn Slope=0.0036
DSS Import GetInterval= 0
DSS Import GetPeak= 0
DSS Import FillOption= 0

--- UNT053 IN SUCR.g01 (geometry) ---

Geom Title=Existing Conditions
Program Version=4.10

River Reach=UNT053 IN SUCR  ,Reach-1
Reach XY= 30
      2278265.27     13399950.22      2278270.96     13399885.24
      2278298.32     13399853.13      2278480.08     13399823.39
      2278516.62     13399755.65      2278519.69     13399422.31
      2278541.68      13399319.3      2278601.66      13399268.6
      2278638.99     13399142.73      2278611.33     13399021.01
      2278747.41      13398891.8      2278766.57     13398843.83
      2278895.61     13398843.11      2278933.81      13398730.1
      2279091.69     13398668.76      2279194.73     13398670.22
      2279354.37     13398570.03      2279799.83     13398470.35
      2279898.58     13398263.33      2280064.65     13398045.72
      2280272.85      13397856.3      2280331.18     13397836.67
      2281202.75     13397846.93      2281300.31     13397811.57
      2281359.94     13397772.85      2281429.87     13397660.01
      2281484.71     13397475.73      2281497.99     13397314.55
      2281575.76     13397284.71      2281587.72     13397226.85

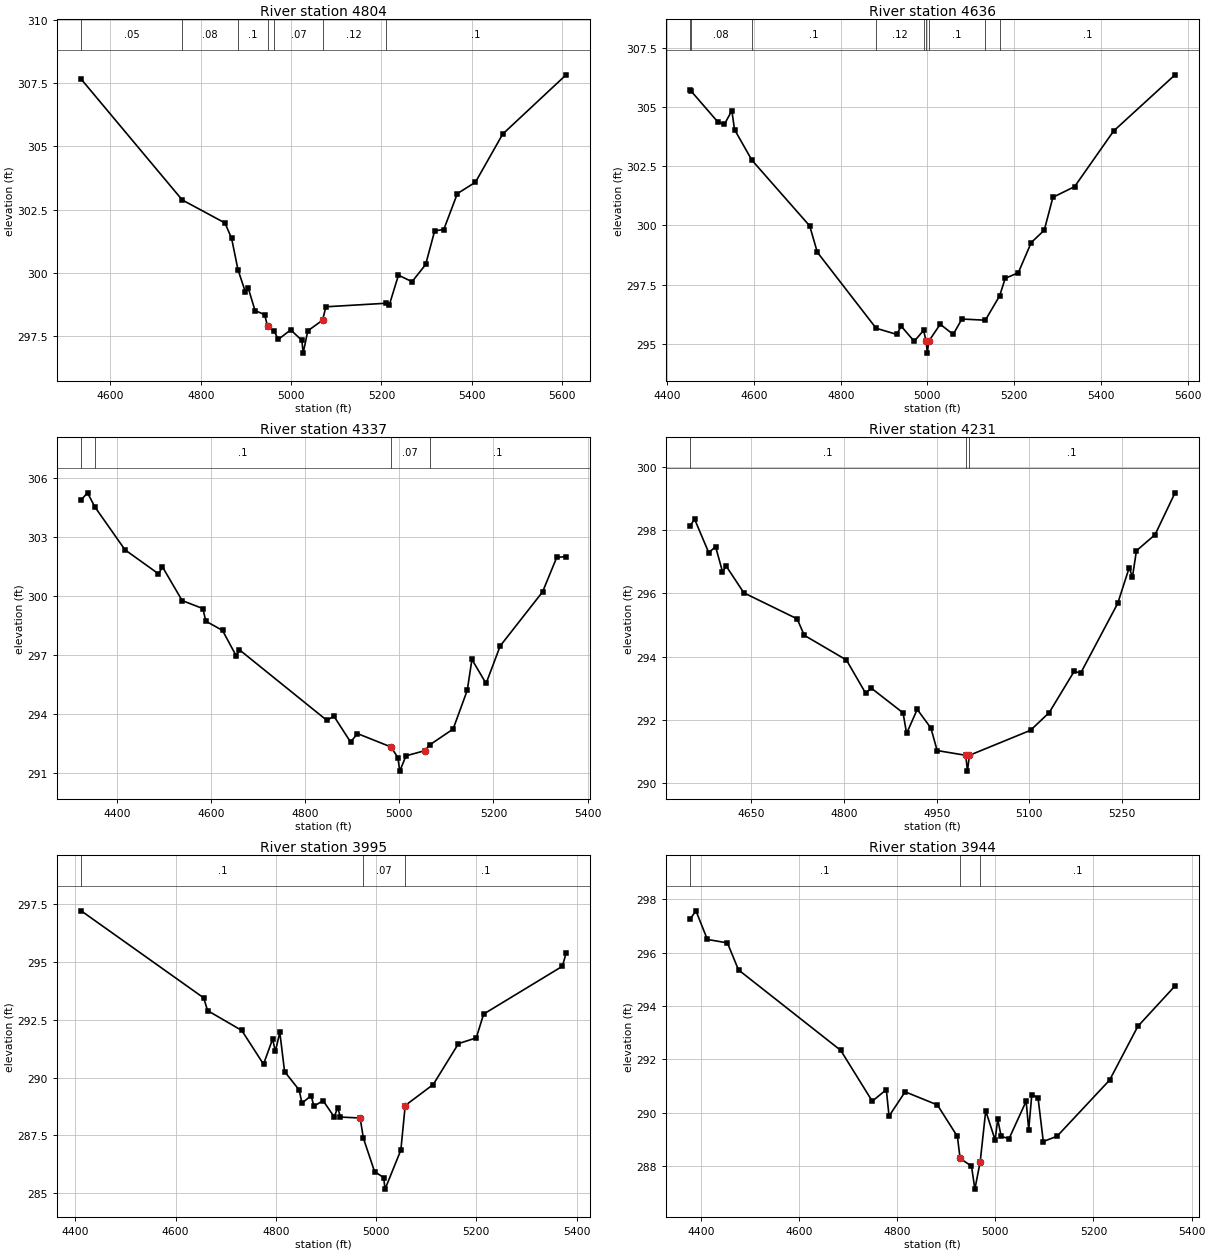
Type RM Length L Ch R = 1 ,4804    ,467,467,467
BEGIN DESCRIPTION:
UNT053 IN SUCR 8.0
END DESCRIPTION:
XS GIS Cut Line= 3
       2278737.7     13400196.82      2278487.72     13399796.85
      2277887.76     13399746.86
#Sta/Elev= 30
  4535.1  307.66  4758.8  302.89  4853.5  301.98  4868.2  301.37  4882.2  300.14
  4898.9  299.24  4904.8  299.42  4920.1  298.52  4941.3  298.36  4947.8   297.9
  4949.1  297.86  4962.5  297.71  4971.4  297.38  4999.1  297.76  5023.8  297.34
  5026.6  296.84  5036.9  297.72  5069.5  298.14    5077  298.67  5210.5  298.81
  5217.5  298.75  5237.6  299.92  5267.7  299.66  5297.8  300.34  5317.8  301.67
  5337.9  301.72    5368  303.14  5408.1  303.59  5468.4  305.49  5608.8  307.83
#Mann= 7 ,-1 , 0
  4535.1     .05       0  4758.8     .08       0  4882.2      .1       0
  4949.1     .12       0  4962.5     .07       0  5069.5     .12       0
  5210.5      .1       0
Bank Sta=4947.8,5069.5
XS Rating Curve= 0 ,0
Exp/Cntr=0.3,0.1

Type RM Length L Ch R = 1 ,4636    ,299,299,299
BEGIN DESCRIPTION:
UNT053 IN SUCR 7.2
END DESCRIPTION:
XS GIS Cut Line= 3
      2278834.68     13400014.93      2278669.75     13399645.15
      2277956.22     13399629.52
#Sta/Elev= 30
  4452.5  305.74  4454.1  305.69  4516.1  304.38  4531.7  304.27  4548.9  304.85
    4555  304.05    4595  302.76  4728.5  299.98    4746  298.87  4881.7  295.66
  4929.4   295.4  4939.4  295.75  4969.5  295.11  4991.2  295.57    4997  295.11
  4999.8  294.61    5003  295.11  5029.5  295.83  5059.5   295.4  5079.5  296.05
  5133.6     296  5166.6  297.03  5179.5  297.77  5209.5     298  5239.5  299.28
  5269.5   299.8  5289.5  301.19  5339.5  301.64  5429.6  303.99  5571.1  306.36
#Mann= 9 ,-1 , 0
  4452.5     .05       0  4454.1     .08       0    4595      .1       0
  4881.7     .12       0  4991.2      .1       0    4997     .07       0
    5003      .1       0  5133.6     .12       0  5166.6      .1       0
Bank Sta=4997,5003
XS Rating Curve= 0 ,0
Exp/Cntr=0.3,0.1

Type RM Length L Ch R = 1 ,4337    ,342,342,342
BEGIN DESCRIPTION:
UNT053 IN SUCR 7.0
END DESCRIPTION:
XS GIS Cut Line= 3
       2278937.7     13399896.83      2278537.72     13399346.85
      2278187.76     13399346.85
#Sta/Elev= 30
  4324.3   304.9  4337.8  305.26  4353.2  304.55  4417.4  302.36  4488.5  301.14
    4497  301.49  4538.7  299.78  4582.8  299.37    4589  298.73  4624.5  298.26
  4653.9  296.95  4660.1  297.28  4846.3  293.68    4861   293.9  4896.5  292.58
  4911.2  293.01  4982.3  292.33    4997  291.79    5001   291.1  5014.3  291.88
  5054.3  292.14  5064.3  292.43  5114.3  293.24  5144.3  295.21  5154.3  296.78
  5184.3  295.56  5214.3  297.47  5304.3  300.22  5334.3  301.97  5354.3  302.02
#Mann= 4 ,-1 , 0
  4324.3     .08       0  4353.2      .1       0  4982.3     .07       0
  5064.3      .1       0
Bank Sta=4982.3,5054.3
XS Rating Curve= 0 ,0
Exp/Cntr=0.3,0.1

Type RM Length L Ch R = 1 ,4231    ,236,236,236
BEGIN DESCRIPTION:
UNT053 IN SUCR 7.0
END DESCRIPTION:
XS GIS Cut Line= 3
      2278827.74     13399624.33      2278668.01     13399280.56
       2278265.7     13399233.71
#Sta/Elev= 30
  4551.3  298.12  4558.6  298.34  4581.5  297.28  4592.6  297.47  4603.7  296.68
  4609.9  296.85  4638.3  296.01  4724.4  295.19    4736  294.67  4804.1  293.89
  4835.2  292.84  4844.4     293  4895.7  292.22  4901.4  291.57  4918.6  292.33
  4940.7  291.74  4950.8  291.03    4997  290.88  4999.8  290.38    5003  290.88
  5101.8  291.67    5132  292.23  5172.3  293.53    5183  293.48  5242.8  295.68
  5261.4  296.81  5266.5   296.5    5273  297.34  5303.2  297.85  5335.4  299.17
#Mann= 3 ,-1 , 0
  4551.3      .1       0    4997     .07       0    5003      .1       0
Bank Sta=4997,5003
XS Rating Curve= 0 ,0
Exp/Cntr=0.3,0.1

Type RM Length L Ch R = 1 ,3995    ,51,51,51
BEGIN DESCRIPTION:
Mapping XS e4050dc0
END DESCRIPTION:
XS GIS Cut Line= 6
      2278861.01     13399572.29      2278648.32     13399064.43
       2278613.6      13399044.9       2278570.2      13399044.9
      2278507.26      13399044.9      2278288.09     13398886.49
#Sta/Elev= 30
  4411.8  297.22  4656.2  293.45  4663.9   292.9  4732.1  292.04  4775.5  290.58
  4793.7  291.67  4799.1  291.13    4808  291.96  4817.5  290.26  4846.7  289.46
  4852.1  288.89  4870.5  289.22  4875.9  288.76  4894.3     289  4916.4   288.3
  4923.5  288.69  4928.9  288.29  4968.2  288.25  4974.6  287.38    4997  285.93
  5015.1  285.67  5017.9  285.17  5049.4  286.86  5058.1  288.79    5114   289.7
  5164.3  291.47  5199.8  291.72  5214.5  292.75  5371.6  294.82    5379  295.39
#Mann= 3 ,-1 , 0
  4411.8      .1       0  4974.6     .07       0  5058.1      .1       0
Bank Sta=4968.2,5058.1
XS Rating Curve= 0 ,0
Exp/Cntr=0.3,0.1

Type RM Length L Ch R = 1 ,3944    ,83,83,83
BEGIN DESCRIPTION:
Mapping XS 427c7776
END DESCRIPTION:
XS GIS Cut Line= 5
       2278895.7     13399557.01      2278652.66     13399012.35
      2278602.75     13398992.82      2278548.49     13399005.84
      2278329.35     13398827.92
#Sta/Elev= 30
    4378  297.25    4390  297.56  4413.2  296.49  4454.1  296.36  4476.7  295.35
    4685  292.34  4749.2  290.44  4777.9  290.87  4783.4  289.88  4816.2  290.79
  4881.9   290.3  4922.7  289.12  4928.2   288.3  4951.4  288.01  4958.3  287.15
  4969.2  288.18  4980.4  290.08  4999.5  288.99  5004.9  289.76  5011.9  289.12
    5028  289.04  5062.8  290.44    5068  289.37  5074.3  290.68    5087  290.57
  5097.7  288.93  5125.9  289.13  5232.9  291.23  5290.4  293.24  5366.1  294.75
#Mann= 3 , 0 , 0
    4378      .1       0  4928.2     .07       0  4969.2      .1       0
Bank Sta=4928.2,4969.2
XS Rating Curve= 0 ,0
Exp/Cntr=0.3,0.1

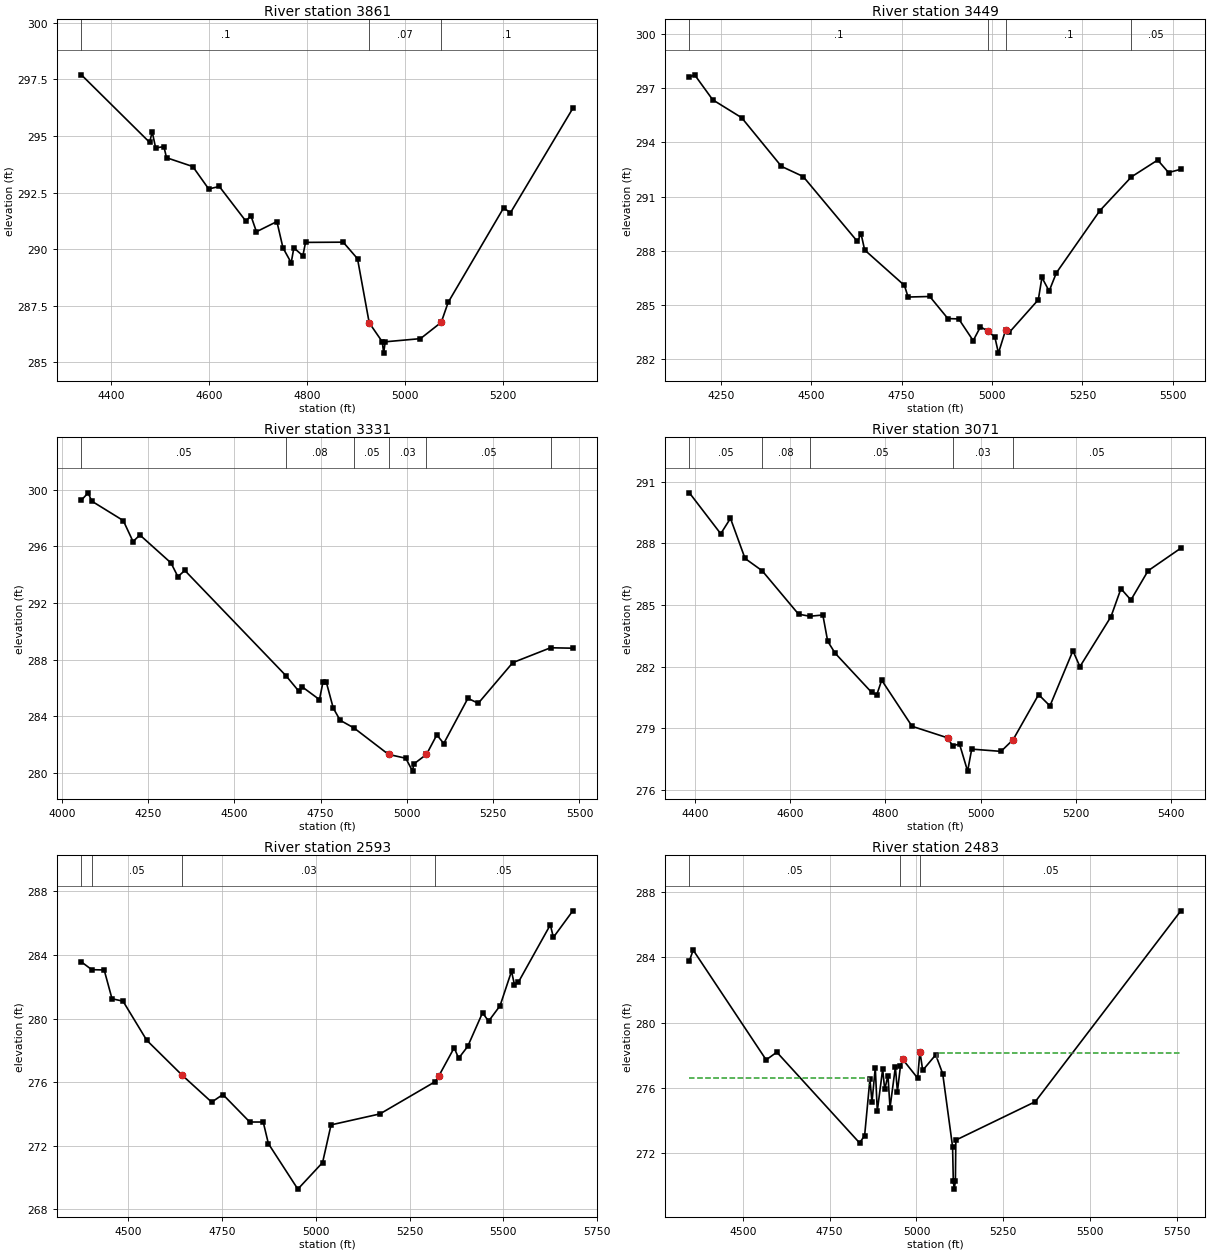
Type RM Length L Ch R = 1 ,3861    ,412,412,412
BEGIN DESCRIPTION:
UNT053 IN SUCR 6.0
END DESCRIPTION:
XS GIS Cut Line= 3
      2278937.74      13399546.9      2278687.72     13398946.85
      2278437.72     13398696.86
#Sta/Elev= 30
  4338.5   297.7  4477.8  294.72  4483.2  295.18  4490.2  294.47    4507  294.53
  4512.4  294.04    4566  293.65  4598.5  292.66  4620.2  292.77  4674.4  291.24
  4684.7  291.48    4696  290.77  4737.8  291.22  4750.2  290.06    4767   289.4
  4772.4  290.06  4790.8  289.71  4796.3   290.3  4873.2  290.31  4902.4  289.58
  4926.3  286.75    4953  285.91  4955.8  285.41    4959  285.91    5031  286.05
  5073.4  286.77  5087.5  287.65  5200.7  291.82  5214.8  291.61  5342.1  296.22
#Mann= 3 , 0 , 0
  4338.5      .1       0  4926.3     .07       0  5073.4      .1       0
Bank Sta=4926.3,5073.4
XS Rating Curve= 0 ,0
Exp/Cntr=0.3,0.1

Type RM Length L Ch R = 1 ,3449    ,118,118,118
BEGIN DESCRIPTION:
Mapping XS c770a5c9
END DESCRIPTION:
XS GIS Cut Line= 2
      2278955.03     13399561.38      2278955.03     13398202.88
#Sta/Elev= 30
  4163.4  297.61  4177.9  297.73  4227.9  296.35  4307.9  295.36  4417.9  292.67
  4477.9  292.11  4627.9  288.52  4637.9  288.95  4647.9  288.05  4757.9  286.09
  4767.9  285.45  4827.9  285.48  4877.9  284.26  4907.9  284.24  4947.9  283.04
  4967.9   283.8  4987.9  283.58  5007.9  283.23  5017.7  282.35  5037.9  283.65
  5047.9   283.5  5127.9   285.3  5137.9  286.53  5157.9  285.78  5177.9  286.79
  5297.9  290.22  5385.3  292.09  5457.9  293.02  5487.9  292.33  5521.9  292.51
#Mann= 4 ,-1 , 0
  4163.4      .1       0  4987.9     .07       0  5037.9      .1       0
  5385.3     .05       0
Bank Sta=4987.9,5037.9
XS Rating Curve= 0 ,0
Exp/Cntr=0.3,0.1

Type RM Length L Ch R = 1 ,3331    ,260,260,260
BEGIN DESCRIPTION:
UNT053 IN SUCR 5.0
END DESCRIPTION:
XS GIS Cut Line= 2
      2279085.24     13399626.51      2279054.86     13398202.93
#Sta/Elev= 30
  4056.8  299.25  4076.5  299.77  4086.5  299.19  4178.2  297.81  4206.5  296.33
  4226.5  296.79  4316.5  294.82  4336.5  293.85  4356.5  294.29  4649.5  286.86
  4686.6  285.77  4696.6  286.07  4746.6  285.17  4756.6  286.38  4766.6  286.39
  4786.6  284.57  4806.6  283.71  4847.1  283.16  4946.7   281.3  4996.7  281.03
  5016.4  280.12  5019.7  280.62  5056.7   281.3  5086.7  282.68  5106.7  282.07
  5176.7  285.26  5206.7  284.91  5306.7  287.78  5416.2  288.83  5480.7   288.8
#Mann= 6 ,-1 , 0
  4056.8     .05       0  4649.5     .08       0  4847.1     .05       0
  4946.7     .03       0  5056.7     .05       0  5416.2     .08       0
Bank Sta=4946.7,5056.7
XS Rating Curve= 0 ,0
Exp/Cntr=0.3,0.1

Type RM Length L Ch R = 1 ,3071    ,478,478,478
BEGIN DESCRIPTION:
UNT053 IN SUCR 4.0
END DESCRIPTION:
XS GIS Cut Line= 4
      2279301.78     13399191.34      2279376.61     13398822.54
      2279248.34     13398464.44      2279088.67      13398240.9
#Sta/Elev= 30
  4388.7  290.45  4454.5  288.46  4474.9  289.21  4505.5  287.26  4541.5  286.66
  4617.8  284.55  4641.5  284.45  4668.8  284.51    4679  283.23  4694.7  282.65
  4771.1  280.75  4781.8  280.62  4792.3  281.34    4856   279.1  4930.4  278.54
    4941  278.16  4955.7  278.23  4972.6  276.92  4981.2  277.99  5042.7  277.88
  5068.1  278.45  5121.6  280.64  5145.4  280.09  5193.6  282.77  5208.3     282
  5273.5  284.43  5294.4  285.79  5315.3  285.24  5351.3  286.66  5420.1  287.76
#Mann= 5 ,-1 , 0
  4388.7     .05       0  4541.5     .08       0  4641.5     .05       0
    4941     .03       0  5068.1     .05       0
Bank Sta=4930.4,5068.1
XS Rating Curve= 0 ,0
Exp/Cntr=0.3,0.1

Type RM Length L Ch R = 1 ,2593    ,110,110,110
BEGIN DESCRIPTION:
Mapping XS 7302159f
END DESCRIPTION:
XS GIS Cut Line= 3
      2280109.56      13398988.5      2279740.62     13398450.28
      2279121.33     13398225.09
#Sta/Elev= 30
  4374.3  283.57    4402  283.08  4435.2  283.06  4456.1  281.25  4485.4   281.1
  4548.8  278.64    4643  276.45  4722.1  274.75    4752  275.23  4823.7   273.5
  4859.6   273.5  4873.4  272.14    4952  269.28    5018  270.95  5040.6  273.32
  5171.1  274.01  5318.7  276.04  5327.9  276.38  5369.2  278.17  5381.1  277.51
  5405.2  278.25  5444.9  280.37    5461  279.84  5491.6  280.81  5522.2  282.98
    5530  282.14  5540.7   282.3  5625.8   285.9  5633.9  285.11  5685.8  286.78
#Mann= 4 ,-1 , 0
  4374.3     .08       0    4402     .05       0    4643     .03       0
  5318.7     .05       0
Bank Sta=4643,5327.9
XS Rating Curve= 0 ,0
Exp/Cntr=0.3,0.1

Type RM Length L Ch R = 1 ,2483    ,99,99,99
BEGIN DESCRIPTION:
UNT053 IN SUCR 3.0
END DESCRIPTION:
XS GIS Cut Line= 5
      2280187.65     13398962.41      2279857.81     13398432.92
      2279801.39     13398389.52       2279727.6     13398380.84
      2279128.62     13398142.11
#Sta/Elev= 30
  4346.6  283.78  4357.5  284.44  4567.5  277.72  4598.2  278.19  4836.2  272.64
  4850.8  273.08  4866.1  276.54    4872  275.14  4881.5  277.23  4887.3  274.59
  4902.7  277.15  4908.6  275.91    4918  276.76  4923.9  274.79  4939.3  277.28
  4945.2  275.78    4954  277.35  4960.5  277.75  5003.5   276.6  5009.8  278.23
    5018  277.08  5055.4  278.03  5075.5  276.87  5103.9  272.41    5106  270.31
  5108.7  269.81    5112  270.31  5113.3  272.81  5341.8  275.16  5760.7  286.84
#Mann= 3 ,-1 , 0
  4346.6     .05       0    4954     .03       0  5009.8     .05       0
#XS Ineff= 2 , 0
       0 4864.55  276.59    5060       0  278.16
Permanent Ineff=
       T       T
Bank Sta=4960.5,5009.8
XS Rating Curve= 0 ,0
Exp/Cntr=0.3,0.1

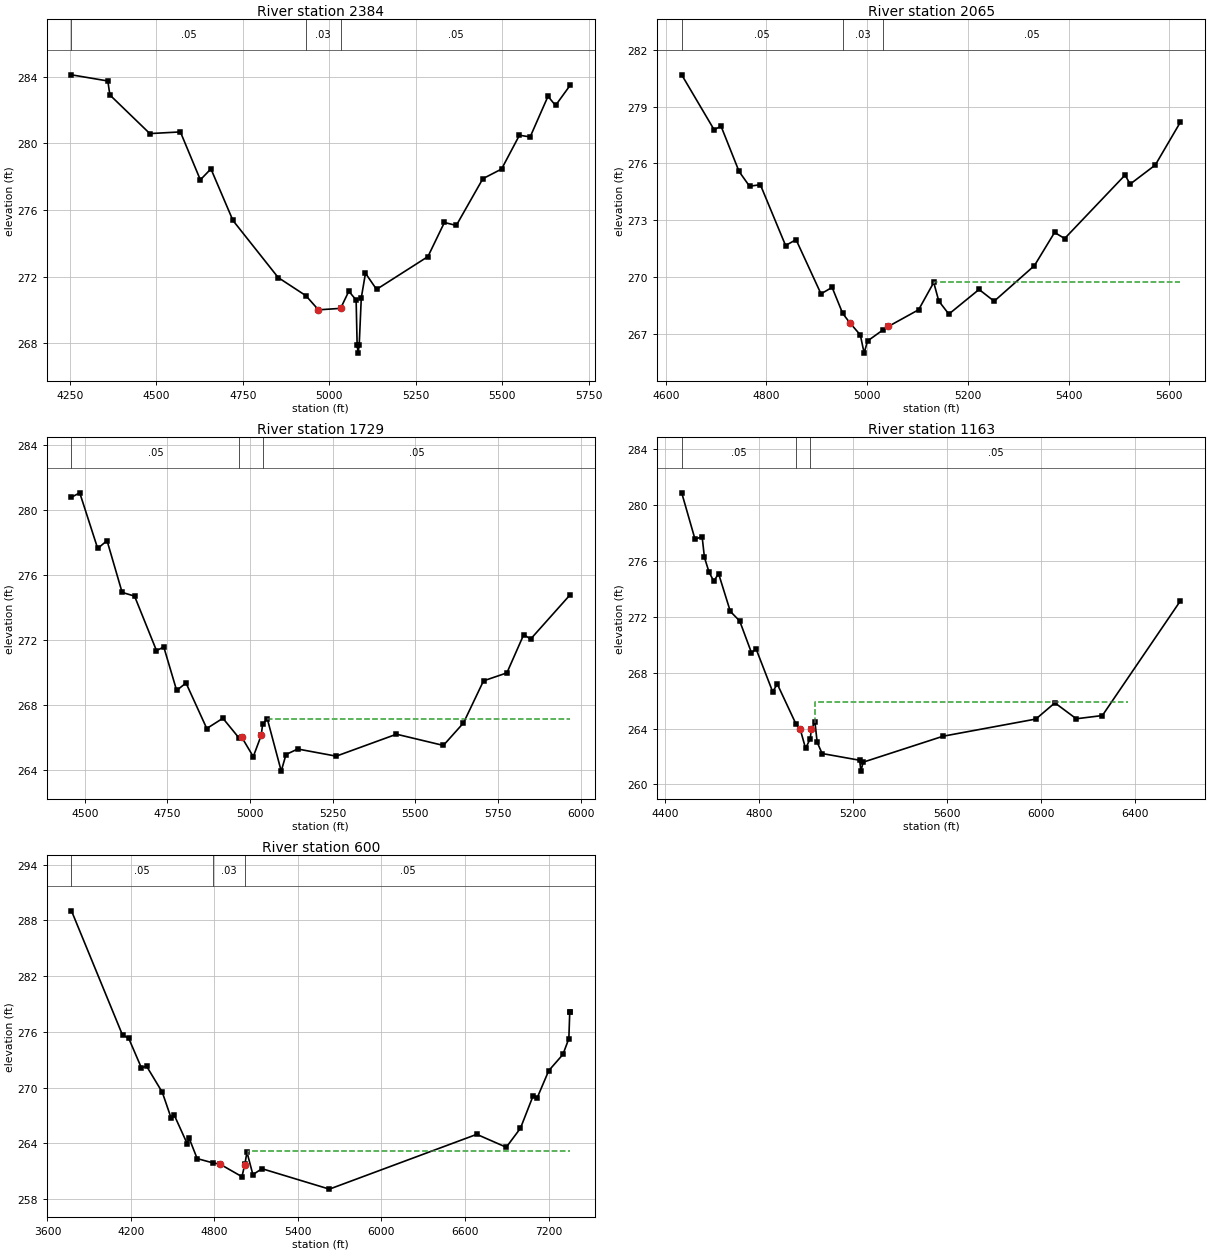
Type RM Length L Ch R = 1 ,2384    ,319,319,319
BEGIN DESCRIPTION:
Mapping XS 04d7bf86
END DESCRIPTION:
XS GIS Cut Line= 4
      2280300.54     13398927.74       2279953.3      13398376.5
      2279779.69     13398263.65      2279215.44     13398120.42
#Sta/Elev= 30
  4255.3  284.12  4360.3  283.75  4366.2  282.91  4481.6  280.59  4569.9  280.69
  4627.5  277.81  4658.1  278.47  4721.7  275.37  4852.4  271.94  4932.5  270.85
  4968.7     270  5032.7  270.09  5056.4  271.12  5077.5  270.59  5080.4   267.9
  5083.2   267.4  5086.4   267.9  5092.4  270.72  5104.5   272.2  5136.5  271.23
  5284.9   273.2  5332.5  275.25  5366.8  275.07  5443.6  277.88  5497.6  278.46
  5549.2  280.49  5580.2  280.39  5631.7  282.83  5653.5  282.28    5696   283.5
#Mann= 3 ,-1 , 0
  4255.3     .05       0  4932.5     .03       0  5032.7     .05       0
#XS Ineff= 2 , 0
                         5056.36          271.11
Permanent Ineff=
       F       F
Bank Sta=4968.7,5032.7
XS Rating Curve= 0 ,0
Exp/Cntr=0.3,0.1

Type RM Length L Ch R = 1 ,2065    ,336,336,336
BEGIN DESCRIPTION:
UNT053 IN SUCR 2.0
END DESCRIPTION:
XS GIS Cut Line= 3
      2280287.72     13398346.85      2280037.72     13398046.85
      2279437.73     13398046.85
#Sta/Elev= 30
  4631.8  280.68  4696.2  277.78  4709.9  277.97  4745.7  275.58  4766.5   274.8
    4788  274.88  4838.1  271.67  4858.9  271.98  4908.4  269.12  4930.5  269.46
  4951.4  268.09  4965.7  267.59  4986.5  266.95  4994.1  265.99  5000.8  266.63
  5032.3  267.23  5042.3   267.4  5102.3  268.28  5132.3  269.72  5142.3  268.74
  5162.3  268.05  5222.3  269.35  5252.3  268.73  5332.3  270.61  5372.3  272.36
  5392.3  272.04  5512.3  275.39  5522.3  274.91  5572.3  275.92  5622.3  278.19
#Mann= 3 ,-1 , 0
  4631.8     .05       0  4951.4     .03       0  5032.3     .05       0
#XS Ineff= 2 , 0
       0                 5133.18       0  269.74
Permanent Ineff=
       F       T
Bank Sta=4965.7,5042.3
XS Rating Curve= 0 ,0
Exp/Cntr=0.3,0.1

Type RM Length L Ch R = 1 ,1729    ,566,566,566
BEGIN DESCRIPTION:
Mapping XS 0b86a99d
END DESCRIPTION:
XS GIS Cut Line= 4
       2280568.5     13398309.47      2280392.11     13397935.31
      2280135.57     13397684.11      2279408.72     13397801.69
#Sta/Elev= 30
  4459.6   280.8  4484.6  281.07  4538.9  277.65  4567.2  278.13  4612.8  274.95
  4650.4  274.72  4716.8  271.37  4738.9  271.59  4777.8  268.92  4806.1  269.38
  4868.9  266.58  4917.7  267.21  4967.2  265.98  4974.3  266.06  5009.6  264.85
 5033.64  266.16  5037.9  266.85    5052  267.18  5094.2  263.96  5108.6  264.98
    5144  265.32  5260.5  264.88  5442.9  266.23  5584.7  265.54  5645.5  266.92
  5706.2  269.51  5776.9     270  5827.8  272.35  5848.8  272.08  5968.6  274.81
#Mann= 3 ,-1 , 0
  4459.6     .05       0  4967.2     .03       0  5037.9     .05       0
#XS Ineff= 2 , 0
       0                 5050.91       0  267.18
Permanent Ineff=
       F       T
Bank Sta=4974.3,5033.64
XS Rating Curve= 0 ,0
Exp/Cntr=0.3,0.1

Type RM Length L Ch R = 1 ,1163    ,563,563,563
BEGIN DESCRIPTION:
Mapping XS 31beabe8
END DESCRIPTION:
XS GIS Cut Line= 4
      2280883.83     13398373.58      2280862.45     13397785.66
      2280515.04     13397555.84      2279408.66     13397716.18
#Sta/Elev= 30
  4470.9  280.88  4527.7  277.55  4557.7  277.75  4567.7  276.25  4587.7  275.18
  4607.7  274.55  4627.7   275.1  4677.8  272.39  4717.8   271.7  4767.8  269.43
  4787.8  269.69  4857.9  266.64  4877.9  267.18  4957.9   264.3 4975.19  263.96
    4998  262.58    5018  263.27 5022.57  263.95    5038  264.46  5047.4  263.02
  5068.5  262.21    5228  261.73  5233.7  260.95    5243  261.59  5583.3  263.45
  5978.3  264.68  6059.1  265.84  6150.2   264.7  6261.2  264.93  6593.7  273.15
#Mann= 3 ,-1 , 0
  4470.9     .05       0  4957.9     .03       0    5018     .05       0
#XS Ineff= 1 ,-1
 5038.36 6368.58  265.89
Permanent Ineff=
       F
Bank Sta=4975.19,5022.57
XS Rating Curve= 0 ,0
Exp/Cntr=0.3,0.1

Type RM Length L Ch R = 1 ,600     ,0,0,0
BEGIN DESCRIPTION:
UNT053 IN SUCR 1.0
END DESCRIPTION:
XS GIS Cut Line= 4
       2280964.3     13398717.82      2281536.63     13397958.96
      2281113.02     13397333.96      2279265.82     13397674.24
#Sta/Elev= 30
  3772.5  289.04  4139.2  275.66  4182.9  275.34  4274.7  272.14    4312  272.31
    4425   269.5    4489   266.7  4511.8  267.01  4603.4  263.98    4618  264.55
  4675.5  262.36  4787.7   261.9  4838.6  261.77  4997.3  260.41 5017.15  261.69
  5018.3  261.75  5033.3  263.06  5075.9  260.63  5141.1  261.27  5625.5  259.07
  6684.6  264.97  6896.6  263.58  6998.5  265.63    7090  269.14  7118.9  268.91
  7201.8  271.83  7303.5  273.57  7346.2  275.28  7352.8  278.17  7356.3  278.17
#Mann= 3 ,-1 , 0
  3772.5     .05       0  4787.7     .03       0  5018.3     .05       0
#XS Ineff= 2 , 0
       0                 5038.64       0  263.15
Permanent Ineff=
       F       T
Bank Sta=4838.6,5017.15
XS Rating Curve= 0 ,0
Exp/Cntr=0.3,0.1

Chan Stop Cuts=-1
Use User Specified Reach Order=0
Composite Channel Slope=5