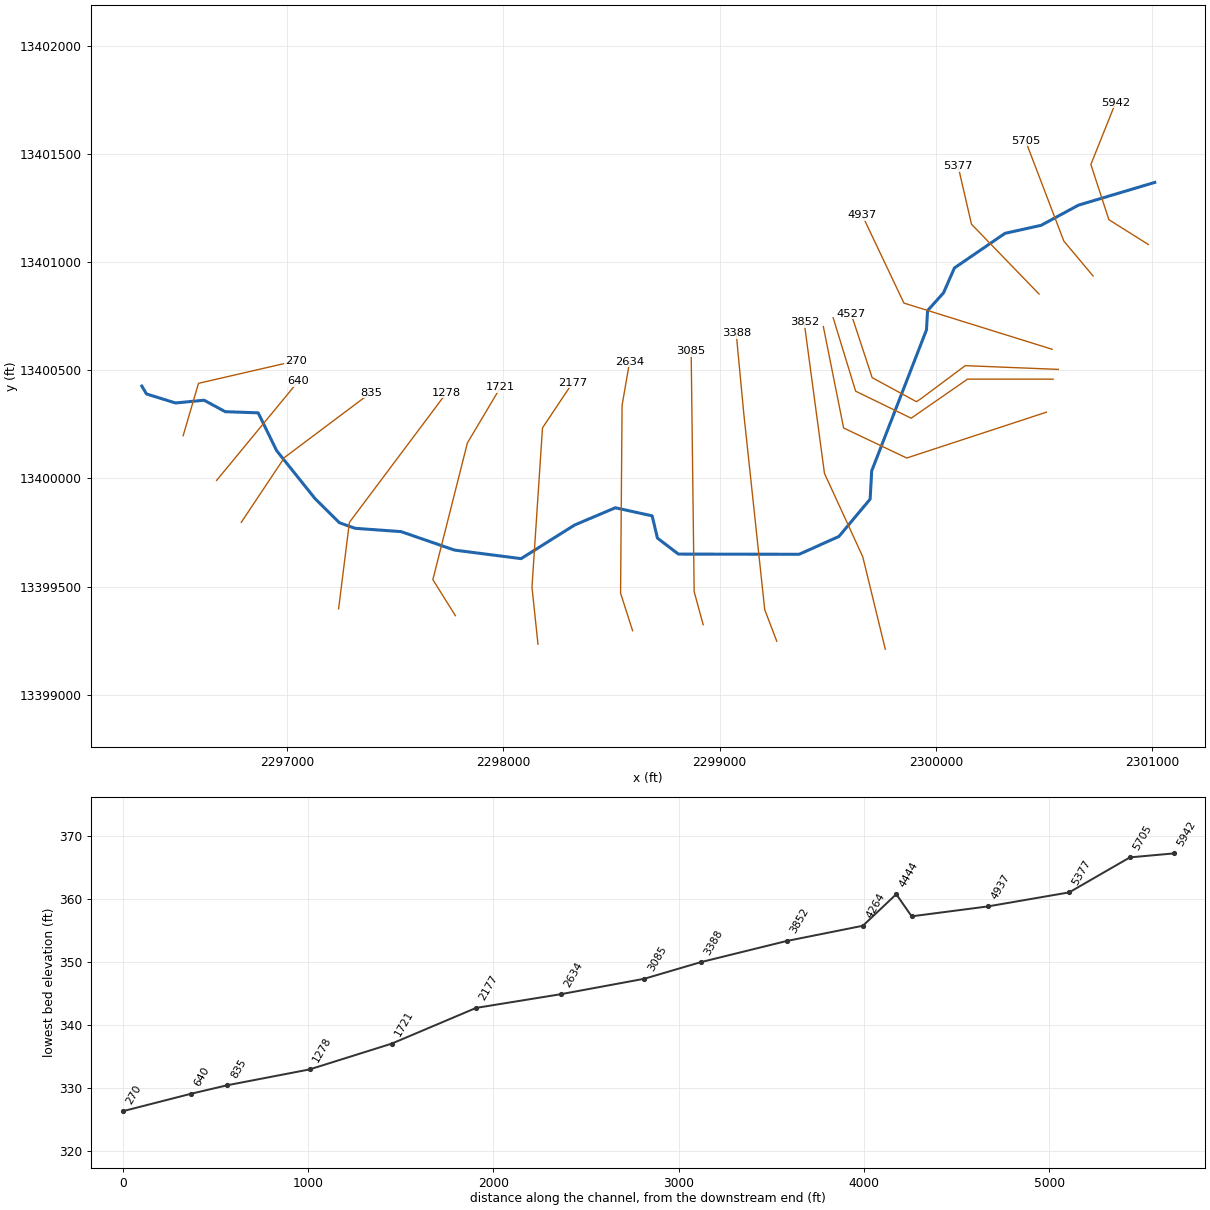
--- UNT054 IN SUCR.prj (project) ---

Proj Title=UNT054 IN SUCR Base Level Engineering
Current Plan=p01
Default Exp/Contr=0.3,0.1
English Units
Geom File=g01
Flow File=f01
Plan File=p01
Y Axis Title=Elevation
X Axis Title(PF)=Main Channel Distance
X Axis Title(XS)=Station
BEGIN DESCRIPTION:
UNT054 IN SUCR
END DESCRIPTION:
DSS Export Rating Curves= 0
DSS Export Rating Curve Sorted= 0
DSS Export Volume Flow Curves= 0
DXF OffsetX= 0
DXF OffsetY= 0
DXF ScaleX= 1
DXF ScaleY= 10

--- UNT054 IN SUCR.p01 (plan) ---

Plan Title=Multiple Run
Short Identifier=Multiple
Geom File=g01
Flow File=f01
Subcritical Flow
K Sum by GR= 0
Std Step Tol= 0.01
Critical Tol= 0.01
Num of Std Step Trials= 20
Max Error Tol= 0.3
Flow Tol Ratio= 0.001
Split Flow NTrial= 30
Split Flow Tol= 0.02
Split Flow Ratio= 0.02
Log Output Level= 0
Friction Slope Method= 1
Unsteady Friction Slope Method= 2
Unsteady Bridges Friction Slope Method= 1
Parabolic Critical Depth
Global Vel Dist=  1 , 1 , 1
Global Log Level= 0
CheckData=True
Encroach Param= -1, 0, 0, 0
BEGIN DESCRIPTION:
Multiple Run
END DESCRIPTION:

--- UNT054 IN SUCR.f01 (steady flow) ---

Flow Title=Multiple
Number of Profiles=7
Profile Names=10-year,25-year,50-year,1pct_min,100-year,1pct_plu,500-year
River Rch & RM= UNT054 IN SUCR,Reach-1,5942
     574     814    1016     927    1253    1695    1915
River Rch & RM= UNT054 IN SUCR,Reach-1,3852
     885    1284    1627    1506    2036    2753    3201
Boundary for River Rch & Prof#=UNT054 IN SUCR,Reach-1,1
Up Type=0
Dn Type=3
Dn Slope=0.005
Boundary for River Rch & Prof#=UNT054 IN SUCR,Reach-1,2
Up Type=0
Dn Type=3
Dn Slope=0.005
Boundary for River Rch & Prof#=UNT054 IN SUCR,Reach-1,3
Up Type=0
Dn Type=3
Dn Slope=0.005
Boundary for River Rch & Prof#=UNT054 IN SUCR,Reach-1,4
Up Type=0
Dn Type=3
Dn Slope=0.005
Boundary for River Rch & Prof#=UNT054 IN SUCR,Reach-1,5
Up Type=0
Dn Type=3
Dn Slope=0.005
Boundary for River Rch & Prof#=UNT054 IN SUCR,Reach-1,6
Up Type=0
Dn Type=3
Dn Slope=0.005
Boundary for River Rch & Prof#=UNT054 IN SUCR,Reach-1,7
Up Type=0
Dn Type=3
Dn Slope=0.005

--- UNT054 IN SUCR.g01 (geometry) ---

Geom Title=Existing Conditions
Program Version=4.10

River Reach=UNT054 IN SUCR  ,Reach-1
Reach XY= 30
      2301012.11     13401368.32      2300659.24     13401263.19
      2300486.46     13401169.89      2300319.44     13401132.91
      2300085.48     13400972.67       2300035.2      13400857.9
      2299961.36     13400775.35      2299956.48     13400686.89
      2299703.04     13400034.57      2299695.81     13399904.08
      2299551.37     13399731.51      2299367.69     13399649.21
      2298809.19     13399650.04      2298712.21     13399723.98
      2298687.72     13399826.86      2298517.62     13399864.25
      2298328.79      13399784.3       2298081.8     13399629.05
      2297773.46     13399668.64      2297526.53     13399753.99
      2297313.73     13399769.29      2297241.24      13399795.2
      2297128.86     13399906.56      2296951.27     13400128.09
      2296865.83     13400303.11      2296713.45     13400308.44
      2296615.86     13400361.43      2296483.59     13400348.69
      2296349.58     13400390.21      2296327.72     13400426.85

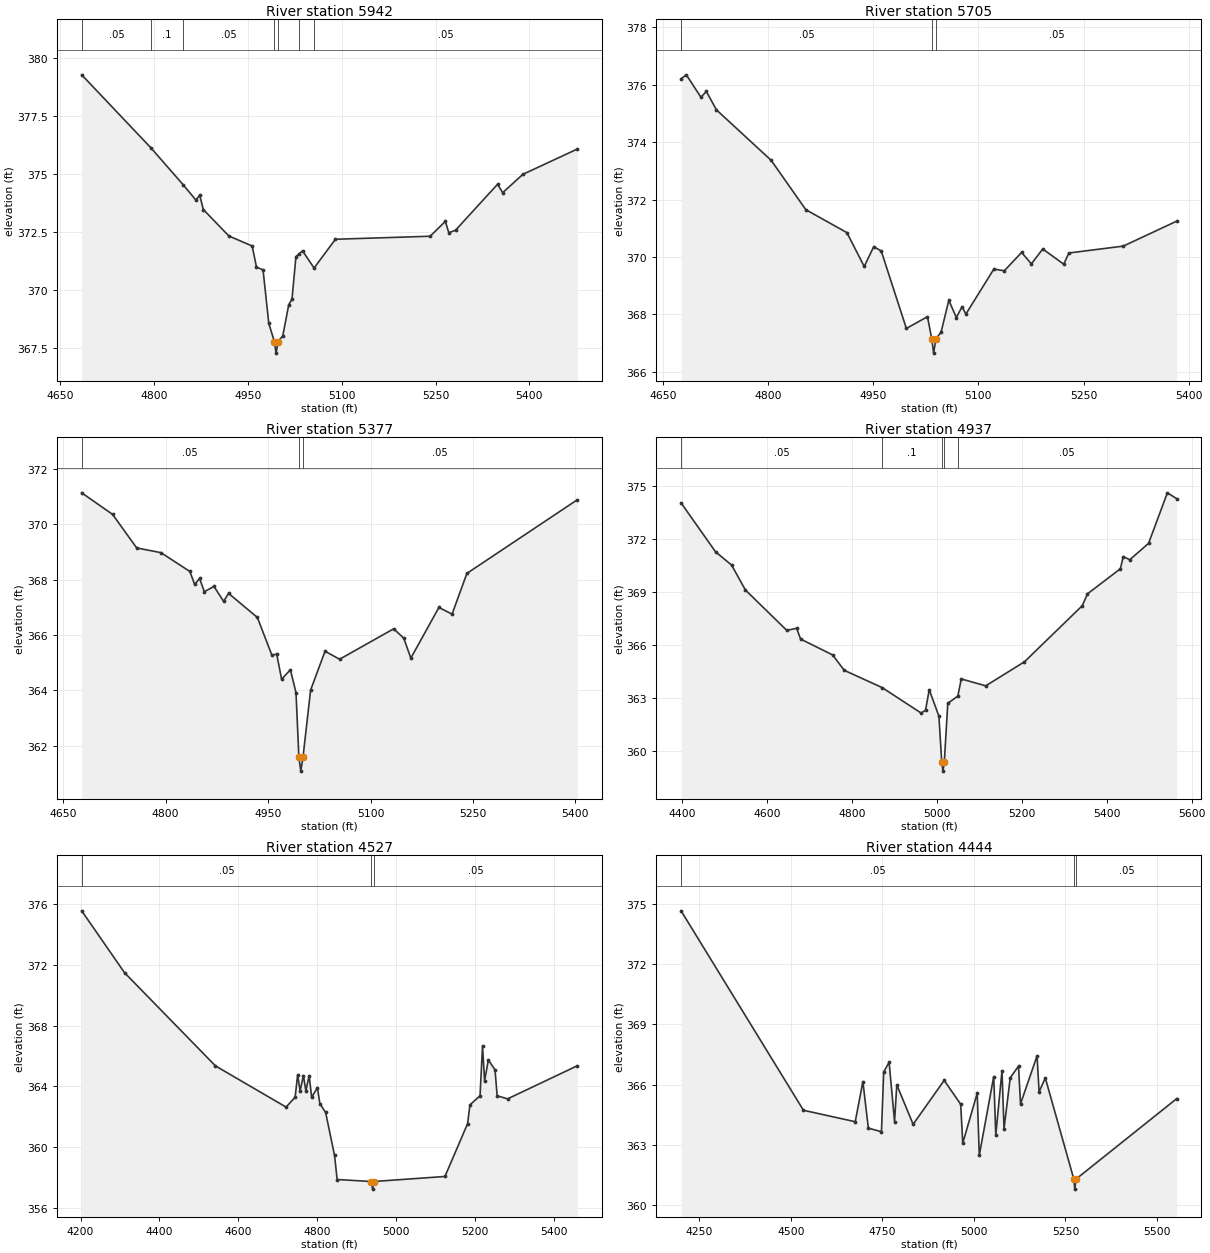
Type RM Length L Ch R = 1 ,5942    ,237,237,237
BEGIN DESCRIPTION:
UNT054 IN SUCR 11.0
END DESCRIPTION:
XS GIS Cut Line= 4
      2300982.24     13401081.35      2300799.94     13401195.94
      2300716.61     13401451.15      2300831.18     13401737.59
#Sta/Elev= 30
  4684.4  379.28  4795.1  376.13  4846.6  374.54  4866.9  373.88    4873  374.09
  4878.9  373.47  4919.7  372.33  4956.9   371.9  4963.8  370.99  4974.3  370.87
  4983.5  368.56  4992.4  367.78  4995.1  367.28  4998.4  367.78  5005.9  368.03
  5015.4  369.37  5020.6  369.61  5026.9  371.44  5031.4  371.55  5037.4  371.69
  5055.9  370.95    5090  372.19  5241.4  372.32  5265.7  372.96  5271.3  372.47
    5282  372.58  5349.1  374.56  5357.4   374.2  5389.7  374.99  5476.7  376.08
#Mann= 7 ,-1 , 0
  4684.4     .05       0  4795.1      .1       0  4846.6     .05       0
  4992.4     .03       0  4998.4     .05       0  5031.4      .1       0
  5055.9     .05       0
Bank Sta=4992.4,4998.4
XS Rating Curve= 0 ,0
Exp/Cntr=0.3,0.1

Type RM Length L Ch R = 1 ,5705    ,328,328,328
BEGIN DESCRIPTION:
Mapping XS e9bf9559
END DESCRIPTION:
XS GIS Cut Line= 3
      2300727.02     13400935.53      2300591.61     13401096.98
      2300414.54     13401560.49
#Sta/Elev= 30
    4676  376.21  4683.5  376.35  4704.3  375.57  4712.1  375.77  4726.4  375.13
  4804.5  373.37  4853.9  371.65  4912.5  370.85  4937.2  369.67  4950.8  370.36
  4961.5  370.21  4997.3  367.51  5027.4  367.92  5033.5  367.15  5036.2  366.65
  5039.5  367.15  5046.8  367.38  5057.9  368.49  5068.6  367.89  5076.8  368.27
  5082.2  368.01  5122.1  369.58    5137  369.52  5161.7  370.16  5175.6  369.76
  5191.8  370.28  5221.8  369.75  5229.1  370.14  5306.7  370.38  5382.9  371.25
#Mann= 3 ,-1 , 0
    4676     .05       0  5033.5     .03       0  5039.5     .05       0
Bank Sta=5033.5,5039.5
XS Rating Curve= 0 ,0
Exp/Cntr=0.3,0.1

Type RM Length L Ch R = 1 ,5377    ,440,440,440
BEGIN DESCRIPTION:
UNT054 IN SUCR 10.0
END DESCRIPTION:
XS GIS Cut Line= 3
      2300476.99     13400852.23      2300164.52     13401175.11
      2300102.38     13401444.41
#Sta/Elev= 30
  4677.1  371.13  4722.4  370.35  4757.6  369.14  4793.1  368.97  4835.5  368.29
  4842.5  367.82  4849.7  368.04  4856.6  367.56  4870.8  367.75  4884.9  367.21
  4892.1   367.5  4934.3  366.63  4955.7  365.26  4962.6  365.31  4969.8   364.4
  4982.7  364.74  4990.9  363.91  4995.1  361.58  4997.9  361.08  5001.1  361.58
  5012.3  364.01  5033.4  365.41  5054.7  365.12  5133.9  366.22  5148.7  365.88
    5159  365.16  5200.1  366.99  5219.4  366.75  5241.1  368.22  5402.8  370.88
#Mann= 3 ,-1 , 0
  4677.1     .05       0  4995.1     .03       0  5001.1     .05       0
Bank Sta=4995.1,5001.1
XS Rating Curve= 0 ,0
Exp/Cntr=0.3,0.1

Type RM Length L Ch R = 1 ,4937    ,410,410,410
BEGIN DESCRIPTION:
UNT054 IN SUCR 9.0
END DESCRIPTION:
XS GIS Cut Line= 3
      2300537.68     13400596.87      2299852.02     13400810.53
      2299659.32     13401216.77
#Sta/Elev= 30
    4397  374.03  4478.2  371.26    4516  370.51  4548.5   369.1  4646.1  366.81
  4669.3  366.93  4678.6  366.32  4754.1  365.42  4781.4  364.55  4870.8  363.57
  4962.6  362.13    4973  362.29  4981.7  363.45  5004.5  361.95  5011.2  359.34
    5014  358.84  5017.2  359.34  5025.4  362.68  5049.1  363.09  5057.2  364.06
  5114.8  363.67    5206  365.03  5342.4  368.21  5354.6  368.88  5432.1   370.3
  5438.9  370.99  5454.2  370.81  5498.5  371.74  5542.8   374.6  5564.8  374.27
#Mann= 5 ,-1 , 0
    4397     .05       0  4870.8      .1       0  5011.2     .07       0
  5017.2      .1       0  5049.1     .05       0
Bank Sta=5011.2,5017.2
XS Rating Curve= 0 ,0
Exp/Cntr=0.3,0.1

Type RM Length L Ch R = 1 ,4527    ,83,83,83
BEGIN DESCRIPTION:
Mapping XS 696e99c1
END DESCRIPTION:
XS GIS Cut Line= 6
      2300566.22     13400503.93       2300135.7     13400521.29
      2299930.84     13400368.51      2299910.01     13400354.62
      2299705.15     13400465.73      2299607.91     13400760.91
#Sta/Elev= 30
    4203  375.52  4311.6  371.46  4541.8  365.35  4720.7  362.65  4743.6   363.3
  4749.9  364.76  4756.2  363.71  4764.5  364.72  4770.8  363.71  4779.1  364.72
  4785.4  363.29    4800  363.93  4806.2  362.88  4820.8   362.3  4843.4  359.48
    4850   357.9  4936.8  357.77  4939.6  357.27  4942.8  357.77    5123   358.1
  5180.3  361.56  5186.4   362.8  5211.9  363.39  5218.2  366.67  5223.4  364.36
  5232.9  365.74  5249.9  365.09  5255.2  363.39  5281.7  363.19  5458.3  365.36
#Mann= 3 ,-1 , 0
    4203     .05       0  4936.8    .033       0  4942.8     .05       0
Bank Sta=4936.8,4942.8
XS Rating Curve= 0 ,0
Exp/Cntr=0.3,0.1

Type RM Length L Ch R = 1 ,4444    ,180,180,180
BEGIN DESCRIPTION:
Mapping XS 74953764
END DESCRIPTION:
XS GIS Cut Line= 5
      2300541.96     13400458.79      2300146.12     13400458.79
       2299885.7     13400278.23      2299628.76     13400403.23
      2299524.83     13400742.73
#Sta/Elev= 30
  4200.3  374.66  4534.5  364.72  4675.9  364.15  4696.8  366.15  4711.7  363.83
  4747.5  363.65  4753.6  366.63  4768.4  367.11  4783.3  364.16  4789.4  365.99
    4834  364.02  4918.8  366.21  4963.9  365.02  4969.5  363.08    5009  365.57
  5014.6  362.47  5054.1   366.4  5059.7  363.49  5076.7  366.69  5082.2   363.8
  5099.2  366.34  5121.8  366.92  5127.3  365.04  5172.4  367.43    5178  365.64
    5195  366.33  5272.8  361.29  5275.5  360.79  5278.8  361.29  5553.8   365.3
#Mann= 3 ,-1 , 0
  4200.3     .05       0  5272.8     .03       0  5278.8     .05       0
Bank Sta=5272.8,5278.8
XS Rating Curve= 0 ,0
Exp/Cntr=0.3,0.1

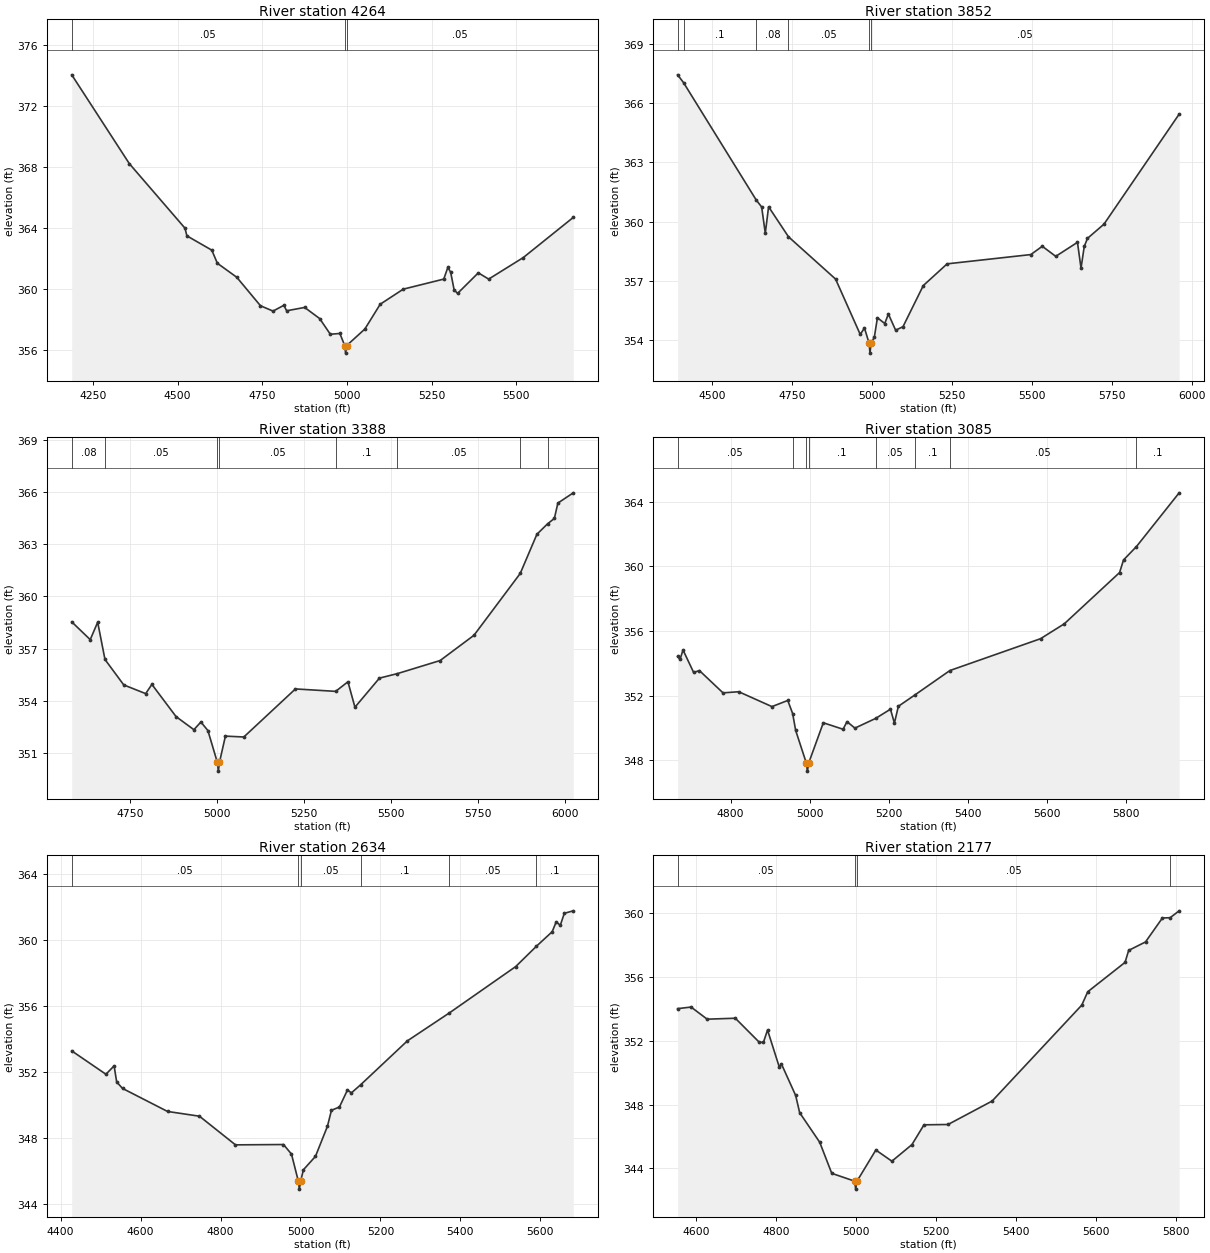
Type RM Length L Ch R = 1 ,4264    ,412,412,412
BEGIN DESCRIPTION:
UNT054 IN SUCR 8.0
END DESCRIPTION:
XS GIS Cut Line= 4
      2300510.67       13400306.      2299864.87     13400094.21
       2299573.2      13400233.1      2299479.46     13400701.82
#Sta/Elev= 30
  4187.5  374.04  4357.5  368.21  4521.9  363.97  4527.4  363.47    4601  362.53
  4617.4  361.67  4674.7  360.75  4744.7  358.88  4781.8  358.53  4813.7  358.91
    4822  358.55  4875.1  358.77  4919.4  358.04  4950.9  357.01  4979.1  357.06
  4993.3  356.27    4996  355.77  4999.3  356.27  5052.8  357.35  5098.2  358.98
  5166.3  359.97  5285.8  360.63  5297.9   361.4  5306.2  361.08  5316.4  359.93
  5326.6  359.69  5387.8  361.04  5418.4  360.63  5520.4  362.04  5668.2  364.68
#Mann= 3 ,-1 , 0
  4187.5     .05       0  4993.3     .03       0  4999.3     .05       0
Bank Sta=4993.3,4999.3
XS Rating Curve= 0 ,0
Exp/Cntr=0.3,0.1

Type RM Length L Ch R = 1 ,3852    ,464,464,464
BEGIN DESCRIPTION:
Mapping XS d4e12480
END DESCRIPTION:
XS GIS Cut Line= 4
      2299765.91     13399210.52      2299661.75     13399637.61
      2299484.66     13400023.03      2299390.92      13400720.9
#Sta/Elev= 30
  4393.1  367.43  4411.8  367.03  4638.9  361.09  4655.8  360.74  4667.2  359.41
  4677.5  360.75  4739.7  359.23  4886.9  357.09  4963.9  354.29  4977.3  354.61
  4991.7  353.84  4994.5  353.34  4997.7  353.84    5008  354.14  5017.7  355.13
  5040.7  354.84    5052  355.32  5074.7   354.5  5097.7  354.68  5161.1  356.76
  5235.6  357.86  5497.3  358.33  5533.1  358.75  5575.2  358.24  5643.1  358.95
  5654.2  357.64  5664.3  358.74  5674.4  359.15    5726  359.87    5961  365.44
#Mann= 6 ,-1 , 0
  4393.1     .05       0  4411.8      .1       0  4638.9     .08       0
  4739.7     .05       0  4991.7     .03       0  4997.7     .05       0
Bank Sta=4991.7,4997.7
XS Rating Curve= 0 ,0
Exp/Cntr=0.3,0.1

Type RM Length L Ch R = 1 ,3388    ,303,303,303
BEGIN DESCRIPTION:
UNT054 IN SUCR 7.0
END DESCRIPTION:
XS GIS Cut Line= 4
      2299263.97     13399247.27      2299208.41     13399393.12
      2299111.19     13400302.84      2299076.46     13400670.93
#Sta/Elev= 30
  4582.1  358.54  4635.2  357.52  4656.6  358.52  4677.6  356.38  4731.5  354.92
  4794.5  354.42  4812.3  354.95  4881.8   353.1    4933  352.35  4953.1  352.79
  4973.2   352.3  5000.4  350.47  5003.2  349.97  5006.4  350.47  5023.5  351.98
  5076.4  351.93  5224.7  354.69  5340.2  354.55  5375.5   355.1  5395.6  353.64
    5466  355.31  5517.7  355.57  5640.3  356.32  5737.5  357.77  5870.4  361.32
  5918.3  363.57  5948.9  364.17  5968.5  364.48  5978.5  365.36  6022.8  365.95
#Mann= 8 ,-1 , 0
  4582.1     .08       0  4677.6     .05       0  5000.4     .03       0
  5006.4     .05       0  5340.2      .1       0  5517.7     .05       0
  5870.4      .1       0  5948.9     .05       0
Bank Sta=5000.4,5006.4
XS Rating Curve= 0 ,0
Exp/Cntr=0.3,0.1

Type RM Length L Ch R = 1 ,3085    ,451,451,451
BEGIN DESCRIPTION:
Mapping XS 648c9416
END DESCRIPTION:
XS GIS Cut Line= 3
      2298923.69     13399323.67      2298882.02     13399476.45
      2298868.13      13400587.6
#Sta/Elev= 30
  4665.9  354.43    4672  354.25  4679.6  354.83  4706.5  353.44    4721  353.56
  4780.8  352.18  4820.6  352.25  4904.7  351.33  4944.7  351.71  4957.1   350.9
  4964.7  349.86  4991.7  347.84  4994.4  347.34  4997.7  347.84  5034.7  350.33
  5084.7  349.93  5094.7   350.4  5114.7     350  5167.2   350.6  5204.7  351.17
  5214.7  350.31  5224.7  351.35  5265.9  352.04  5355.1  353.56  5584.7  355.53
  5644.7  356.45  5784.7  359.62  5794.7   360.4  5827.5  361.23  5935.5  364.55
#Mann= 8 ,-1 , 0
  4665.9     .05       0  4957.1      .1       0  4991.7     .07       0
  4997.7      .1       0  5167.2     .05       0  5265.9      .1       0
  5355.1     .05       0  5827.5      .1       0
Bank Sta=4991.7,4997.7
XS Rating Curve= 0 ,0
Exp/Cntr=0.3,0.1

Type RM Length L Ch R = 1 ,2634    ,457,457,457
BEGIN DESCRIPTION:
UNT054 IN SUCR 6.0
END DESCRIPTION:
XS GIS Cut Line= 4
       2298597.3     13399295.88      2298541.74     13399469.51
      2298548.69     13400337.56       2298583.4     13400538.91
#Sta/Elev= 30
  4427.8  353.28  4513.3  351.86  4533.8  352.37  4540.2  351.39  4554.8     351
  4667.4   349.6  4747.4  349.31  4837.4  347.57  4957.5  347.59  4977.5  347.01
  4994.5  345.38  4997.2  344.88  5000.5  345.38  5007.5  346.06  5037.5  346.87
  5067.5   348.7  5077.5  349.67  5097.5  349.87  5117.5   350.9  5127.5  350.73
  5150.5  351.22  5267.5  353.89  5372.7  355.59  5538.3   358.4  5590.4  359.64
  5629.7  360.52  5639.8  361.12    5650  360.91  5660.1  361.64  5682.5  361.79
#Mann= 6 ,-1 , 0
  4427.8     .05       0  4994.5     .03       0  5000.5     .05       0
  5150.5      .1       0  5372.7     .05       0  5590.4      .1       0
Bank Sta=4994.5,5000.5
XS Rating Curve= 0 ,0
Exp/Cntr=0.3,0.1

Type RM Length L Ch R = 1 ,2177    ,456,456,456
BEGIN DESCRIPTION:
UNT054 IN SUCR 5.0
END DESCRIPTION:
XS GIS Cut Line= 4
       2298159.8     13399233.41      2298132.02     13399497.28
      2298180.63      13400233.4       2298319.5      13400441.7
#Sta/Elev= 30
  4554.6  354.01  4588.2  354.11  4628.5  353.35  4698.8  353.41  4759.2  351.89
  4769.2  351.91  4779.3  352.67  4808.8  350.34  4813.9  350.55  4849.6  348.57
  4859.6  347.49  4909.7  345.64  4939.8  343.69  4996.9   343.2  4999.6   342.7
  5002.9   343.2    5050  345.15  5090.1  344.45  5140.2  345.49  5170.3  346.73
  5230.4  346.75  5340.6  348.22  5564.6  354.23  5579.6  355.07  5672.8  356.91
  5681.8  357.66  5723.9  358.19  5766.1  359.69  5785.5  359.71    5808  360.14
#Mann= 4 ,-1 , 0
  4554.6     .05       0  4996.9     .03       0  5002.9     .05       0
  5785.5      .1       0
Bank Sta=4996.9,5002.9
XS Rating Curve= 0 ,0
Exp/Cntr=0.3,0.1

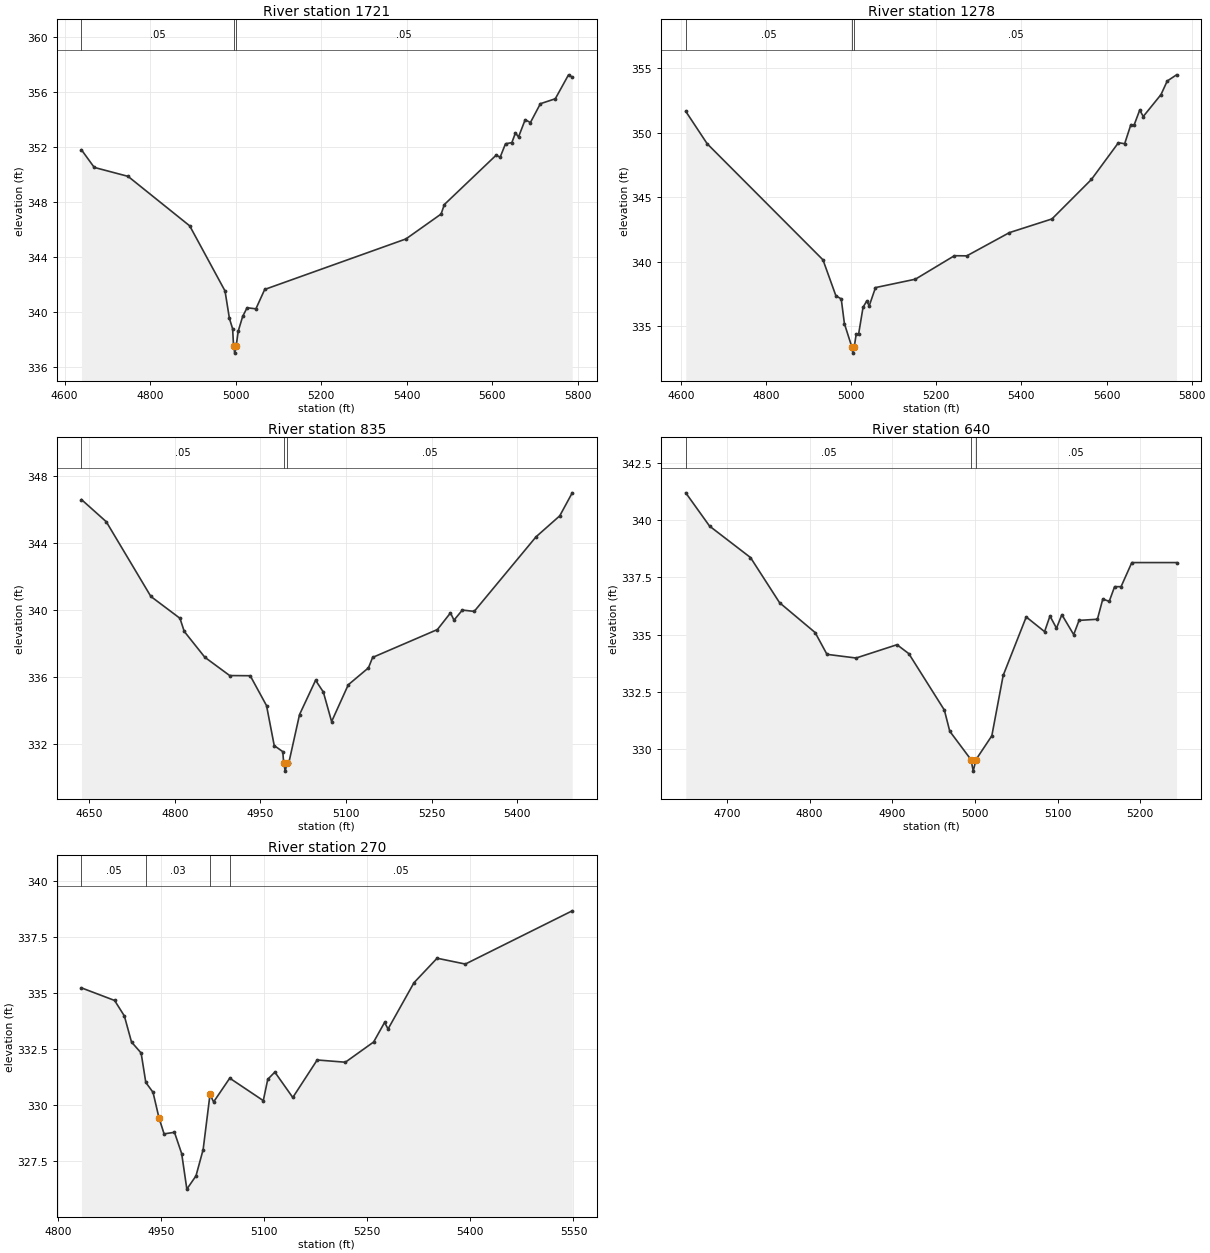
Type RM Length L Ch R = 1 ,1721    ,443,443,443
BEGIN DESCRIPTION:
UNT054 IN SUCR 4.0
END DESCRIPTION:
XS GIS Cut Line= 4
      2297777.84     13399365.37      2297673.69     13399532.01
      2297833.41     13400163.95      2297986.21     13400420.93
#Sta/Elev= 30
  4639.3  351.79  4669.2  350.51  4748.2  349.86  4892.4  346.26  4974.9  341.53
  4985.2  339.53  4992.7  338.78  4994.9  337.51  4997.6  337.01  5000.9  337.51
  5005.8  338.61  5016.2  339.68  5026.5  340.31  5047.1  340.23  5067.7  341.64
  5397.8  345.31    5480  347.12  5487.6  347.81  5608.4  351.39  5618.2  351.26
  5630.6  352.23  5645.4  352.31  5653.9  353.02    5661  352.72  5676.6  353.98
  5688.8  353.77  5712.1  355.14    5747   355.5  5777.9  357.24  5786.6  357.07
#Mann= 3 ,-1 , 0
  4639.3     .05       0  4994.9     .03       0  5000.9     .05       0
Bank Sta=4994.9,5000.9
XS Rating Curve= 0 ,0
Exp/Cntr=0.3,0.1

Type RM Length L Ch R = 1 ,1278    ,443,443,443
BEGIN DESCRIPTION:
UNT054 IN SUCR 3.0
END DESCRIPTION:
XS GIS Cut Line= 3
      2297237.73      13399396.9      2297287.72     13399796.85
      2297737.74     13400396.88
#Sta/Elev= 30
  4611.4  351.65  4661.7  349.14  4933.8  340.14  4964.1  337.36  4976.7  337.11
  4984.2  335.19  5001.4  333.41  5004.1  332.91  5007.4  333.41  5011.9   334.4
  5017.6   334.4    5028  336.47  5036.3  336.93  5042.6  336.59  5057.2  337.99
  5150.9  338.64  5242.6  340.46  5271.8  340.45  5371.8  342.25  5471.8  343.31
  5564.5  346.37    5628  349.22  5642.6  349.14  5657.2  350.62  5664.5  350.56
    5678  351.75  5686.3  351.25    5728  352.95  5742.6     354  5764.5  354.48
#Mann= 3 ,-1 , 0
  4611.4     .05       0  5001.4     .03       0  5007.4     .05       0
Bank Sta=5001.4,5007.4
XS Rating Curve= 0 ,0
Exp/Cntr=0.3,0.1

Type RM Length L Ch R = 1 ,835     ,195,195,195
BEGIN DESCRIPTION:
UNT054 IN SUCR 2.0
END DESCRIPTION:
XS GIS Cut Line= 3
      2296787.74     13399796.88      2296987.72     13400096.85
       2297387.7     13400396.84
#Sta/Elev= 30
  4636.1  346.57  4679.6  345.25  4757.8   340.8  4808.8   339.5  4816.3  338.72
  4852.4  337.18    4896  336.09    4932  336.08  4960.6   334.3  4974.1  331.92
  4989.1  331.56  4990.6   330.9  4993.4   330.4  4996.6   330.9  4999.7   330.9
  5018.5  333.77  5046.6  335.81  5060.2  335.11  5074.7  333.35  5103.9  335.54
  5139.3  336.55  5146.6  337.17  5260.2  338.83  5283.1  339.82  5289.3  339.39
  5303.9  339.99  5324.7  339.91  5433.1  344.35  5474.7   345.6  5496.6  346.97
#Mann= 3 ,-1 , 0
  4636.1     .05       0  4990.6     .03       0  4996.6     .05       0
Bank Sta=4990.6,4996.6
XS Rating Curve= 0 ,0
Exp/Cntr=0.3,0.1

Type RM Length L Ch R = 1 ,640     ,370,370,370
BEGIN DESCRIPTION:
Mapping XS 66f1ab83
END DESCRIPTION:
XS GIS Cut Line= 2
      2296673.55     13399990.67      2297051.21     13400448.64
#Sta/Elev= 30
  4650.3  341.18  4679.1  339.73  4728.6  338.36  4763.8  336.39  4806.8  335.09
  4821.1  334.14  4856.3  333.98  4905.8  334.56  4920.1  334.17  4963.1  331.71
  4969.6  330.79  4995.3  329.55    4998  329.05  5001.3  329.55  5020.5  330.59
  5034.2  333.22  5062.1  335.77  5084.3  335.13  5090.8  335.81  5098.7  335.28
  5105.2  335.87  5119.5     335    5126  335.62  5148.2  335.67  5154.7  336.55
  5162.5  336.45    5169  337.09  5176.8  337.09  5189.8  338.14  5243.9  338.14
#Mann= 3 ,-1 , 0
  4650.3     .05       0  4995.3     .03       0  5001.3     .05       0
Bank Sta=4995.3,5001.3
XS Rating Curve= 0 ,0
Exp/Cntr=0.3,0.1

Type RM Length L Ch R = 1 ,270     ,0,0,0
BEGIN DESCRIPTION:
UNT054 IN SUCR 1.0
END DESCRIPTION:
XS GIS Cut Line= 3
      2296518.75     13400196.99      2296589.89     13400439.51
       2297039.3     13400542.97
#Sta/Elev= 30
  4834.3  335.22  4882.5  334.66  4896.7  333.97  4907.1  332.81  4921.1  332.32
  4927.9  331.01  4938.4  330.57  4947.1  329.43  4954.5  328.72  4969.6  328.79
  4980.1  327.84  4987.6  326.26  5000.9  326.85  5011.3  328.02  5021.3  330.48
  5026.5  330.14    5050   331.2  5098.8   330.2  5105.3  331.15  5115.6  331.47
  5141.7  330.34  5177.2  332.01  5218.2  331.91  5259.3  332.81  5275.2  333.68
  5280.3  333.39    5318  335.45  5351.6  336.54  5392.7  336.28  5548.2  338.65
#Mann= 4 ,-1 , 0
  4834.3     .05       0  4927.9     .03       0  5021.3     .05       0
    5050     .05       0
Bank Sta=4947.1,5021.3
XS Rating Curve= 0 ,0
Exp/Cntr=0.3,0.1

Chan Stop Cuts=-1
Use User Specified Reach Order=0
Composite Channel Slope=5