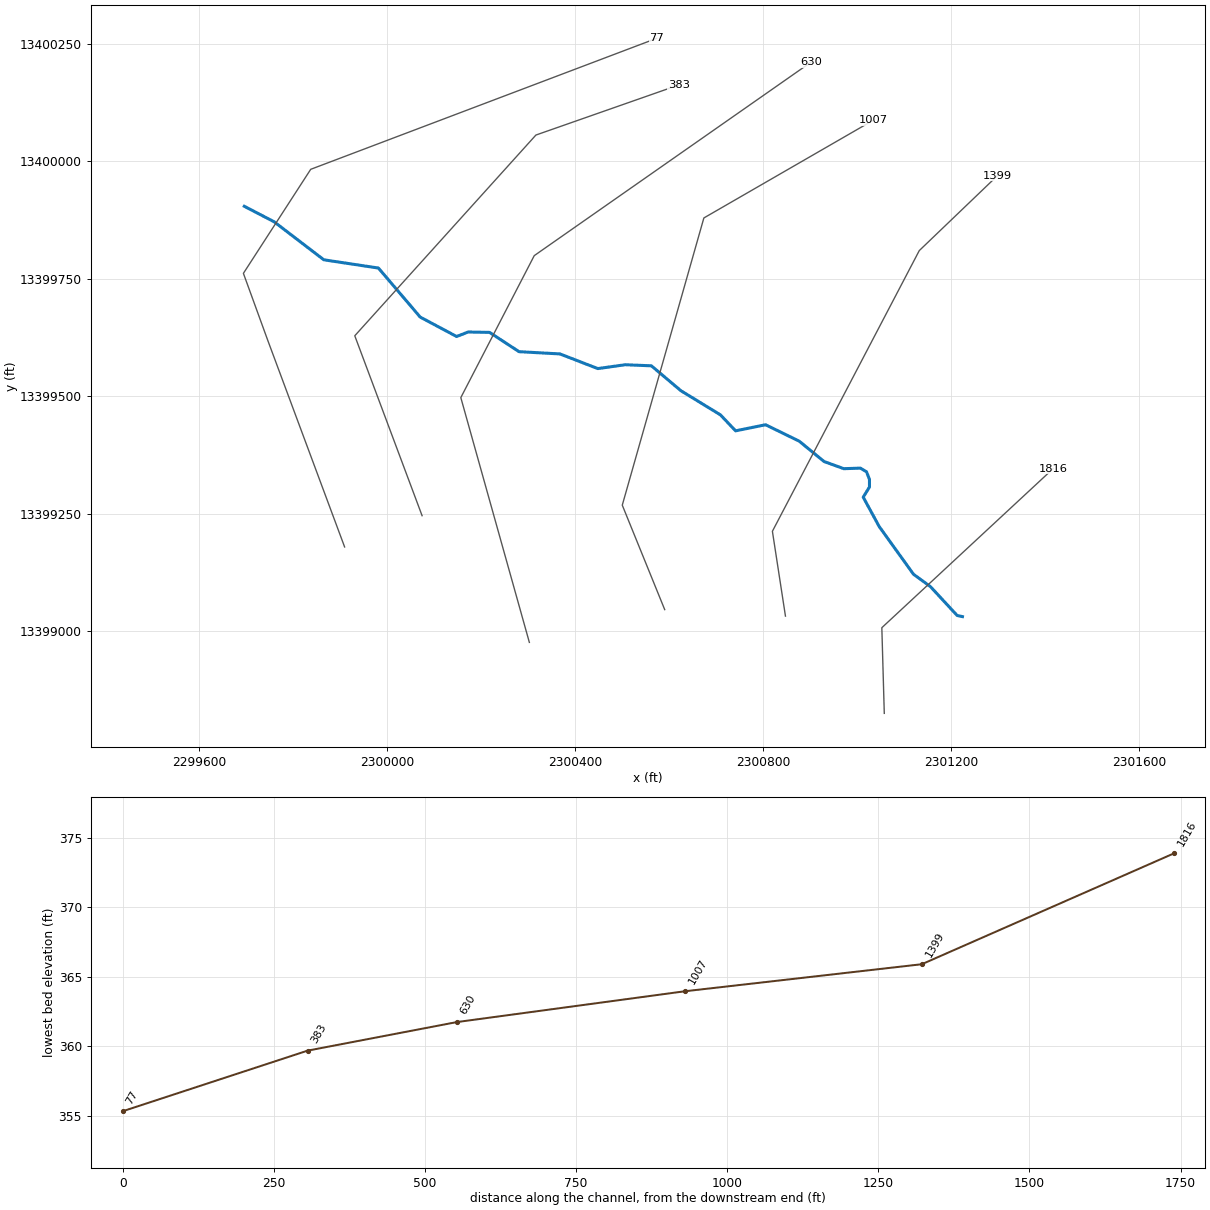
--- UNT055 IN SUCR.prj (project) ---

Proj Title=UNT055 IN SUCR Base Level Engineering
Current Plan=p01
Default Exp/Contr=0.3,0.1
English Units
Geom File=g01
Flow File=f01
Plan File=p01
BEGIN DESCRIPTION:
UNT055 IN SUCR
END DESCRIPTION:

--- UNT055 IN SUCR.p01 (plan) ---

Plan Title=Multiple Run
Short Identifier=Multiple
Geom File=g01
Flow File=f01
Subcritical Flow
K Sum by GR= 0
Std Step Tol= 0.01
Critical Tol= 0.01
Num of Std Step Trials= 20
Max Error Tol= 0.3
Flow Tol Ratio= 0.001
Split Flow NTrial= 30
Split Flow Tol= 0.02
Split Flow Ratio= 0.02
Log Output Level= 0
Friction Slope Method= 1
Unsteady Friction Slope Method= 2
Unsteady Bridges Friction Slope Method= 1
Parabolic Critical Depth
Global Vel Dist=  1 , 1 , 1
Global Log Level= 0
CheckData=True
Encroach Param= -1, 0, 0, 0
BEGIN DESCRIPTION:
Multiple Run
END DESCRIPTION:

--- UNT055 IN SUCR.f01 (steady flow) ---

Flow Title=Multiple
Number of Profiles=7
Profile Names=10-year,25-year,50-year,1pct_min,100-year,1pct_plu,500-year
River Rch & RM= UNT055 IN SUCR,Reach-1,1816
     364     504     618     557     753    1018    1118
River Rch & RM= UNT055 IN SUCR,Reach-1,383
     393     546     673     607     821    1111    1227
Boundary for River Rch & Prof#=UNT055 IN SUCR,Reach-1,1
Up Type=0
Dn Type=3
Dn Slope=0.005
Boundary for River Rch & Prof#=UNT055 IN SUCR,Reach-1,2
Up Type=0
Dn Type=3
Dn Slope=0.005
Boundary for River Rch & Prof#=UNT055 IN SUCR,Reach-1,3
Up Type=0
Dn Type=3
Dn Slope=0.005
Boundary for River Rch & Prof#=UNT055 IN SUCR,Reach-1,4
Up Type=0
Dn Type=3
Dn Slope=0.005
Boundary for River Rch & Prof#=UNT055 IN SUCR,Reach-1,5
Up Type=0
Dn Type=3
Dn Slope=0.005
Boundary for River Rch & Prof#=UNT055 IN SUCR,Reach-1,6
Up Type=0
Dn Type=3
Dn Slope=0.005
Boundary for River Rch & Prof#=UNT055 IN SUCR,Reach-1,7
Up Type=0
Dn Type=3
Dn Slope=0.005

--- UNT055 IN SUCR.g01 (geometry) ---

Geom Title=Existing Conditions

River Reach=UNT055 IN SUCR,Reach-1
Reach XY= 30
      2301223.95     13399030.94      2301212.64     13399033.40
      2301155.83     13399094.76      2301119.72     13399121.15
      2301046.80     13399222.54      2301012.77     13399285.04
      2301026.06     13399306.82      2301026.06     13399322.96
      2301019.81     13399339.11      2301006.79     13399346.92
      2300971.48     13399345.75      2300929.59     13399360.93
      2300876.61     13399404.28      2300804.99     13399439.23
      2300741.19     13399426.27      2300708.92     13399460.26
      2300624.90     13399511.59      2300562.00     13399564.64
      2300506.28     13399566.92      2300448.10     13399558.73
      2300367.34     13399589.94      2300280.44     13399594.70
      2300217.73     13399635.74      2300172.08     13399636.56
      2300147.63     13399627.00      2300070.12     13399668.31
      2299981.23     13399772.65      2299865.08     13399790.19
      2299759.35     13399871.09      2299695.81     13399904.08

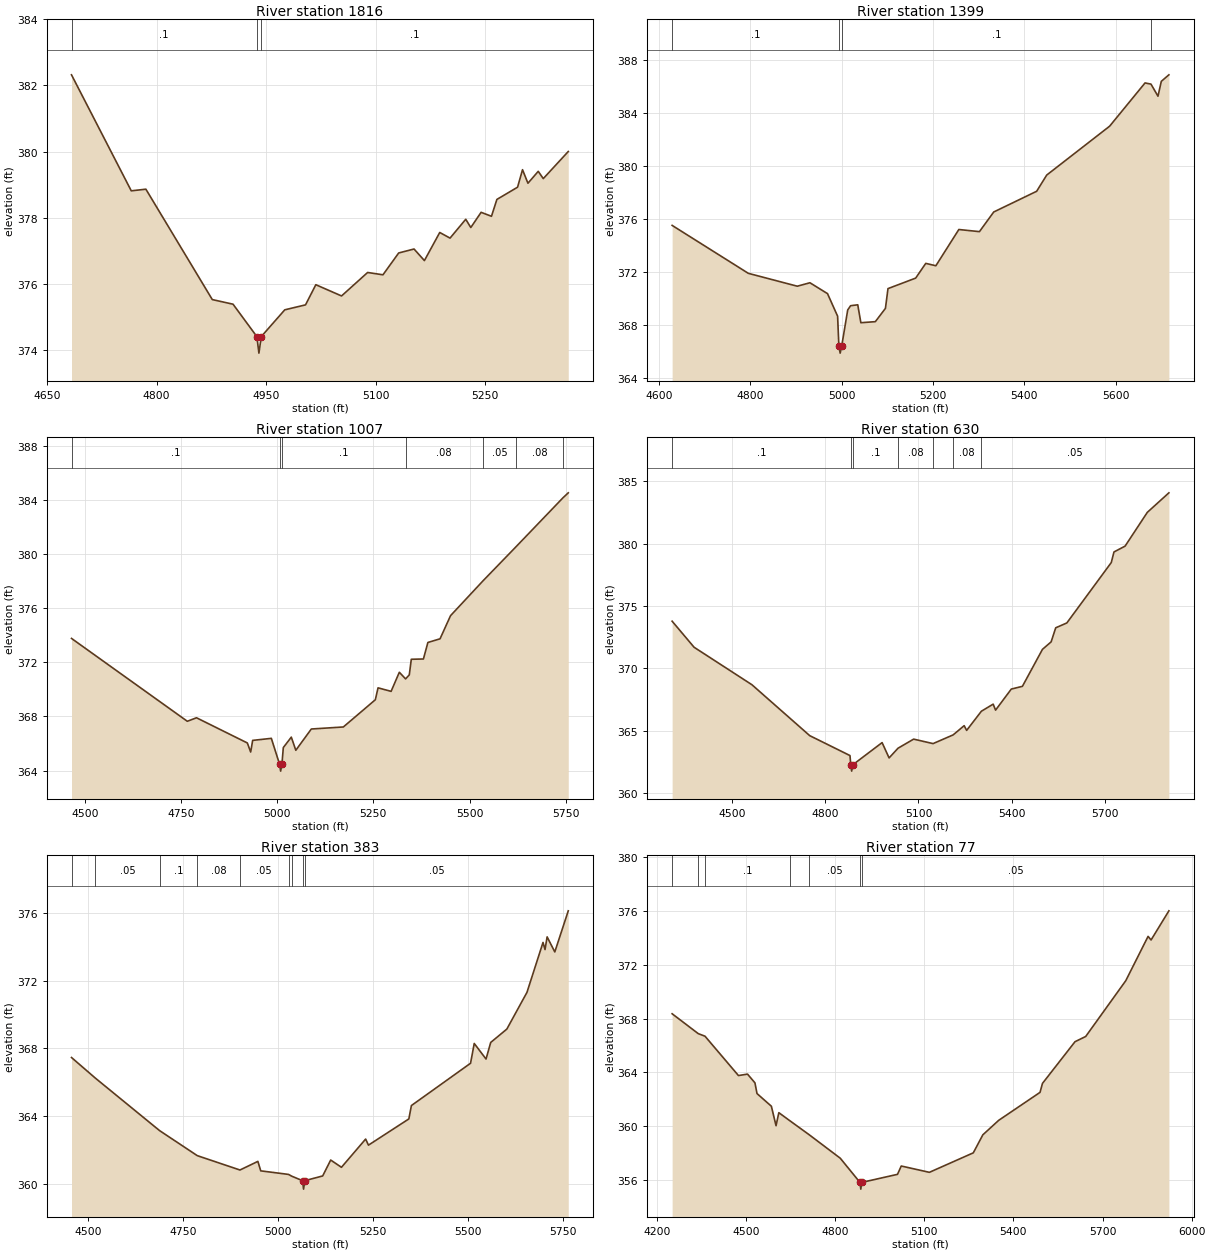
Type RM Length L Ch R = 1,1816,417,417,417
BEGIN DESCRIPTION:
UNT055 IN SUCR 4.0
END DESCRIPTION:
XS GIS Cut Line= 3
      2301057.58     13398825.10      2301052.37     13399007.40
      2301416.95     13399345.94
#Sta/Elev= 30
  4683.6  382.32  4765.4  378.81  4785.4  378.86  4876.3  375.52  4904.7  375.38
  4937.3  374.40  4940.1  373.90  4943.3  374.40  4975.5  375.21  5003.9  375.36
  5018.0  375.97  5053.2  375.63  5088.9  376.34  5109.9  376.27  5131.4  376.93
  5152.4  377.05  5166.6  376.70  5187.6  377.55  5201.7  377.38  5223.2  377.95
  5230.1  377.70  5244.2  378.16  5258.4  378.04  5265.8  378.55  5294.1  378.92
  5300.9  379.45  5308.3  379.04  5322.4  379.40  5329.3  379.18  5363.5  380.00
#Mann=3,-1,0
  4683.6     0.1       0  4937.3    0.07       0  4943.3     0.1       0
Bank Sta=4937.3,4943.3
Exp/Cntr=0.3,0.1

Type RM Length L Ch R = 1,1399,392,392,392
BEGIN DESCRIPTION:
UNT055 IN SUCR 3.0
END DESCRIPTION:
XS GIS Cut Line= 4
      2300847.30     13399032.01      2300819.52     13399212.56
      2301132.02     13399809.78      2301298.72     13399969.53
#Sta/Elev= 30
  4628.9  375.53  4795.7  371.92  4902.9  370.95  4930.6  371.21  4969.1  370.39
  4991.2  368.69  4994.0  366.41  4996.8  365.91  5000.0  366.41  5013.3  369.16
  5019.6  369.48  5035.3  369.55  5042.1  368.20  5073.8  368.28  5095.9  369.28
  5101.5  370.77  5162.1  371.56  5184.2  372.67  5206.3  372.49  5256.6  375.22
  5301.7  375.06  5333.0  376.54  5427.0  378.10  5449.0  379.32  5586.7  383.00
  5664.3  386.26  5677.3  386.17  5692.6  385.26  5699.9  386.38  5716.5  386.87
#Mann=4,-1,0
  4628.9     0.1       0  4994.0    0.07       0  5000.0     0.1       0
  5677.3    0.05       0
Bank Sta=4994,5000
Exp/Cntr=0.3,0.1

Type RM Length L Ch R = 1,1007,377,377,377
BEGIN DESCRIPTION:
UNT055 IN SUCR 2.0
END DESCRIPTION:
XS GIS Cut Line= 4
      2300590.37     13399045.87      2300500.08     13399268.12
      2300673.69     13399879.23      2301033.78     13400086.97
#Sta/Elev= 30
  4465.6  373.76  4766.6  367.64  4790.4  367.90  4922.5  366.04  4931.2  365.37
  4936.4  366.23  4984.9  366.38  5006.4  364.46  5009.1  363.96  5012.4  364.46
  5016.0  365.70  5036.8  366.47  5048.5  365.50  5088.8  367.07  5172.0  367.22
  5255.1  369.23  5262.2  370.11  5296.1  369.85  5317.5  371.26  5333.8  370.77
  5343.4  371.07  5348.6  372.22  5380.1  372.24  5391.7  373.46  5423.3  373.73
  5450.6  375.44  5534.9  378.01  5620.1  380.51  5743.0  384.15  5756.5  384.51
#Mann=7,-1,0
  4465.6     0.1       0  5006.4    0.07       0  5012.4     0.1       0
  5333.8    0.08       0  5534.9    0.05       0  5620.1    0.08       0
  5743.0    0.05       0
Bank Sta=5006.4,5012.4
Exp/Cntr=0.3,0.1

Type RM Length L Ch R = 1,630,247,247,247
BEGIN DESCRIPTION:
Mapping XS 65bb5d
END DESCRIPTION:
XS GIS Cut Line= 4
      2300302.38     13398976.12      2300156.54     13399496.98
      2300312.79     13399799.07      2300901.33     13400210.52
#Sta/Elev= 30
  4307.1  373.78  4377.7  371.69  4563.9  368.68  4750.0  364.59  4879.6  362.99
  4882.2  362.24  4885.0  361.74  4888.2  362.24  4983.0  364.03  5005.5  362.80
  5034.3  363.58  5084.5  364.31  5147.1  363.95  5211.7  364.65  5247.2  365.39
  5255.1  365.01  5302.6  366.55  5340.5  367.12  5348.3  366.64  5398.9  368.33
  5434.7  368.55  5499.2  371.52  5527.1  372.12  5541.9  373.25  5577.7  373.64
  5720.7  378.49  5729.4  379.34  5765.2  379.81  5836.7  382.52  5906.2  384.09
#Mann=7,-1,0
  4307.1     0.1       0  4882.2    0.07       0  4888.2     0.1       0
  5034.3    0.08       0  5147.1    0.05       0  5211.7    0.08       0
  5302.6    0.05       0
Bank Sta=4882.2,4888.2
Exp/Cntr=0.3,0.1

Type RM Length L Ch R = 1,383,306,306,306
BEGIN DESCRIPTION:
Mapping XS 65bb5dfa
END DESCRIPTION:
XS GIS Cut Line= 4
      2300074.14     13399245.74      2299930.91     13399628.57
      2300316.32     13400055.65      2300620.18     13400162.13
#Sta/Elev= 30
  4457.0  367.46  4519.8  366.24  4688.5  363.14  4787.6  361.66  4899.9  360.81
  4947.0  361.32  4954.5  360.76  5027.5  360.55  5036.5  360.44  5064.4  360.18
  5067.1  359.68  5070.4  360.18  5117.4  360.46  5138.4  361.40  5166.7  360.97
  5230.3  362.64  5237.7  362.28  5343.9  363.83  5350.6  364.62  5506.1  367.12
  5515.8  368.29  5546.8  367.37  5559.1  368.35  5601.5  369.14  5654.4  371.31
  5696.6  374.26  5701.9  373.84  5707.4  374.59  5727.6  373.70  5763.0  376.13
#Mann=9,-1,0
  4457.0     0.1       0  4519.8    0.05       0  4688.5     0.1       0
  4787.6    0.08       0  4899.9    0.05       0  5027.5    0.08       0
  5036.5    0.05       0  5064.4    0.03       0  5070.4    0.05       0
Bank Sta=5064.4,5070.4
Exp/Cntr=0.3,0.1

Type RM Length L Ch R = 1,77,0,0,0
BEGIN DESCRIPTION:
UNT055 IN SUCR 1.0
END DESCRIPTION:
XS GIS Cut Line= 5
      2299909.27     13399179.22      2299746.01     13399618.15
      2299693.93     13399761.38      2299837.16     13399982.74
      2300573.19     13400261.43
#Sta/Elev= 30
  4252.0  368.36  4340.0  366.88  4362.6  366.69  4475.2  363.76  4505.6  363.87
  4530.6  363.22  4537.6  362.42  4585.9  361.48  4601.6  360.03  4611.0  361.00
  4647.4  360.41  4713.0  359.36  4817.7  357.61  4884.0  355.81  4886.8  355.31
  4890.0  355.81  5010.3  356.41  5022.9  357.03  5117.5  356.56  5265.3  358.01
  5297.4  359.35  5350.8  360.43  5489.8  362.51  5498.1  363.18  5607.5  366.28
  5643.5  366.67  5778.3  370.82  5853.4  374.12  5863.4  373.85  5923.4  376.02
#Mann=7,-1,0
  4252.0     0.1       0  4340.0    0.05       0  4362.6     0.1       0
  4647.4    0.08       0  4713.0    0.05       0  4884.0    0.03       0
  4890.0    0.05       0
Bank Sta=4884,4890
Exp/Cntr=0.3,0.1

Chan Stop Cuts=-1