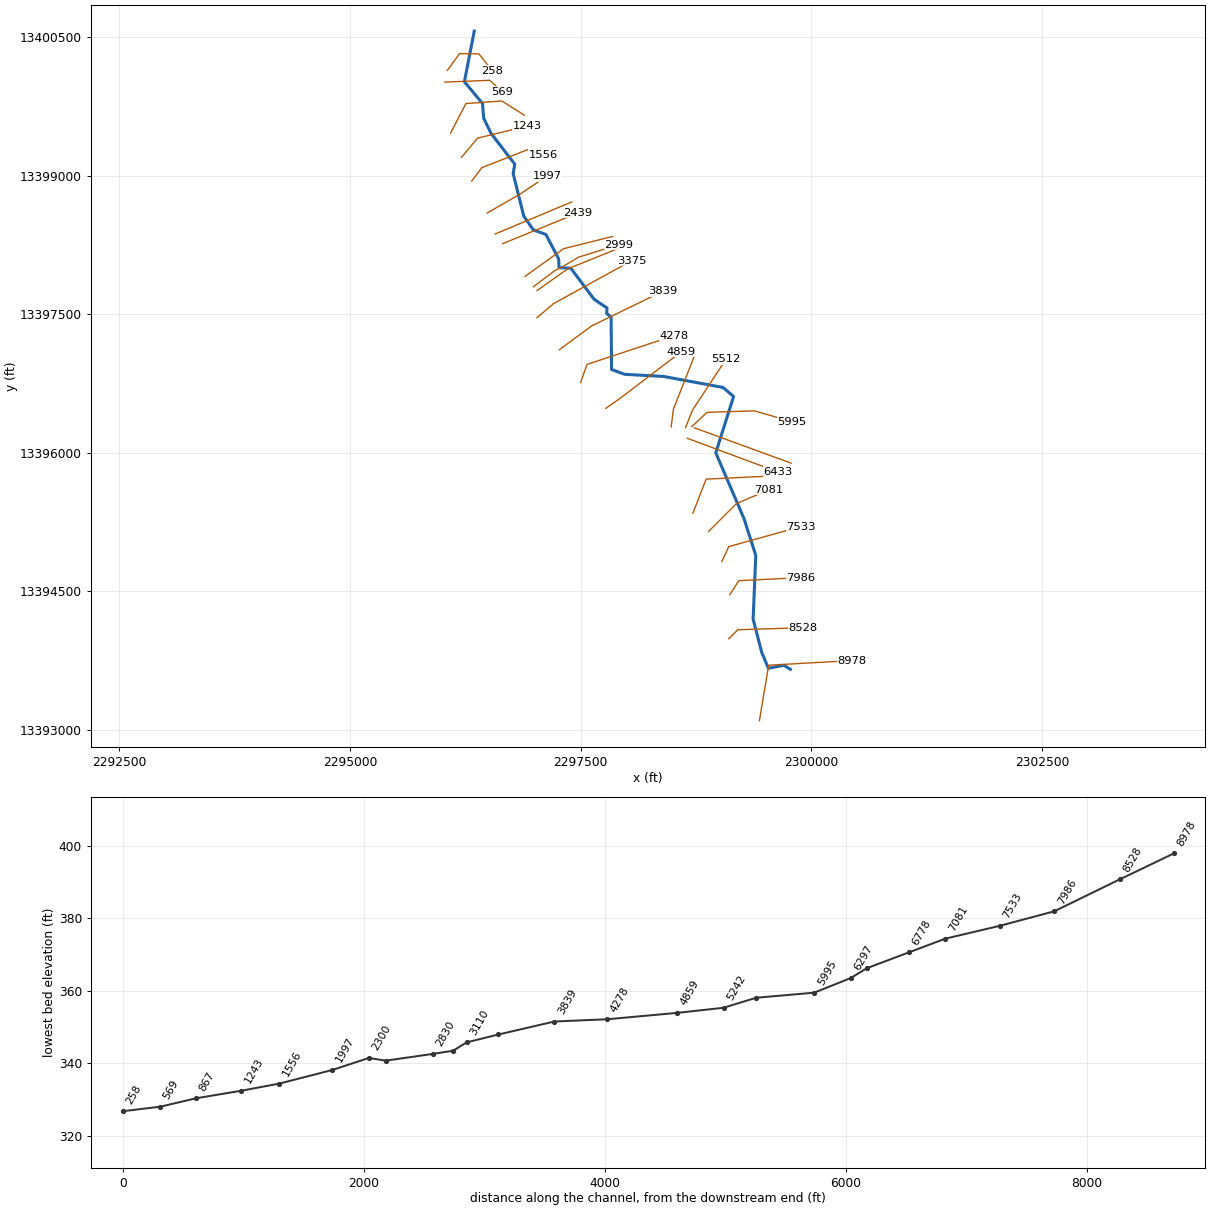
--- UNT056 IN SUCR.prj (project) ---

Proj Title=UNT056 IN SUCR Base Level Engineering
Current Plan=p01
Default Exp/Contr=0.3,0.1
English Units
Geom File=g01
Flow File=f01
Plan File=p01
Y Axis Title=Elevation
X Axis Title(PF)=Main Channel Distance
X Axis Title(XS)=Station
BEGIN DESCRIPTION:
UNT056 IN SUCR
END DESCRIPTION:
DSS Export Rating Curves= 0
DSS Export Rating Curve Sorted= 0
DSS Export Volume Flow Curves= 0
DXF OffsetX= 0
DXF OffsetY= 0
DXF ScaleX= 1
DXF ScaleY= 10

--- UNT056 IN SUCR.p01 (plan) ---

Plan Title=Multiple Run
Short Identifier=Multiple
Geom File=g01
Flow File=f01
Subcritical Flow
K Sum by GR= 0
Std Step Tol= 0.01
Critical Tol= 0.01
Num of Std Step Trials= 20
Max Error Tol= 0.3
Flow Tol Ratio= 0.001
Split Flow NTrial= 30
Split Flow Tol= 0.02
Split Flow Ratio= 0.02
Log Output Level= 0
Friction Slope Method= 1
Unsteady Friction Slope Method= 2
Unsteady Bridges Friction Slope Method= 1
Parabolic Critical Depth
Global Vel Dist=  1 , 1 , 1
Global Log Level= 0
CheckData=True
Encroach Param= -1, 0, 0, 0
BEGIN DESCRIPTION:
Multiple Run
END DESCRIPTION:

--- UNT056 IN SUCR.f01 (steady flow) ---

Flow Title=Multiple
Program Version=4.10
Number of Profiles= 7
Profile Names=10-year,25-year,50-year,1pct_min,100-year,1pct_plu,500-year
River Rch & RM=UNT056 IN SUCR,Reach-1         ,8978
     440     614     759     687     930    1257    1396
River Rch & RM=UNT056 IN SUCR,Reach-1         ,6297
     453     633     782     708     957    1294    1437
River Rch & RM=UNT056 IN SUCR,Reach-1         ,5512
     850    1230    1556    1438    1944    2630    3049
River Rch & RM=UNT056 IN SUCR,Reach-1         ,2300
     860    1243    1572    1452    1963    2655    3073
Boundary for River Rch & Prof#=UNT056 IN SUCR,Reach-1         , 1
Up Type= 0
Dn Type= 3
Dn Slope=0.0037
Boundary for River Rch & Prof#=UNT056 IN SUCR,Reach-1         , 2
Up Type= 0
Dn Type= 3
Dn Slope=0.0037
Boundary for River Rch & Prof#=UNT056 IN SUCR,Reach-1         , 3
Up Type= 0
Dn Type= 3
Dn Slope=0.0037
Boundary for River Rch & Prof#=UNT056 IN SUCR,Reach-1         , 4
Up Type= 0
Dn Type= 3
Dn Slope=0.0037
Boundary for River Rch & Prof#=UNT056 IN SUCR,Reach-1         , 5
Up Type= 0
Dn Type= 3
Dn Slope=0.0037
Boundary for River Rch & Prof#=UNT056 IN SUCR,Reach-1         , 6
Up Type= 0
Dn Type= 3
Dn Slope=0.0037
Boundary for River Rch & Prof#=UNT056 IN SUCR,Reach-1         , 7
Up Type= 0
Dn Type= 3
Dn Slope=0.0037
DSS Import GetInterval= 0
DSS Import GetPeak= 0
DSS Import FillOption= 0

--- UNT056 IN SUCR.g01 (geometry) ---

Geom Title=Existing Conditions
Program Version=4.10

River Reach=UNT056 IN SUCR  ,Reach-1
Reach XY= 30
      2299772.72     13393651.85      2299704.71     13393695.88
      2299534.13     13393663.67      2299461.68     13393838.49
       2299369.2     13394195.96      2299397.72     13394886.86
      2299270.87     13395283.88      2298964.61     13395998.01
      2299157.32     13396607.91      2299043.22     13396706.09
      2298397.53     13396825.62      2297978.52     13396848.34
      2297835.25     13396900.26      2297830.73     13397467.18
      2297781.82     13397509.37      2297786.12     13397567.55
      2297645.85     13397662.22      2297394.24     13397997.54
      2297266.59      13398004.4      2297261.73     13398100.23
      2297124.23     13398363.42      2296988.81     13398413.42
       2296885.1     13398560.48      2296769.58     13399022.64
      2296786.28     13399126.07      2296530.46     13399457.98
      2296450.13     13399622.48      2296437.01     13399783.19
       2296241.1     13400018.39      2296347.72     13400566.85

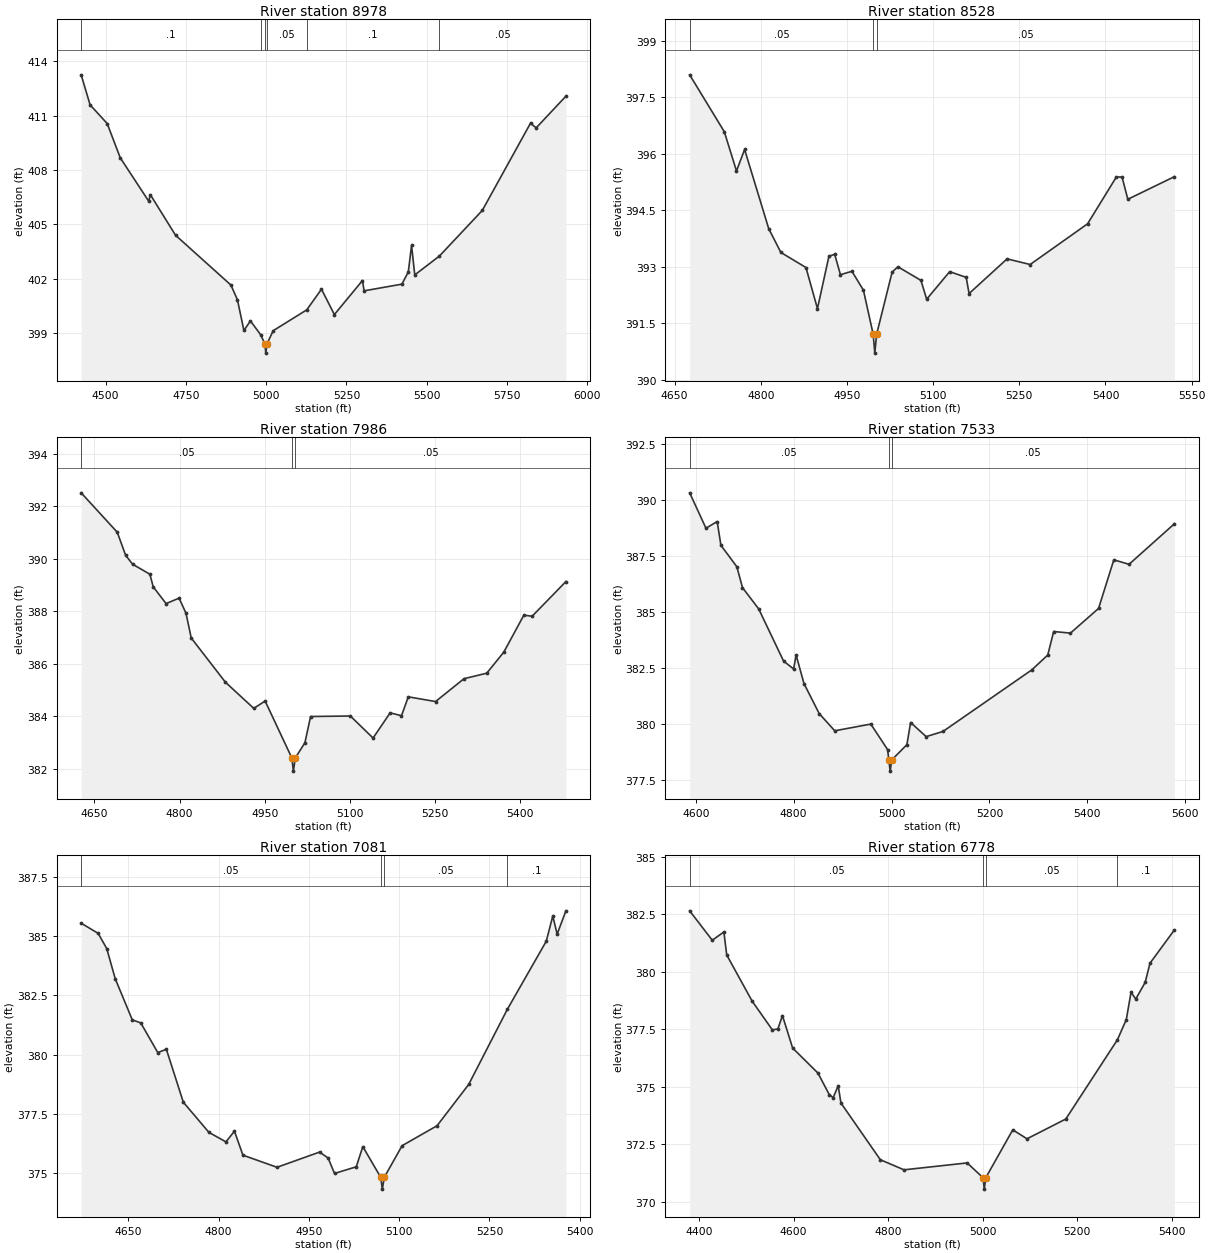
Type RM Length L Ch R = 1 ,8978    ,450,450,450
BEGIN DESCRIPTION:
UNT056 IN SUCR 17.0
END DESCRIPTION:
XS GIS Cut Line= 3
      2299437.71     13393096.82      2299537.72     13393696.85
      2300437.72     13393746.85
#Sta/Elev= 30
  4423.8  413.26  4451.7   411.6  4504.9  410.57  4545.5  408.68  4634.2  406.28
  4639.3  406.64  4717.8   404.4  4890.2  401.65  4910.5  400.84  4930.7  399.14
    4951  399.67  4983.1   398.9  4996.2  398.39  4998.9  397.89  5002.2  398.39
    5022  399.13  5126.4  400.28  5172.3  401.42  5212.4  400.02    5300   401.9
    5305  401.33  5422.7   401.7  5442.7  402.37  5452.8  403.84  5462.8  402.21
  5539.5  403.25  5673.1  405.77  5823.3  410.59  5840.9  410.33  5933.5  412.08
#Mann= 6 ,-1 , 0
  4423.8      .1       0  4983.1     .05       0  4996.2     .03       0
  5002.2     .05       0  5126.4      .1       0  5539.5     .05       0
Bank Sta=4996.2,5002.2
XS Rating Curve= 0 ,0
Exp/Cntr=0.3,0.1

Type RM Length L Ch R = 1 ,8528    ,542,542,542
BEGIN DESCRIPTION:
UNT056 IN SUCR 16.0
END DESCRIPTION:
XS GIS Cut Line= 3
      2299105.83     13393983.53      2299203.48     13394081.18
      2299908.75     13394102.88
#Sta/Elev= 30
  4676.3  398.09  4736.6  396.58  4757.8  395.54  4771.9  396.11  4813.9  394.01
    4835  393.38  4878.7  392.98  4898.7  391.89  4918.7  393.28  4928.7  393.33
  4938.7  392.79  4958.7  392.88  4978.7  392.38  4995.7  391.21  4998.5  390.71
  5001.7  391.21  5028.7  392.86  5038.7     393  5078.8  392.64  5088.8  392.14
  5128.8  392.87  5157.6  392.72  5162.6  392.29  5228.8  393.21  5268.9  393.06
  5368.9  394.14  5418.9  395.38  5428.9  395.38  5438.9  394.79    5520  395.39
#Mann= 3 ,-1 , 0
  4676.3     .05       0  4995.7     .03       0  5001.7     .05       0
Bank Sta=4995.7,5001.7
XS Rating Curve= 0 ,0
Exp/Cntr=0.3,0.1

Type RM Length L Ch R = 1 ,7986    ,453,453,453
BEGIN DESCRIPTION:
UNT056 IN SUCR 15.0
END DESCRIPTION:
XS GIS Cut Line= 3
      2299116.65     13394460.92      2299214.33     13394612.86
      2299887.11     13394645.42
#Sta/Elev= 30
  4626.5  392.51  4690.1  391.01  4704.9  390.13  4717.2  389.79  4747.6  389.41
  4753.5  388.93  4776.2  388.29  4799.1   388.5  4811.3  387.92  4820.5  386.98
  4880.6   385.3  4930.7   384.3  4950.7  384.58  4997.8  382.41  5000.5  381.91
  5003.8  382.41  5020.8  382.99  5030.8  383.99  5100.9  384.01  5140.9  383.17
    5171  384.13    5191  384.02    5203  384.74    5251  384.56  5301.1  385.43
  5341.2  385.64  5371.2  386.44  5406.6  387.85  5421.2  387.81  5480.7  389.13
#Mann= 3 ,-1 , 0
  4626.5     .05       0  4997.8     .03       0  5003.8     .05       0
Bank Sta=4997.8,5003.8
XS Rating Curve= 0 ,0
Exp/Cntr=0.3,0.1

Type RM Length L Ch R = 1 ,7533    ,452,452,452
BEGIN DESCRIPTION:
UNT056 IN SUCR 14.0
END DESCRIPTION:
XS GIS Cut Line= 3
      2299029.87     13394819.04      2299105.82     13394981.79
      2299887.05      13395198.8
#Sta/Elev= 30
  4587.6  390.31  4620.9  388.73  4643.8  389.03  4651.4  387.97    4684  387.01
  4695.5  386.08  4728.6  385.13  4779.5   382.8    4800  382.45  4805.1  383.07
  4821.1   381.8  4852.2  380.46    4884  379.69  4957.7  379.99    4992  378.85
  4994.5  378.39  4997.2  377.89  5000.5  378.39  5031.4  379.07    5039  380.06
  5070.8  379.43  5105.1  379.66  5286.7  382.41  5319.2  383.07  5331.3  384.12
  5365.6  384.05    5423  385.15  5454.2  387.32  5485.3  387.12    5578  388.93
#Mann= 3 ,-1 , 0
  4587.6     .05       0  4994.5     .03       0  5000.5     .05       0
Bank Sta=4994.5,5000.5
XS Rating Curve= 0 ,0
Exp/Cntr=0.3,0.1

Type RM Length L Ch R = 1 ,7081    ,303,303,303
BEGIN DESCRIPTION:
UNT056 IN SUCR 13.0
END DESCRIPTION:
XS GIS Cut Line= 3
      2298887.69     13395146.83      2299187.72     13395446.85
      2299537.73     13395596.86
#Sta/Elev= 30
  4571.8  385.54  4600.1  385.11  4614.3  384.47  4628.4   383.2  4656.7  381.47
  4670.8  381.34  4699.1  380.09  4713.3  380.23  4741.5     378    4784  376.73
  4812.3  376.33  4826.4  376.78  4840.5  375.77  4897.1  375.26  4967.8   375.9
    4982  375.65  4992.6     375  5028.7  375.28  5039.6  376.13  5069.3  374.84
    5072  374.34  5075.3  374.84  5104.9  376.17  5162.9  377.01  5215.5  378.75
  5279.6  381.91  5344.3  384.78  5355.1  385.84  5362.4  385.08  5376.9  386.06
#Mann= 4 ,-1 , 0
  4571.8     .05       0  5069.3     .03       0  5075.3     .05       0
  5279.6      .1       0
Bank Sta=5069.3,5075.3
XS Rating Curve= 0 ,0
Exp/Cntr=0.3,0.1

Type RM Length L Ch R = 1 ,6778    ,345,345,345
BEGIN DESCRIPTION:
Mapping XS e9fff081
END DESCRIPTION:
XS GIS Cut Line= 3
      2298716.78     13395343.74      2298860.02      13395712.7
       2299489.4     13395743.08
#Sta/Elev= 30
  4380.1  382.65  4427.9  381.37  4452.5  381.73  4458.5  380.73  4512.3  378.72
  4555.1  377.47  4566.7  377.51  4576.5  378.09    4598  376.68  4651.6  375.59
  4675.6  374.65  4683.8  374.52  4694.5  375.04  4700.2  374.29  4783.6  371.82
  4833.7  371.38  4967.3  371.68  5000.9  371.04  5003.6  370.54  5006.9  371.04
  5063.9  373.12    5094  372.73  5176.1  373.59  5285.4  377.04  5304.2  377.92
  5314.2  379.11  5324.2  378.81  5344.2  379.54  5354.3  380.37    5406  381.82
#Mann= 4 ,-1 , 0
  4380.1     .05       0  5000.9     .03       0  5006.9     .05       0
  5285.4      .1       0
Bank Sta=5000.9,5006.9
XS Rating Curve= 0 ,0
Exp/Cntr=0.3,0.1

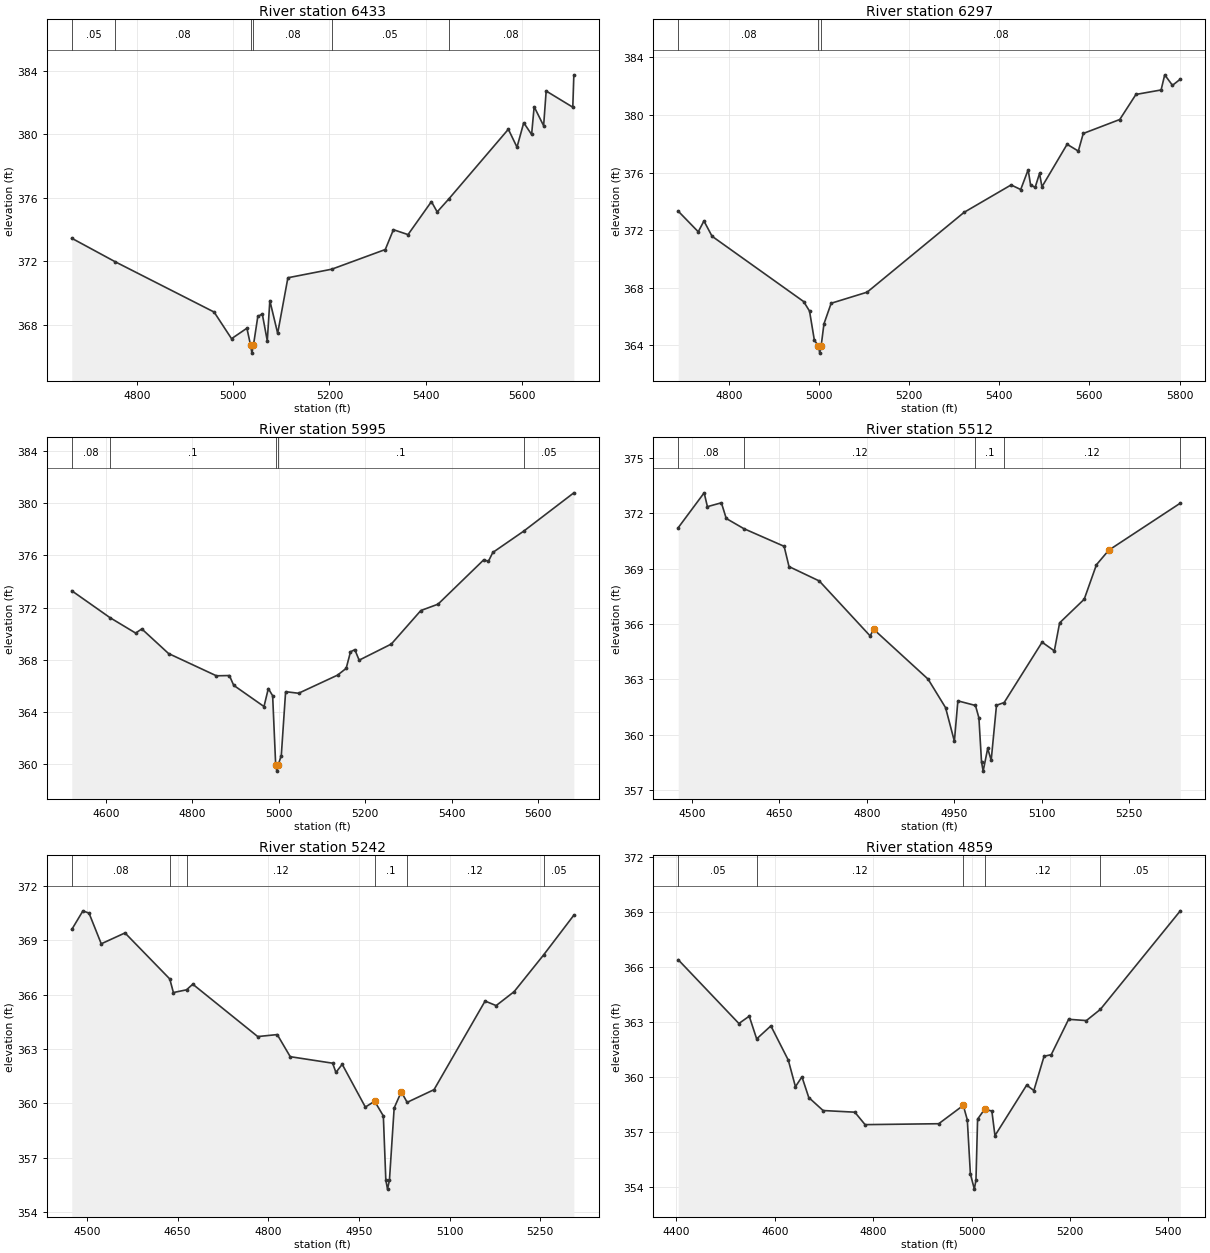
Type RM Length L Ch R = 1 ,6433    ,136,136,136
BEGIN DESCRIPTION:
Mapping XS e79c7c46
END DESCRIPTION:
XS GIS Cut Line= 2
      2298656.07     13396155.39      2299635.51     13395791.35
#Sta/Elev= 30
  4663.7  373.46  4754.6  371.97  4959.9  368.81  4996.2  367.13  5028.2  367.79
  5035.8  366.72  5038.6  366.22  5041.8  366.72  5050.9  368.53  5060.2  368.69
  5070.6  366.99  5075.9  369.53  5092.2  367.47  5113.5  370.97  5204.8  371.51
  5316.2  372.75  5333.1     374  5363.5  373.69  5412.2  375.77  5424.2  375.12
  5447.9  375.92  5572.3  380.33  5590.3   379.2  5604.3  380.74  5620.7     380
    5626  381.75  5645.7  380.55    5651  382.74  5706.4  381.72  5708.6  383.76
#Mann= 6 ,-1 , 0
  4663.7     .05       0  4754.6     .08       0  5035.8     .07       0
  5041.8     .08       0  5204.8     .05       0  5447.9     .08       0
Bank Sta=5035.8,5041.8
XS Rating Curve= 0 ,0
Exp/Cntr=0.3,0.1

Type RM Length L Ch R = 1 ,6297    ,302,302,302
BEGIN DESCRIPTION:
Mapping XS 6349b4b5
END DESCRIPTION:
XS GIS Cut Line= 2
      2298734.16     13396268.25      2299780.21     13395886.29
#Sta/Elev= 30
  4688.1  373.32  4732.5  371.89  4745.1  372.64  4763.1  371.58  4966.2  367.05
  4979.3  366.39    4990  364.37  4999.1  363.97  5001.9  363.47  5005.1  363.97
  5011.3   365.5  5027.3  366.93  5107.1   367.7  5322.2  373.24  5426.4  375.14
  5447.7  374.82  5464.2  376.19  5469.6  375.14  5479.7  374.97  5489.5  375.94
  5494.8  375.01  5550.6  377.96  5575.5  377.49  5586.4  378.71  5667.4  379.68
  5703.3  381.42  5759.1  381.73  5767.1  382.78  5784.3  382.05  5801.7  382.48
#Mann= 3 ,-1 , 0
  4688.1     .08       0  4999.1     .07       0  5005.1     .08       0
Bank Sta=4999.1,5005.1
XS Rating Curve= 0 ,0
Exp/Cntr=0.3,0.1

Type RM Length L Ch R = 1 ,5995    ,483,483,483
BEGIN DESCRIPTION:
UNT056 IN SUCR 12.0
END DESCRIPTION:
XS GIS Cut Line= 4
      2298704.36     13396281.23      2298870.41      13396436.4
      2299382.19     13396452.73      2299787.83     13396335.66
#Sta/Elev= 30
  4521.5  373.29  4609.7  371.23  4669.3  370.04  4683.5  370.36  4745.4  368.47
  4856.1  366.76  4886.1  366.78  4896.1  366.03  4966.2   364.4  4976.2  365.78
  4986.2  365.23  4993.2  359.94  4995.9  359.44  4999.2  359.94  5006.2  360.63
  5016.2  365.54  5046.2  365.42  5136.3  366.81  5156.3  367.33  5166.3   368.6
  5176.3  368.77  5186.3  367.96  5260.8   369.2    5329  371.77  5368.8  372.26
  5474.7  375.67  5485.3  375.55  5495.5  376.23  5566.7  377.86    5683  380.81
#Mann= 5 ,-1 , 0
  4521.5     .08       0  4609.7      .1       0  4993.2     .07       0
  4999.2      .1       0  5566.7     .05       0
Bank Sta=4993.2,4999.2
XS Rating Curve= 0 ,0
Exp/Cntr=0.3,0.1

Type RM Length L Ch R = 1 ,5512    ,270,270,270
BEGIN DESCRIPTION:
UNT056 IN SUCR 11.0
END DESCRIPTION:
XS GIS Cut Line= 3
      2298636.28     13396270.31      2298712.52      13396460.9
      2299073.67     13397009.41
#Sta/Elev= 30
  4476.3  371.23  4520.8  373.12  4526.4  372.37  4550.4  372.58  4558.7  371.73
  4588.8  371.18  4658.1  370.22  4666.5  369.12  4718.5  368.34  4805.8  365.36
  4811.8  365.72  4905.2  363.02  4935.3  361.47  4950.4  359.65  4956.4  361.84
  4986.6  361.59  4992.5  360.92    4997  358.53  4999.8  358.03  5007.6  359.26
  5013.6  358.62  5022.7   361.6  5035.9  361.75    5101  365.02    5122  364.55
  5131.1  366.07  5173.3  367.35  5194.3  369.22  5215.5  370.01  5338.3  372.56
#Mann= 5 ,-1 , 0
  4476.3     .08       0  4588.8     .12       0  4986.6      .1       0
  5035.9     .12       0  5338.3     .05       0
Bank Sta=4811.8,5215.5
XS Rating Curve= 0 ,0
Exp/Cntr=0.3,0.1

Type RM Length L Ch R = 1 ,5242    ,383,383,383
BEGIN DESCRIPTION:
UNT056 IN SUCR 10.0
END DESCRIPTION:
XS GIS Cut Line= 3
      2298481.13     13396278.47      2298505.63     13396471.78
      2298739.08     13397063.54
#Sta/Elev= 30
  4474.7   369.6  4493.2  370.63  4503.3   370.5  4523.5  368.81  4562.8  369.41
  4636.9  366.87  4642.9  366.12  4664.6  366.27    4675  366.58  4782.5  363.69
  4814.8   363.8  4836.3  362.58  4906.5  362.22  4911.9  361.71  4922.3  362.16
  4960.6   359.8    4976  360.12  4990.4  359.31  4994.5  355.77  4997.3  355.27
  5000.5  355.77  5008.3  359.75  5020.1  360.64  5029.8  360.06  5074.3  360.76
  5158.8  365.65  5177.1   365.4  5206.9  366.17  5255.5  368.19  5305.7  370.39
#Mann= 6 ,-1 , 0
  4474.7     .08       0  4636.9      .1       0  4664.6     .12       0
    4976      .1       0  5029.8     .12       0  5255.5     .05       0
Bank Sta=4976,5020.1
XS Rating Curve= 0 ,0
Exp/Cntr=0.3,0.1

Type RM Length L Ch R = 1 ,4859    ,581,581,581
BEGIN DESCRIPTION:
UNT056 IN SUCR 9.0
END DESCRIPTION:
XS GIS Cut Line= 3
       2297773.4     13396479.98      2297917.63     13396580.67
      2298589.62     13397092.14
#Sta/Elev= 30
  4403.9  366.38  4527.2   362.9  4548.2   363.3  4563.3  362.06  4592.2  362.77
  4627.6   360.9  4642.1  359.45  4655.3  359.99  4669.2  358.86  4698.3  358.15
  4762.8  358.06  4783.6  357.38  4933.3  357.43  4983.2  358.43  4991.4  357.64
  4997.7  354.68  5005.7  353.86    5009  354.36  5012.3  357.68  5026.8  358.23
  5041.3  358.12  5047.6  356.78  5112.1  359.54  5126.6  359.24  5147.4  361.11
    5162   361.2  5197.3  363.13  5233.4  363.06  5261.8  363.67  5424.3  369.05
#Mann= 5 ,-1 , 0
  4403.9     .05       0  4563.3     .12       0  4983.2      .1       0
  5026.8     .12       0  5261.8     .05       0
Bank Sta=4983.2,5026.8
XS Rating Curve= 0 ,0
Exp/Cntr=0.3,0.1

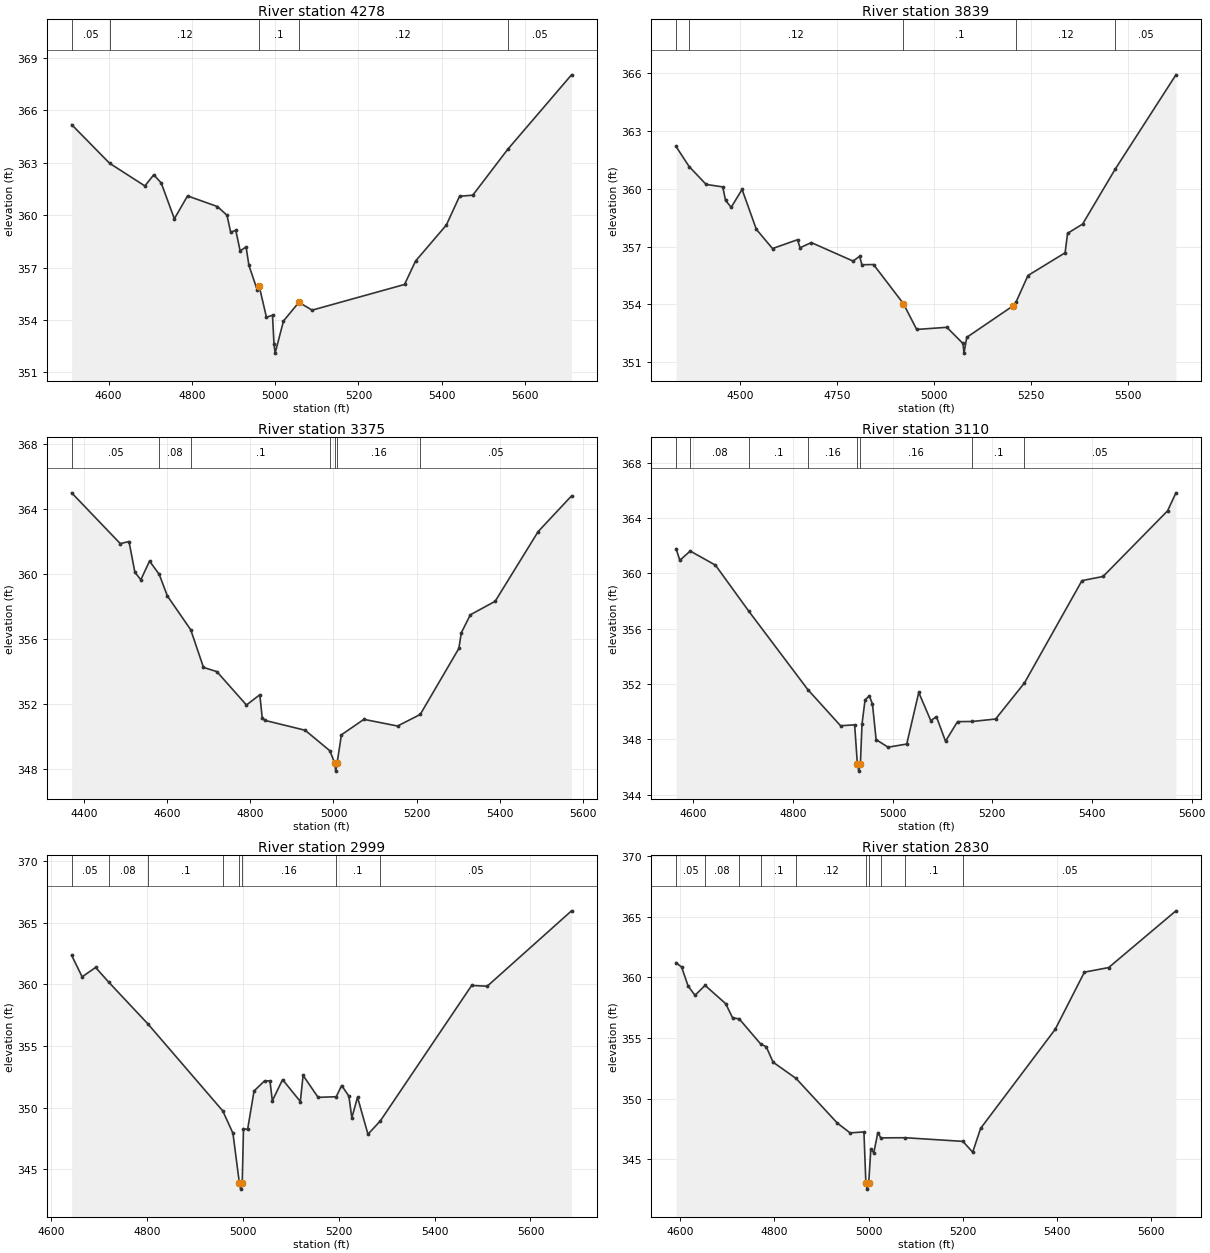
Type RM Length L Ch R = 1 ,4278    ,439,439,439
BEGIN DESCRIPTION:
UNT056 IN SUCR 8.0
END DESCRIPTION:
XS GIS Cut Line= 3
      2297500.07     13396761.17      2297569.52     13396955.62
      2298513.32      13397267.9
#Sta/Elev= 30
  4511.3  365.18  4602.3  362.97  4687.2  361.67  4708.5  362.31  4726.4  361.84
    4758  359.79  4789.6   361.1  4861.5  360.49  4884.4  359.99  4893.2  359.02
  4905.5  359.13    4916  357.95  4930.2  358.18  4937.1  357.12  4956.7  355.74
  4961.9  355.92  4979.2  354.15  4993.7  354.27  4997.3   352.6    5000   352.1
  5020.1  353.94  5057.1  355.01  5088.8  354.56  5310.8  356.03  5337.3  357.37
  5411.2  359.43    5443  361.08  5474.7  361.14  5558.5  363.76  5711.9  368.03
#Mann= 5 ,-1 , 0
  4511.3     .05       0  4602.3     .12       0  4961.9      .1       0
  5057.1     .12       0  5558.5     .05       0
Bank Sta=4961.9,5057.1
XS Rating Curve= 0 ,0
Exp/Cntr=0.3,0.1

Type RM Length L Ch R = 1 ,3839    ,464,464,464
BEGIN DESCRIPTION:
UNT056 IN SUCR 7.0
END DESCRIPTION:
XS GIS Cut Line= 3
      2297270.93     13397115.36      2297618.13     13397372.28
      2298388.94     13397747.27
#Sta/Elev= 30
  4335.1   362.2  4368.7  361.16  4412.6  360.23  4455.5   360.1  4462.7   359.4
  4477.3  359.04  4505.3  359.97  4542.1   357.9  4583.8   356.9  4648.5  357.36
  4654.7  356.94  4683.9  357.21  4791.6  356.25  4808.6   356.5  4814.2  356.06
  4844.4  356.07  4921.4  354.04  4955.6   352.7  5033.5  352.81  5074.9  351.97
  5077.7  351.47  5084.8  352.29  5203.1  353.91  5211.4   354.1  5242.6   355.5
  5338.4  356.68  5344.8  357.69  5383.5  358.17  5467.2  361.01  5624.2  365.92
#Mann= 5 ,-1 , 0
  4335.1     .05       0  4368.7     .12       0  4921.4      .1       0
  5211.4     .12       0  5467.2     .05       0
Bank Sta=4921.4,5203.1
XS Rating Curve= 0 ,0
Exp/Cntr=0.3,0.1

Type RM Length L Ch R = 1 ,3375    ,265,265,265
BEGIN DESCRIPTION:
UNT056 IN SUCR 6.0
END DESCRIPTION:
XS GIS Cut Line= 3
      2297027.89     13397462.59      2297208.41     13397615.34
      2298054.19     13398079.82
#Sta/Elev= 30
  4370.8  364.98  4487.7  361.86  4508.6  361.99  4522.8   360.1  4537.1  359.64
    4558  360.79  4581.3  359.97  4600.8  358.65    4657  356.57  4687.6  354.26
  4719.8     354  4790.9  351.95    4823  352.58  4828.8  351.17  4834.7  351.01
    4932   350.4  4991.4  349.14  5002.8  348.39  5005.5  347.89  5008.8  348.39
  5019.2  350.12  5073.2  351.07  5154.1  350.66  5208.6  351.37  5301.5  355.43
  5307.2  356.38    5329  357.49  5388.7  358.32    5492   362.6  5572.2  364.79
#Mann= 7 ,-1 , 0
  4370.8     .05       0  4581.3     .08       0    4657      .1       0
  4991.4     .16       0  5002.8     .07       0  5008.8     .16       0
  5208.6     .05       0
Bank Sta=5002.8,5008.8
XS Rating Curve= 0 ,0
Exp/Cntr=0.3,0.1

Type RM Length L Ch R = 1 ,3110    ,111,111,111
BEGIN DESCRIPTION:
Mapping XS 478cdcae
END DESCRIPTION:
XS GIS Cut Line= 3
      2297028.42      13397756.1      2297359.16     13397990.47
      2297913.24     13398214.19
#Sta/Elev= 30
  4565.6  361.79  4573.2  360.95    4594  361.62  4644.6   360.6  4711.9  357.25
  4829.9   351.6  4895.7  348.98  4923.9  349.05  4929.4   346.2  4932.2   345.7
  4935.4   346.2  4938.7  349.11  4944.8  350.86  4953.4  351.14  4959.6  350.56
    4967  347.98    4991  347.43  5028.4  347.66  5052.5  351.39  5076.7  349.35
    5088  349.64  5106.2  347.86  5130.3  349.28  5159.9  349.29  5206.7  349.47
  5264.6  352.08    5380  359.48  5422.4  359.78  5551.8  364.53  5568.5  365.83
#Mann= 8 ,-1 , 0
  4565.6     .05       0    4594     .08       0  4711.9      .1       0
  4829.9     .16       0  4929.4     .07       0  4935.4     .16       0
  5159.9      .1       0  5264.6     .05       0
Bank Sta=4929.4,4935.4
XS Rating Curve= 0 ,0
Exp/Cntr=0.3,0.1

Type RM Length L Ch R = 1 ,2999    ,169,169,169
BEGIN DESCRIPTION:
UNT056 IN SUCR 5.0
END DESCRIPTION:
XS GIS Cut Line= 5
      2296987.71     13397796.85      2297221.14     13397972.25
       2297325.3     13398026.93      2297478.95     13398118.08
       2297913.3     13398253.33
#Sta/Elev= 30
  4642.4  362.35  4664.3  360.61  4692.4  361.37  4719.7  360.18  4801.4   356.8
  4957.8  349.74    4979  347.93  4992.4   343.9  4995.1   343.4  4998.4   343.9
    5001   348.3  5009.6  348.24  5023.1  351.36  5045.1  352.18  5056.3  352.17
  5061.2  350.56  5082.6  352.28  5119.6   350.5  5125.4  352.62  5156.7  350.84
  5194.5  350.89    5206   351.8    5221  350.93  5227.1  349.18    5239  350.85
  5260.8  347.85  5286.4  348.92  5477.2  359.91  5509.7  359.85  5685.6  365.96
#Mann= 8 ,-1 , 0
  4642.4     .05       0  4719.7     .08       0  4801.4      .1       0
  4957.8     .16       0  4992.4     .07       0  4998.4     .16       0
  5194.5      .1       0  5286.4     .05       0
Bank Sta=4992.4,4998.4
XS Rating Curve= 0 ,0
Exp/Cntr=0.3,0.1

Type RM Length L Ch R = 1 ,2830    ,391,391,391
BEGIN DESCRIPTION:
Mapping XS ada26397
END DESCRIPTION:
XS GIS Cut Line= 3
      2296898.18     13397909.72      2297314.89     13398209.22
      2297846.16     13398342.04
#Sta/Elev= 30
  4591.6  361.21  4603.4  360.85  4617.1  359.29  4631.8  358.52  4653.2  359.34
  4696.9  357.83  4711.6  356.66  4725.5  356.58  4771.7  354.48  4782.8  354.29
  4797.6     353  4846.3  351.66  4933.8  347.98  4960.9  347.17  4990.3  347.25
  4994.4  343.03  4997.2  342.53  5000.4  343.03    5005  345.86  5011.2  345.52
  5019.8   347.2  5026.1  346.76  5078.2  346.77  5200.3  346.47  5221.1  345.58
  5237.9  347.54  5396.3  355.72  5458.2  360.43  5509.7  360.81  5652.4  365.49
#Mann= 10 ,-1 , 0
  4591.6     .05       0  4653.2     .08       0  4725.5     .05       0
  4771.7      .1       0  4846.3     .12       0  4994.4     .07       0
  5000.4     .12       0  5026.1     .16       0  5078.2      .1       0
  5200.3     .05       0
Bank Sta=4994.4,5000.4
XS Rating Curve= 0 ,0
Exp/Cntr=0.3,0.1

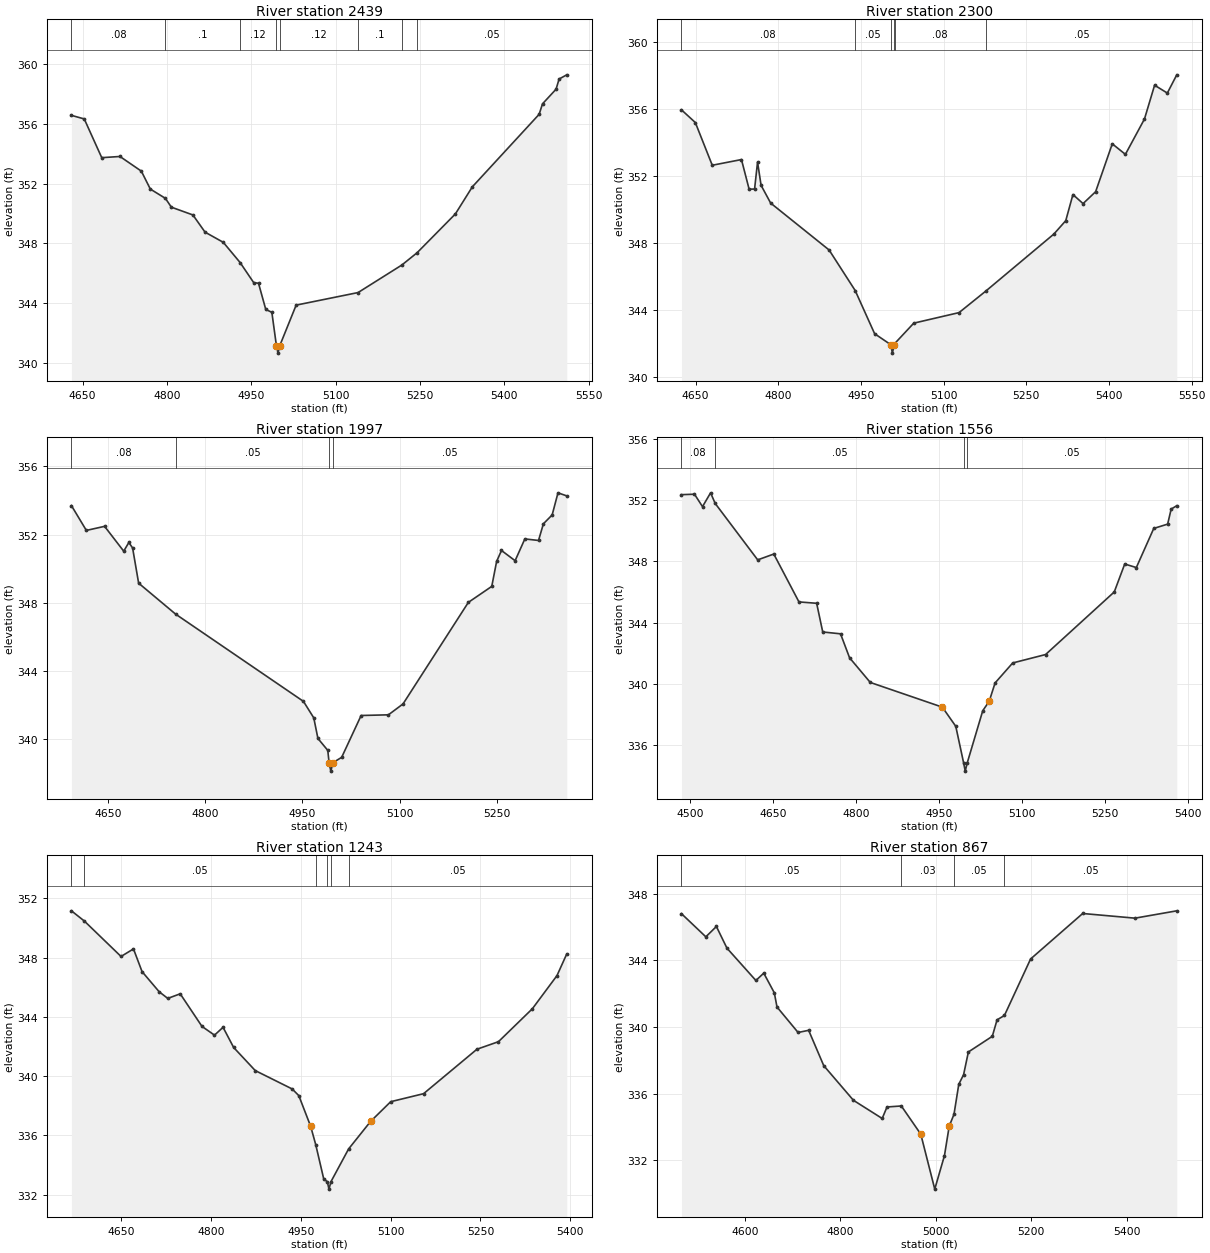
Type RM Length L Ch R = 1 ,2439    ,139,139,139
BEGIN DESCRIPTION:
UNT056 IN SUCR 4.0
END DESCRIPTION:
XS GIS Cut Line= 2
      2296657.81      13398264.8      2297473.19     13398597.89
#Sta/Elev= 30
  4630.1  356.56  4652.9  356.32    4684  353.73  4716.4  353.81  4754.4  352.83
  4770.4  351.63  4797.2  351.01  4807.8  350.42  4846.1   349.9  4867.7  348.75
  4900.1  348.07    4930  346.72  4954.1  345.38  4962.8  345.33  4975.7  343.58
  4986.5  343.39  4994.6  341.16  4997.4  340.66  5000.6  341.16  5029.7  343.87
  5139.8  344.71  5217.6  346.55  5244.7  347.37  5312.9  349.97    5343  351.78
  5461.8  356.63  5467.8  357.33  5491.9  358.31  5497.3  358.99  5510.9  359.27
#Mann= 8 ,-1 , 0
  4630.1     .08       0  4797.2      .1       0    4930     .12       0
  4994.6     .07       0  5000.6     .12       0  5139.8      .1       0
  5217.6     .08       0  5244.7     .05       0
Bank Sta=4994.6,5000.6
XS Rating Curve= 0 ,0
Exp/Cntr=0.3,0.1

Type RM Length L Ch R = 1 ,2300    ,303,303,303
BEGIN DESCRIPTION:
Mapping XS 436290e1
END DESCRIPTION:
XS GIS Cut Line= 2
      2296574.43     13398368.94      2297403.48     13398715.83
#Sta/Elev= 30
  4624.3  355.94  4649.5  355.18  4680.2  352.63  4733.2  352.97  4747.1   351.2
    4757  351.21  4762.4  352.82  4768.8  351.43  4786.2  350.37  4892.2  347.57
  4939.5  345.15  4974.8  342.57  5004.3  341.91    5007  341.41  5010.3  341.91
  5011.2  341.98  5045.8   343.2    5128  343.83  5176.7  345.12    5300  348.52
  5321.6  349.32  5334.6  350.88    5353  350.34  5375.8  351.05    5406  353.91
  5429.8  353.28  5464.4  355.39  5482.8  357.41  5505.9  356.94    5523  358.03
#Mann= 6 ,-1 , 0
  4624.3     .08       0  4939.5     .05       0  5004.3     .03       0
  5010.3     .05       0  5011.2     .08       0  5176.7     .05       0
Bank Sta=5004.3,5010.3
XS Rating Curve= 0 ,0
Exp/Cntr=0.3,0.1

Type RM Length L Ch R = 1 ,1997    ,441,441,441
BEGIN DESCRIPTION:
UNT056 IN SUCR 3.0
END DESCRIPTION:
XS GIS Cut Line= 3
      2296487.75     13398596.87      2296837.72     13398796.85
       2297137.7     13398996.84
#Sta/Elev= 30
  4593.9   353.7  4616.9  352.24    4645  352.48  4674.5  351.02  4682.4  351.53
  4688.2  351.21  4697.5  349.14  4754.5  347.32  4951.6  342.19  4967.5  341.22
  4973.9  340.01  4989.1  339.31  4991.1  338.59  4993.8  338.09  4997.1  338.59
  5010.5   338.9  5040.5  341.36  5082.6   341.4  5105.1  342.04  5205.8  348.01
  5241.9  348.95  5249.4  350.42  5256.9  351.06  5277.9  350.46  5292.9  351.74
    5314  351.65  5321.5  352.63    5335  353.15    5344  354.45  5357.5  354.27
#Mann= 4 ,-1 , 0
  4593.9     .08       0  4754.5     .05       0  4991.1     .03       0
  4997.1     .05       0
Bank Sta=4991.1,4997.1
XS Rating Curve= 0 ,0
Exp/Cntr=0.3,0.1

Type RM Length L Ch R = 1 ,1556    ,313,313,313
BEGIN DESCRIPTION:
UNT056 IN SUCR 2.0
END DESCRIPTION:
XS GIS Cut Line= 4
       2296319.5      13398941.7      2296430.63     13399087.56
      2296923.69     13399282.01      2297097.33     13399226.44
#Sta/Elev= 30
  4484.5  352.34  4508.1  352.37  4522.6  351.56  4537.2  352.46  4545.5  351.77
  4622.4  348.09  4651.5  348.47    4697  345.35    4729  345.26    4740  343.39
  4772.2  343.27  4788.5  341.71    4826   340.1  4956.3  338.49  4980.6  337.24
    4995  334.82  4997.7  334.32    5001  334.82  5029.4  338.26    5041  338.87
  5051.7  340.07  5083.5  341.37    5143  341.92  5267.2     346  5286.1  347.82
  5307.1  347.59  5338.6  350.14  5363.7  350.42  5370.1   351.4  5380.2  351.62
#Mann= 4 ,-1 , 0
  4484.5     .08       0  4545.5     .05       0    4995     .03       0
    5001     .05       0
Bank Sta=4956.3,5041
XS Rating Curve= 0 ,0
Exp/Cntr=0.3,0.1

Type RM Length L Ch R = 1 ,1243    ,376,376,376
BEGIN DESCRIPTION:
Mapping XS ce4a4513
END DESCRIPTION:
XS GIS Cut Line= 3
      2296209.16     13399198.81      2296382.77     13399407.14
      2296923.57     13399538.87
#Sta/Elev= 30
  4566.5  351.15  4588.1  350.46  4649.4  348.07  4670.2  348.58  4684.5  347.05
  4713.1  345.69  4727.5  345.24  4748.3  345.55  4784.7  343.35  4805.6  342.76
  4819.9  343.29  4837.6  341.93  4873.7  340.37  4935.4  339.13  4946.5  338.68
  4966.3  336.61  4974.8  335.37  4988.2  333.05  4994.2  332.87  4996.9  332.37
  5000.2  332.87  5029.7  335.08  5066.5  336.94  5100.1  338.27    5155  338.81
  5244.2  341.81  5280.2  342.32  5336.8  344.54    5378  346.78  5394.3  348.24
#Mann= 6 ,-1 , 0
  4566.5     .08       0  4588.1     .05       0  4974.8      .1       0
  4994.2     .07       0  5000.2      .1       0  5029.7     .05       0
Bank Sta=4966.3,5066.5
XS Rating Curve= 0 ,0
Exp/Cntr=0.3,0.1

Type RM Length L Ch R = 1 ,867     ,298,298,298
BEGIN DESCRIPTION:
Mapping XS 3d33cd59
END DESCRIPTION:
XS GIS Cut Line= 4
      2296091.09     13399462.68      2296257.77     13399782.14
      2296646.66     13399809.92      2296889.72     13399657.14
#Sta/Elev= 30
  4467.4  346.81  4518.5  345.42  4540.6  346.04  4562.7  344.74  4623.3   342.8
  4639.8  343.24  4661.9  342.06  4667.5  341.21  4711.7  339.68  4733.8  339.81
  4765.4  337.69  4827.6  335.61  4887.8  334.52  4897.9  335.21  4927.9  335.27
  4968.6  333.58  4997.9  330.28  5018.2  332.29  5028.2  334.06  5038.2  334.77
  5048.2  336.57  5058.3  337.15  5068.3  338.51  5118.4  339.45  5128.4  340.44
  5143.8   340.7  5198.6  344.09  5307.7  346.82  5417.2  346.54  5504.7  346.98
#Mann= 4 ,-1 , 0
  4467.4     .05       0  4927.9     .03       0  5038.2     .05       0
  5143.8     .05       0
Bank Sta=4968.6,5028.2
XS Rating Curve= 0 ,0
Exp/Cntr=0.3,0.1

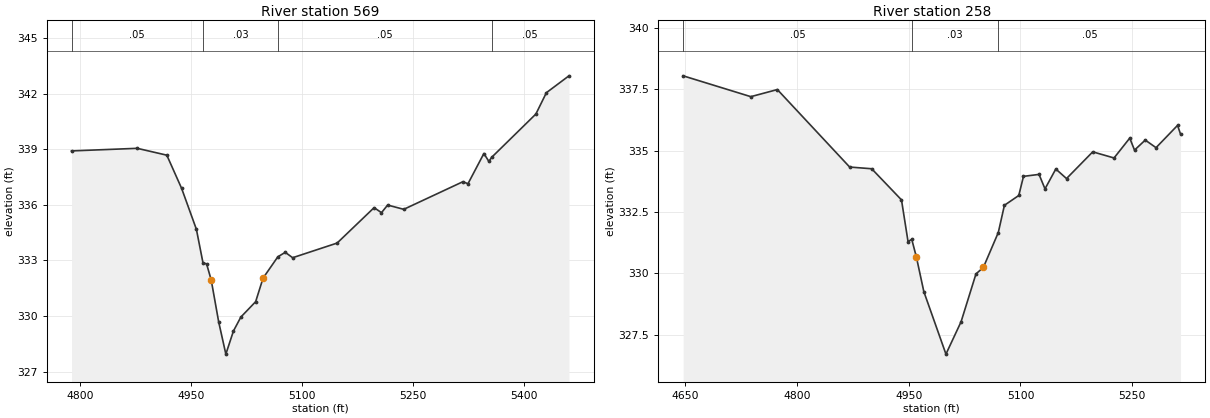
Type RM Length L Ch R = 1 ,569     ,311,311,311
BEGIN DESCRIPTION:
Mapping XS c2fe38e3
END DESCRIPTION:
XS GIS Cut Line= 3
      2296029.03     13400014.57      2296515.16     13400034.11
      2296651.91     13399908.21
#Sta/Elev= 30
  4788.6  338.91  4877.4  339.05  4917.4  338.68  4937.4  336.89  4957.4  334.68
  4966.2  332.89  4971.2  332.81  4977.4  331.95  4987.5  329.69  4997.2  327.95
  5007.5   329.2  5017.5  329.95  5037.5  330.78  5047.5  332.05  5067.5   333.2
  5077.5  333.44  5087.5  333.15  5147.6  333.94  5197.6  335.85  5207.6  335.58
  5215.9  335.99  5237.7  335.76  5317.7  337.25  5324.5  337.14    5346  338.77
  5352.8  338.34  5356.4  338.56  5416.3   340.9  5430.5  342.05    5461  342.96
#Mann= 4 ,-1 , 0
  4788.6     .05       0  4966.2     .03       0  5067.5     .05       0
  5356.4     .05       0
Bank Sta=4977.4,5047.5
XS Rating Curve= 0 ,0
Exp/Cntr=0.3,0.1

Type RM Length L Ch R = 1 ,258     ,0,0,0
BEGIN DESCRIPTION:
UNT056 IN SUCR 1.0
END DESCRIPTION:
XS GIS Cut Line= 4
      2296056.39     13400142.05      2296188.95     13400323.11
      2296399.12     13400319.87      2296543.69     13400136.75
#Sta/Elev= 30
    4647  338.05  4737.9   337.2  4773.5  337.49  4870.6  334.33  4900.2  334.26
  4940.2  332.99    4949  331.29    4954  331.38  4960.2  330.66  4970.2  329.25
  4999.9   326.7  5020.2  328.02  5040.2  329.97  5050.2  330.24  5070.2  331.66
  5078.4  332.77  5097.7  333.17    5104  333.95  5124.9  334.03  5132.9  333.44
  5147.4  334.25  5161.8  333.86    5197  334.95  5225.6   334.7  5246.7  335.51
  5253.1  335.02  5267.5  335.43    5282  335.12  5310.9  336.03  5314.9  335.67
#Mann= 3 ,-1 , 0
    4647     .05       0    4954     .03       0  5070.2     .05       0
Bank Sta=4960.2,5050.2
XS Rating Curve= 0 ,0
Exp/Cntr=0.3,0.1

Chan Stop Cuts=-1
Use User Specified Reach Order=0
Composite Channel Slope=5