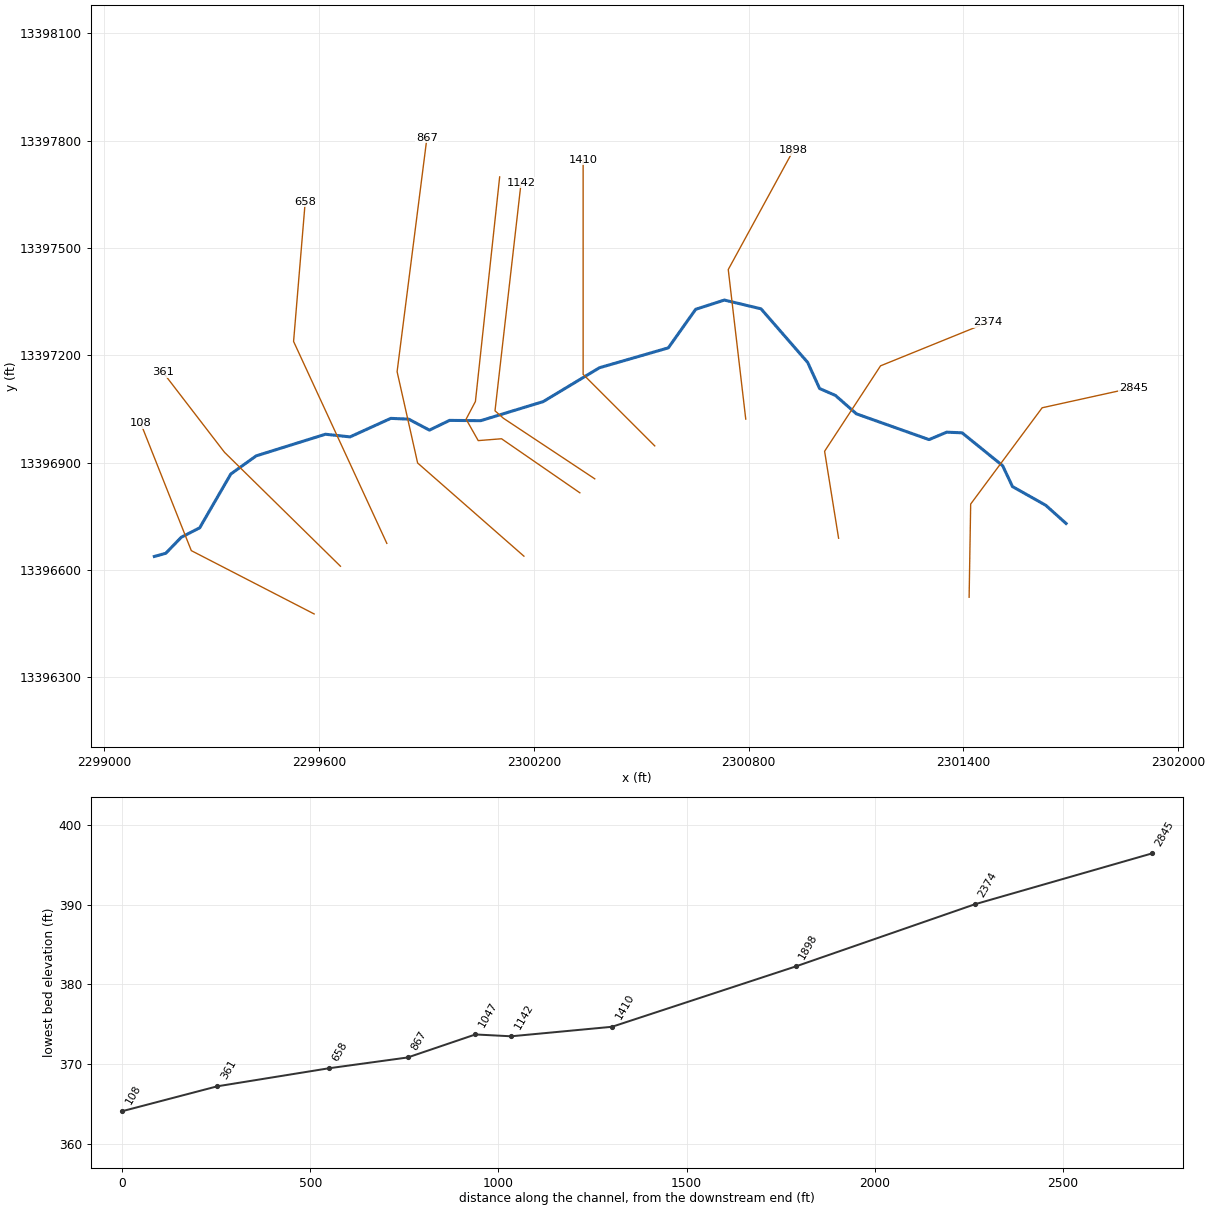
--- UNT057 IN SUCR.prj (project) ---

Proj Title=UNT057 IN SUCR Base Level Engineering
Current Plan=p01
Default Exp/Contr=0.3,0.1
English Units
Geom File=g01
Flow File=f01
Plan File=p01
Y Axis Title=Elevation
X Axis Title(PF)=Main Channel Distance
X Axis Title(XS)=Station
BEGIN DESCRIPTION:
UNT057 IN SUCR
END DESCRIPTION:
DSS Export Rating Curves= 0
DSS Export Rating Curve Sorted= 0
DSS Export Volume Flow Curves= 0
DXF OffsetX= 0
DXF OffsetY= 0
DXF ScaleX= 1
DXF ScaleY= 10

--- UNT057 IN SUCR.p01 (plan) ---

Plan Title=Multiple Run
Short Identifier=Multiple
Geom File=g01
Flow File=f01
Subcritical Flow
K Sum by GR= 0
Std Step Tol= 0.01
Critical Tol= 0.01
Num of Std Step Trials= 20
Max Error Tol= 0.3
Flow Tol Ratio= 0.001
Split Flow NTrial= 30
Split Flow Tol= 0.02
Split Flow Ratio= 0.02
Log Output Level= 0
Friction Slope Method= 1
Unsteady Friction Slope Method= 2
Unsteady Bridges Friction Slope Method= 1
Parabolic Critical Depth
Global Vel Dist=  1 , 1 , 1
Global Log Level= 0
CheckData=True
Encroach Param= -1, 0, 0, 0
BEGIN DESCRIPTION:
Multiple Run
END DESCRIPTION:

--- UNT057 IN SUCR.f01 (steady flow) ---

Flow Title=Multiple
Program Version=4.10
Number of Profiles= 7
Profile Names=10-year,25-year,50-year,1pct_min,100-year,1pct_plu,500-year
River Rch & RM=UNT057 IN SUCR,Reach-1         ,2845
     345     474     578     518     700     947    1027
Boundary for River Rch & Prof#=UNT057 IN SUCR,Reach-1         , 1
Up Type= 0
Dn Type= 3
Dn Slope=0.015
Boundary for River Rch & Prof#=UNT057 IN SUCR,Reach-1         , 2
Up Type= 0
Dn Type= 3
Dn Slope=0.015
Boundary for River Rch & Prof#=UNT057 IN SUCR,Reach-1         , 3
Up Type= 0
Dn Type= 3
Dn Slope=0.015
Boundary for River Rch & Prof#=UNT057 IN SUCR,Reach-1         , 4
Up Type= 0
Dn Type= 3
Dn Slope=0.015
Boundary for River Rch & Prof#=UNT057 IN SUCR,Reach-1         , 5
Up Type= 0
Dn Type= 3
Dn Slope=0.015
Boundary for River Rch & Prof#=UNT057 IN SUCR,Reach-1         , 6
Up Type= 0
Dn Type= 3
Dn Slope=0.015
Boundary for River Rch & Prof#=UNT057 IN SUCR,Reach-1         , 7
Up Type= 0
Dn Type= 3
Dn Slope=0.015
DSS Import GetInterval= 0
DSS Import GetPeak= 0
DSS Import FillOption= 0

--- UNT057 IN SUCR.g01 (geometry) ---

Geom Title=Existing Conditions
Program Version=4.10

River Reach=UNT057 IN SUCR  ,Reach-1
Reach XY= 30
      2301686.56     13396730.07      2301629.82     13396780.88
       2301536.9      13396833.2      2301509.45     13396891.47
      2301396.14     13396983.44      2301353.08     13396985.16
      2301303.86     13396964.44      2301101.04     13397036.41
      2301042.36     13397087.91      2300998.22     13397107.15
      2300964.92     13397180.02      2300834.55     13397329.96
      2300732.17     13397354.39      2300652.08     13397328.62
       2300575.6     13397220.79      2300383.36      13397165.3
       2300226.1     13397070.58      2300051.38     13397017.28
      2299964.57     13397018.15      2299908.45     13396990.95
      2299850.42     13397021.62      2299800.51     13397023.79
      2299686.63     13396972.03      2299618.06     13396979.43
      2299424.62     13396919.03       2299353.7     13396868.28
       2299266.8     13396717.94      2299215.26     13396691.47
      2299172.06     13396646.76      2299140.14     13396637.84

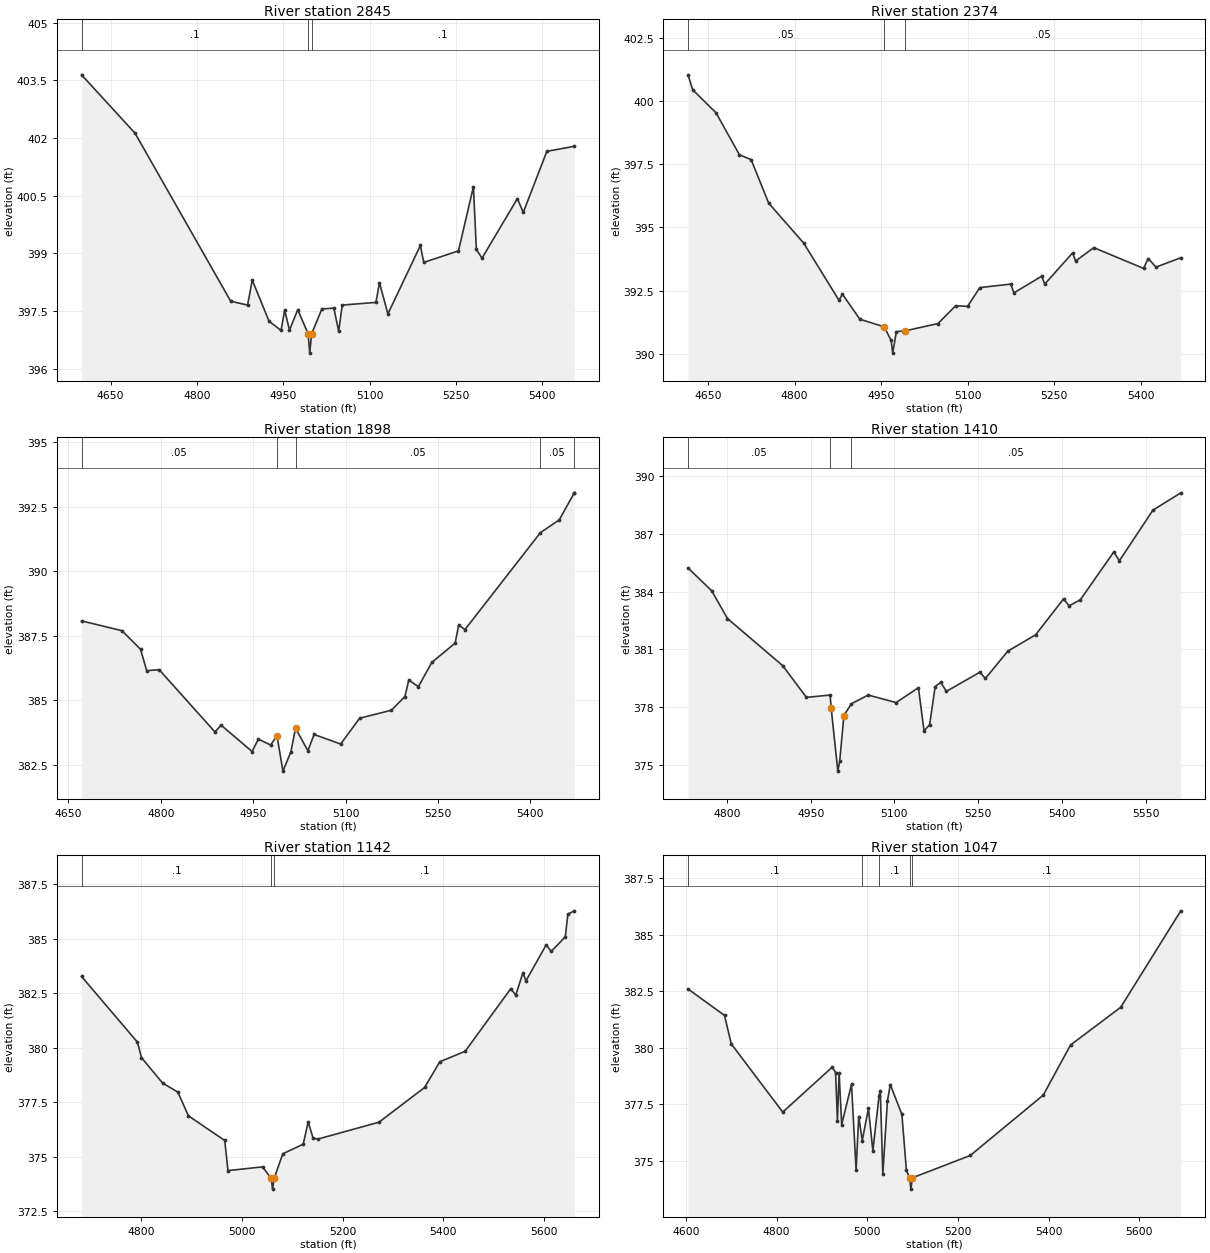
Type RM Length L Ch R = 1 ,2845    ,471,471,471
BEGIN DESCRIPTION:
UNT057 IN SUCR 6.0
END DESCRIPTION:
XS GIS Cut Line= 4
       2301415.8     13396523.87      2301420.14     13396784.31
      2301619.79     13397053.41      2301874.33     13397109.49
#Sta/Elev= 30
  4599.6  403.64  4692.6  402.12  4858.8  397.75  4888.1  397.65  4896.2   398.3
  4925.4  397.23  4946.3  396.99  4952.5  397.52  4960.9     397  4975.3  397.53
  4993.3   396.9  4996.1   396.4  4999.3   396.9  5017.2  397.55    5038  397.57
  5046.4  396.97  5052.6  397.65  5111.1  397.72  5117.3  398.23  5131.9  397.42
  5188.3   399.2  5194.2  398.76  5254.5  399.06  5280.5  400.73  5285.6   399.1
  5295.4  398.87  5356.9  400.42  5367.1  400.06  5408.1  401.65  5455.8  401.78
#Mann= 3 ,-1 , 0
  4599.6      .1       0  4993.3     .07       0  4999.3      .1       0
Bank Sta=4993.3,4999.3
XS Rating Curve= 0 ,0
Exp/Cntr=0.3,0.1

Type RM Length L Ch R = 1 ,2374    ,476,476,476
BEGIN DESCRIPTION:
UNT057 IN SUCR 5.0
END DESCRIPTION:
XS GIS Cut Line= 4
      2301051.21     13396688.87      2301012.15     13396931.88
       2301168.4      13397170.6      2301467.57       13397292.
#Sta/Elev= 30
  4615.3  401.03  4623.4  400.44  4663.8  399.53  4704.4  397.87  4724.7  397.68
  4755.1  395.96  4815.8  394.38    4877  392.12    4883  392.36  4913.2  391.37
  4955.4  391.07  4967.5  390.53  4970.2  390.03  4976.5  390.88  4991.6  390.91
  5048.8   391.2  5079.1   391.9  5100.1  391.88  5121.2  392.62  5174.8  392.76
  5180.2  392.41  5228.4  393.07  5233.8  392.76    5282  393.99  5287.4  393.67
  5318.7   394.2    5405  393.38  5413.2  393.77  5426.6  393.43  5469.6   393.8
#Mann= 3 , 0 , 0
  4615.3     .05       0  4955.4     .03       0  4991.6     .05       0
Bank Sta=4955.4,4991.6
XS Rating Curve= 0 ,0
Exp/Cntr=0.3,0.1

Type RM Length L Ch R = 1 ,1898    ,488,488,488
BEGIN DESCRIPTION:
UNT057 IN SUCR 4.0
END DESCRIPTION:
XS GIS Cut Line= 3
      2300791.91     13397021.74      2300743.05     13397439.69
      2300924.78     13397772.85
#Sta/Elev= 30
  4671.3  388.07  4736.9  387.69  4767.1  386.97  4777.1  386.14  4797.3  386.18
  4887.9  383.77    4898  384.03  4948.3  383.01  4958.4  383.49  4978.5  383.26
  4988.6  383.63  4998.4  382.25  5011.3     383  5018.8  383.91  5038.9  383.04
    5049  383.67  5092.1   383.3    5123   384.3  5174.6  384.61  5196.5  385.14
  5202.8  385.78  5218.3  385.52  5240.1  386.46  5278.1  387.21  5283.8  387.92
  5293.9  387.73  5416.6  391.49  5447.1  391.98  5471.3  393.02  5471.6  393.03
#Mann= 5 ,-1 , 0
  4671.3     .05       0  4988.6     .03       0  5018.8     .05       0
  5416.6     .05       0  5471.3      .1       0
Bank Sta=4988.6,5018.8
XS Rating Curve= 0 ,0
Exp/Cntr=0.3,0.1

Type RM Length L Ch R = 1 ,1410    ,268,268,268
BEGIN DESCRIPTION:
UNT057 IN SUCR 3.0
END DESCRIPTION:
XS GIS Cut Line= 3
      2300537.72     13396946.86      2300337.72     13397146.85
      2300337.72     13397746.82
#Sta/Elev= 30
  4730.2  385.22  4772.6  384.04  4800.9   382.6  4899.9  380.16  4942.3  378.52
  4984.8  378.64 4986.59  377.98  4998.6   374.7  5001.9   375.2  5009.5  377.58
    5023  378.19    5053  378.64    5103  378.25    5143  379.02    5153  376.79
    5163   377.1    5173  379.08    5183   379.3    5193  378.83    5253  379.82
    5263   379.5    5303  380.91    5353  381.76    5403  383.62    5413  383.26
    5433  383.57    5493  386.05    5503  385.59    5563  388.21    5613  389.11
#Mann= 3 ,-1 , 0
  4730.2     .05       0  4984.8     .03       0    5023     .05       0
Bank Sta=4986.59,5009.5
XS Rating Curve= 0 ,0
Exp/Cntr=0.3,0.1

Type RM Length L Ch R = 1 ,1142    ,95,95,95
BEGIN DESCRIPTION:
Mapping XS de723552
END DESCRIPTION:
XS GIS Cut Line= 4
      2300370.24     13396854.83      2300115.02     13397024.11
      2300091.58     13397044.94      2300164.43     13397682.38
#Sta/Elev= 30
  4681.2  383.26  4792.2  380.25  4800.3  379.54  4842.4  378.37  4872.5  377.96
  4893.6  376.87  4965.7  375.74  4972.2  374.36  5040.9  374.53    5058  374.01
  5060.7  373.51    5064  374.01  5081.1  375.13  5121.7  375.57  5131.5  376.59
  5141.5  375.84  5151.6  375.81  5272.4  376.58  5362.9  378.17  5393.1  379.35
  5443.5  379.83  5534.1   382.7  5544.1  382.41  5558.3  383.43  5564.3  383.06
  5604.5  384.71  5614.6  384.41  5642.5  385.08  5647.6  386.12  5660.4  386.27
#Mann= 3 ,-1 , 0
  4681.2      .1       0    5058     .07       0    5064      .1       0
Bank Sta=5058,5064
XS Rating Curve= 0 ,0
Exp/Cntr=0.3,0.1

Type RM Length L Ch R = 1 ,1047    ,180,180,180
BEGIN DESCRIPTION:
UNT057 IN SUCR 2.0
END DESCRIPTION:
XS GIS Cut Line= 6
      2300328.53      13396815.8      2300109.81     13396966.82
       2300044.7     13396961.61      2300010.85     13397021.51
      2300036.89     13397070.99       2300104.6     13397698.62
#Sta/Elev= 30
  4604.5   382.6    4685  381.43  4699.9  380.17  4813.5  377.15  4922.6  379.14
  4930.1   378.9  4934.1  376.77  4937.8   378.9  4943.5   376.6  4965.2  378.38
  4975.3  374.58  4981.1  376.95  4988.9  375.89  5002.5  377.31  5012.3  375.44
    5026  377.88  5028.7   378.1  5034.3  374.41  5044.4  377.63  5050.7  378.37
  5076.3  377.05  5086.3  374.57  5093.4  374.24  5096.2  373.74  5099.4  374.24
  5227.2  375.23  5388.1   377.9  5448.4  380.12  5559.1  381.79  5691.6  386.06
#Mann= 5 ,-1 , 0
  4604.5      .1       0  4988.9     .05       0    5026      .1       0
  5093.4     .03       0  5099.4      .1       0
Bank Sta=5093.4,5099.4
XS Rating Curve= 0 ,0
Exp/Cntr=0.3,0.1

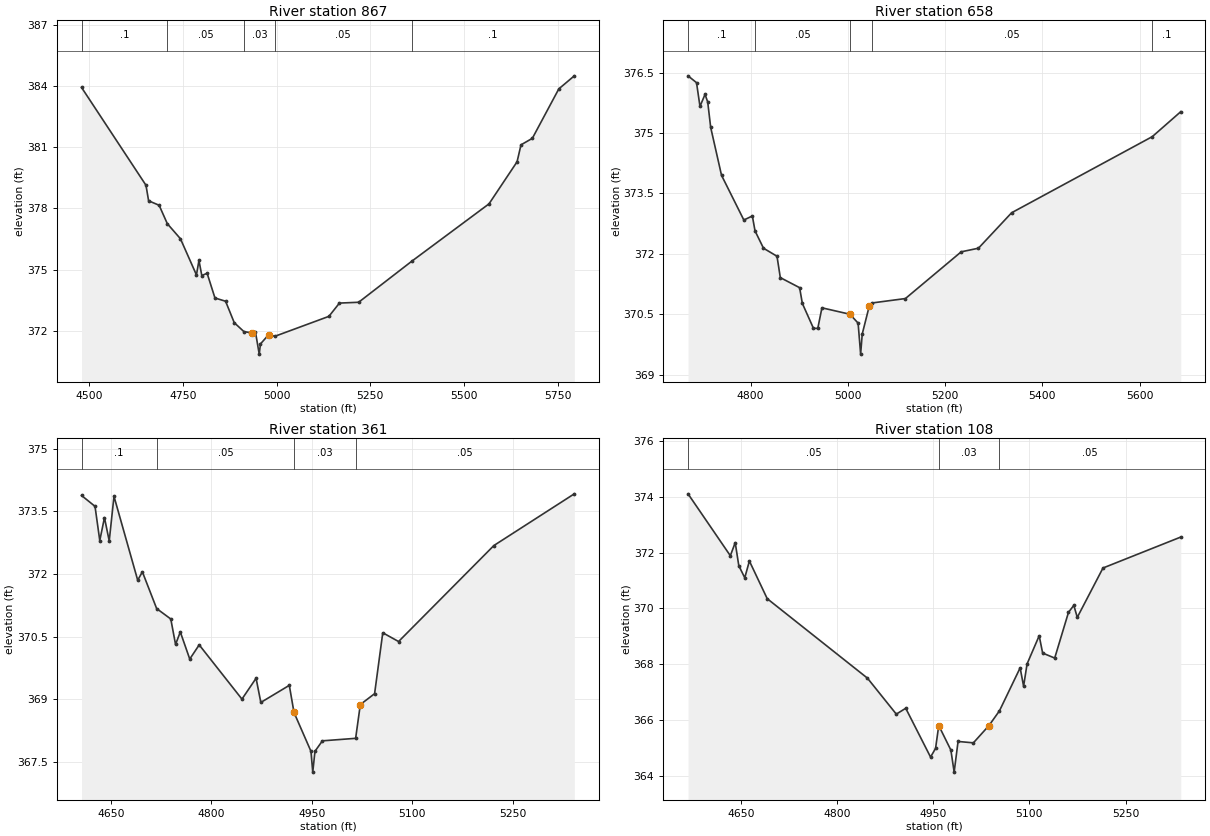
Type RM Length L Ch R = 1 ,867     ,209,209,209
BEGIN DESCRIPTION:
Mapping XS 40c23d96
END DESCRIPTION:
XS GIS Cut Line= 4
       2300172.3      13396638.7      2299875.43     13396899.11
      2299818.14     13397154.32      2299901.48     13397807.97
#Sta/Elev= 30
  4479.2  383.92  4651.2  379.13  4658.2  378.37  4686.3  378.15  4708.1  377.25
  4743.2  376.51  4785.9  374.74  4792.6  375.45  4800.2  374.71  4814.4  374.82
  4835.3  373.61  4863.7  373.45  4886.8   372.4  4912.8  371.96  4935.3   371.9
  4943.5  371.94  4953.5  370.86  4956.8  371.36  4978.6  371.81  4994.8  371.73
  5139.5  372.71  5167.6  373.36  5218.9   373.4    5360   375.4  5566.9  378.22
  5641.8  380.28  5652.3  381.11  5682.6  381.43  5753.2  383.85  5794.6  384.49
#Mann= 5 ,-1 , 0
  4479.2      .1       0  4708.1     .05       0  4912.8     .03       0
  4994.8     .05       0    5360      .1       0
Bank Sta=4935.3,4978.6
XS Rating Curve= 0 ,0
Exp/Cntr=0.3,0.1

Type RM Length L Ch R = 1 ,658     ,297,297,297
BEGIN DESCRIPTION:
Mapping XS 2c7ab96e
END DESCRIPTION:
XS GIS Cut Line= 3
      2299789.41     13396674.51        2299529.     13397238.73
      2299561.55     13397629.36
#Sta/Elev= 30
  4671.4  376.42  4688.9  376.25    4696  375.66  4706.4  375.96  4711.9  375.77
    4718  375.14  4740.3  373.95  4786.2  372.84  4803.7  372.94  4809.2  372.57
  4826.6  372.14  4854.4  371.94  4861.2  371.41  4900.9  371.16  4906.5  370.77
  4929.4  370.15  4938.3  370.15  4946.8  370.66  5004.4   370.5  5021.2  370.28
  5026.4  369.51  5029.7  370.01  5044.1   370.7  5049.6  370.78  5118.5  370.89
  5233.2  372.05  5268.7  372.14  5336.9  373.02  5626.2  374.91  5684.8  375.53
#Mann= 5 ,-1 , 0
  4671.4      .1       0  4809.2     .05       0  5004.4     .03       0
  5049.6     .05       0  5626.2      .1       0
Bank Sta=5004.4,5044.1
XS Rating Curve= 0 ,0
Exp/Cntr=0.3,0.1

Type RM Length L Ch R = 1 ,361     ,253,253,253
BEGIN DESCRIPTION:
Mapping XS f7cc41a6
END DESCRIPTION:
XS GIS Cut Line= 3
      2299659.88     13396610.59      2299335.91     13396929.12
      2299164.61     13397152.08
#Sta/Elev= 30
  4606.4  373.88  4626.5  373.62  4633.6   372.8  4640.6  373.35  4647.7  372.79
  4654.8  373.86  4690.2  371.85  4697.2  372.05  4718.5  371.17  4739.6  370.92
  4746.7  370.31  4753.8  370.61  4767.9  369.96    4782   370.3  4845.8     369
  4866.9   369.5    4874  368.92  4916.5  369.33  4923.5  368.68  4948.8  367.75
  4951.5  367.25  4954.8  367.75  4965.9     368  5015.5  368.06  5022.5  368.87
  5043.8  369.13    5056  370.59  5079.6  370.38  5221.8  372.68  5341.9  373.92
#Mann= 4 ,-1 , 0
  4606.4      .1       0  4718.5     .05       0  4923.5     .03       0
  5015.5     .05       0
Bank Sta=4923.5,5022.5
XS Rating Curve= 0 ,0
Exp/Cntr=0.3,0.1

Type RM Length L Ch R = 1 ,108     ,0,0,0
BEGIN DESCRIPTION:
UNT057 IN SUCR 1.0
END DESCRIPTION:
XS GIS Cut Line= 3
      2299586.37     13396477.22      2299243.35     13396654.17
      2299102.26     13397009.62
#Sta/Elev= 30
  4567.8  374.11  4633.8  371.89  4641.4  372.36    4647  371.53  4656.3   371.1
  4663.5   371.7  4691.3  370.35  4847.6   367.5  4892.6  366.21  4907.3  366.42
    4946  364.67  4953.8  364.98  4958.8   365.8  4977.7  364.92  4982.8  364.13
  4988.9  365.23  5012.8  365.18  5037.1   365.8  5053.5  366.33  5085.7  367.87
  5091.1  367.21  5096.5  368.01  5115.4  369.02  5120.8   368.4  5139.6  368.22
  5161.1  369.86  5169.4  370.11  5174.8  369.68  5214.9  371.45  5336.2  372.56
#Mann= 3 ,-1 , 0
  4567.8     .05       0  4958.8     .03       0  5053.5     .05       0
Bank Sta=4958.8,5037.1
XS Rating Curve= 0 ,0
Exp/Cntr=0.3,0.1

Chan Stop Cuts=-1
Use User Specified Reach Order=0
Composite Channel Slope=5