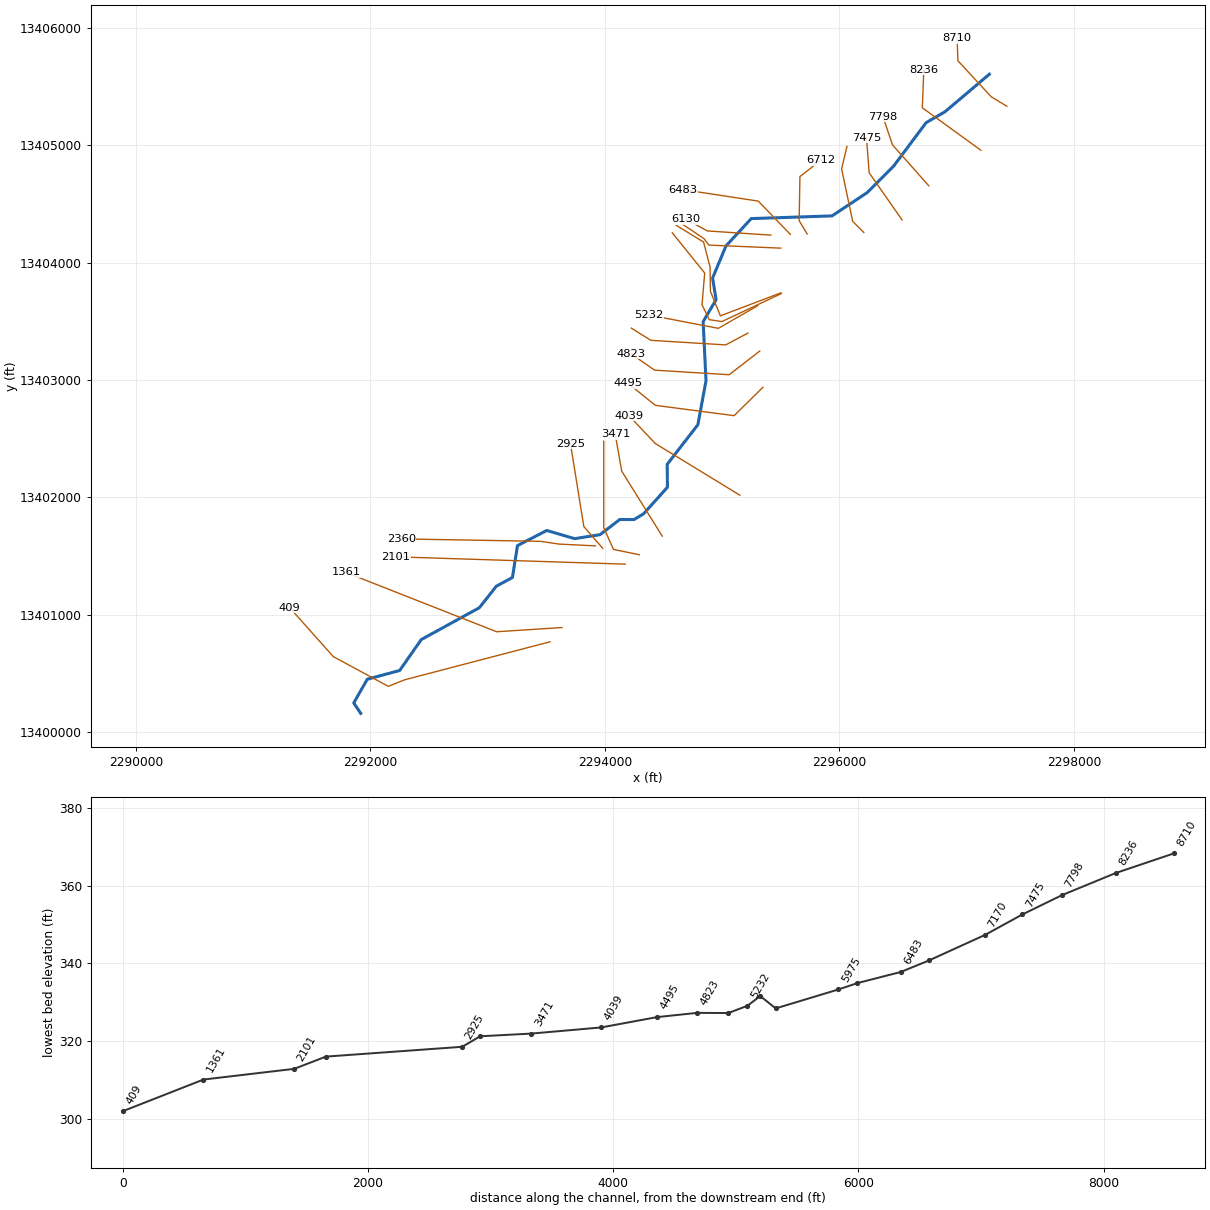
--- UNT059 IN SUCR.prj (project) ---

Proj Title=UNT059 IN SUCR Base Level Engineering
Current Plan=p01
Default Exp/Contr=0.3,0.1
English Units
Geom File=g01
Flow File=f01
Plan File=p01
Y Axis Title=Elevation
X Axis Title(PF)=Main Channel Distance
X Axis Title(XS)=Station
BEGIN DESCRIPTION:
UNT059 IN SUCR
END DESCRIPTION:
DSS Export Rating Curves= 0
DSS Export Rating Curve Sorted= 0
DSS Export Volume Flow Curves= 0
DXF OffsetX= 0
DXF OffsetY= 0
DXF ScaleX= 1
DXF ScaleY= 10

--- UNT059 IN SUCR.p01 (plan) ---

Plan Title=Multiple Run
Short Identifier=Multiple
Geom File=g01
Flow File=f01
Subcritical Flow
K Sum by GR= 0
Std Step Tol= 0.01
Critical Tol= 0.01
Num of Std Step Trials= 20
Max Error Tol= 0.3
Flow Tol Ratio= 0.001
Split Flow NTrial= 30
Split Flow Tol= 0.02
Split Flow Ratio= 0.02
Log Output Level= 0
Friction Slope Method= 1
Unsteady Friction Slope Method= 2
Unsteady Bridges Friction Slope Method= 1
Parabolic Critical Depth
Global Vel Dist=  1 , 1 , 1
Global Log Level= 0
CheckData=True
Encroach Param= -1, 0, 0, 0
BEGIN DESCRIPTION:
Multiple Run
END DESCRIPTION:

--- UNT059 IN SUCR.f01 (steady flow) ---

Flow Title=Multiple
Program Version=4.10
Number of Profiles= 7
Profile Names=10-year,25-year,50-year,1pct_min,100-year,1pct_plu,500-year
River Rch & RM=UNT059 IN SUCR,Reach-1         ,8710
     307     419     510     455     615     831     896
River Rch & RM=UNT059 IN SUCR,Reach-1         ,6483
     630     898    1124    1029    1391    1882    2139
River Rch & RM=UNT059 IN SUCR,Reach-1         ,6130
     630     898    1124    1029    1391    1882    2139
River Rch & RM=UNT059 IN SUCR,Reach-1         ,2925
     644     918    1151    1054    1426    1928    2195
River Rch & RM=UNT059 IN SUCR,Reach-1         ,2360
     721    1035    1303    1198    1620    2191    2516
River Rch & RM=UNT059 IN SUCR,Reach-1         ,2101
     760    1094    1379    1270    1717    2323    2674
Boundary for River Rch & Prof#=UNT059 IN SUCR,Reach-1         , 1
Up Type= 0
Dn Type= 3
Dn Slope=0.012
Boundary for River Rch & Prof#=UNT059 IN SUCR,Reach-1         , 2
Up Type= 0
Dn Type= 3
Dn Slope=0.012
Boundary for River Rch & Prof#=UNT059 IN SUCR,Reach-1         , 3
Up Type= 0
Dn Type= 3
Dn Slope=0.012
Boundary for River Rch & Prof#=UNT059 IN SUCR,Reach-1         , 4
Up Type= 0
Dn Type= 3
Dn Slope=0.012
Boundary for River Rch & Prof#=UNT059 IN SUCR,Reach-1         , 5
Up Type= 0
Dn Type= 3
Dn Slope=0.012
Boundary for River Rch & Prof#=UNT059 IN SUCR,Reach-1         , 6
Up Type= 0
Dn Type= 3
Dn Slope=0.012
Boundary for River Rch & Prof#=UNT059 IN SUCR,Reach-1         , 7
Up Type= 0
Dn Type= 3
Dn Slope=0.012
DSS Import GetInterval= 0
DSS Import GetPeak= 0
DSS Import FillOption= 0

--- UNT059 IN SUCR.g01 (geometry) ---

Geom Title=Existing Conditions
Program Version=4.10

River Reach=UNT059 IN SUCR  ,Reach-1
Reach XY= 30
      2297278.15     13405606.94      2296898.98     13405286.11
      2296739.26     13405194.44      2296462.18     13404823.61
      2296235.09     13404596.52      2295936.77     13404399.01
      2295248.02     13404376.16      2295032.42     13404142.86
      2294918.41     13403869.17      2294948.02     13403684.44
      2294837.72     13403496.85      2294862.19     13402993.58
      2294792.75     13402618.15      2294531.35      13402280.8
       2294533.3     13402085.22      2294330.36      13401859.1
      2294248.96     13401809.92      2294126.44     13401809.95
      2293958.68     13401680.76      2293742.02     13401646.86
      2293504.61     13401716.57      2293254.45      13401587.4
      2293211.41     13401315.32      2293075.11     13401241.88
      2292928.83     13401057.45      2292434.14     13400786.34
      2292249.92     13400522.65      2291973.81     13400448.01
      2291858.33     13400245.89      2291917.72     13400156.86

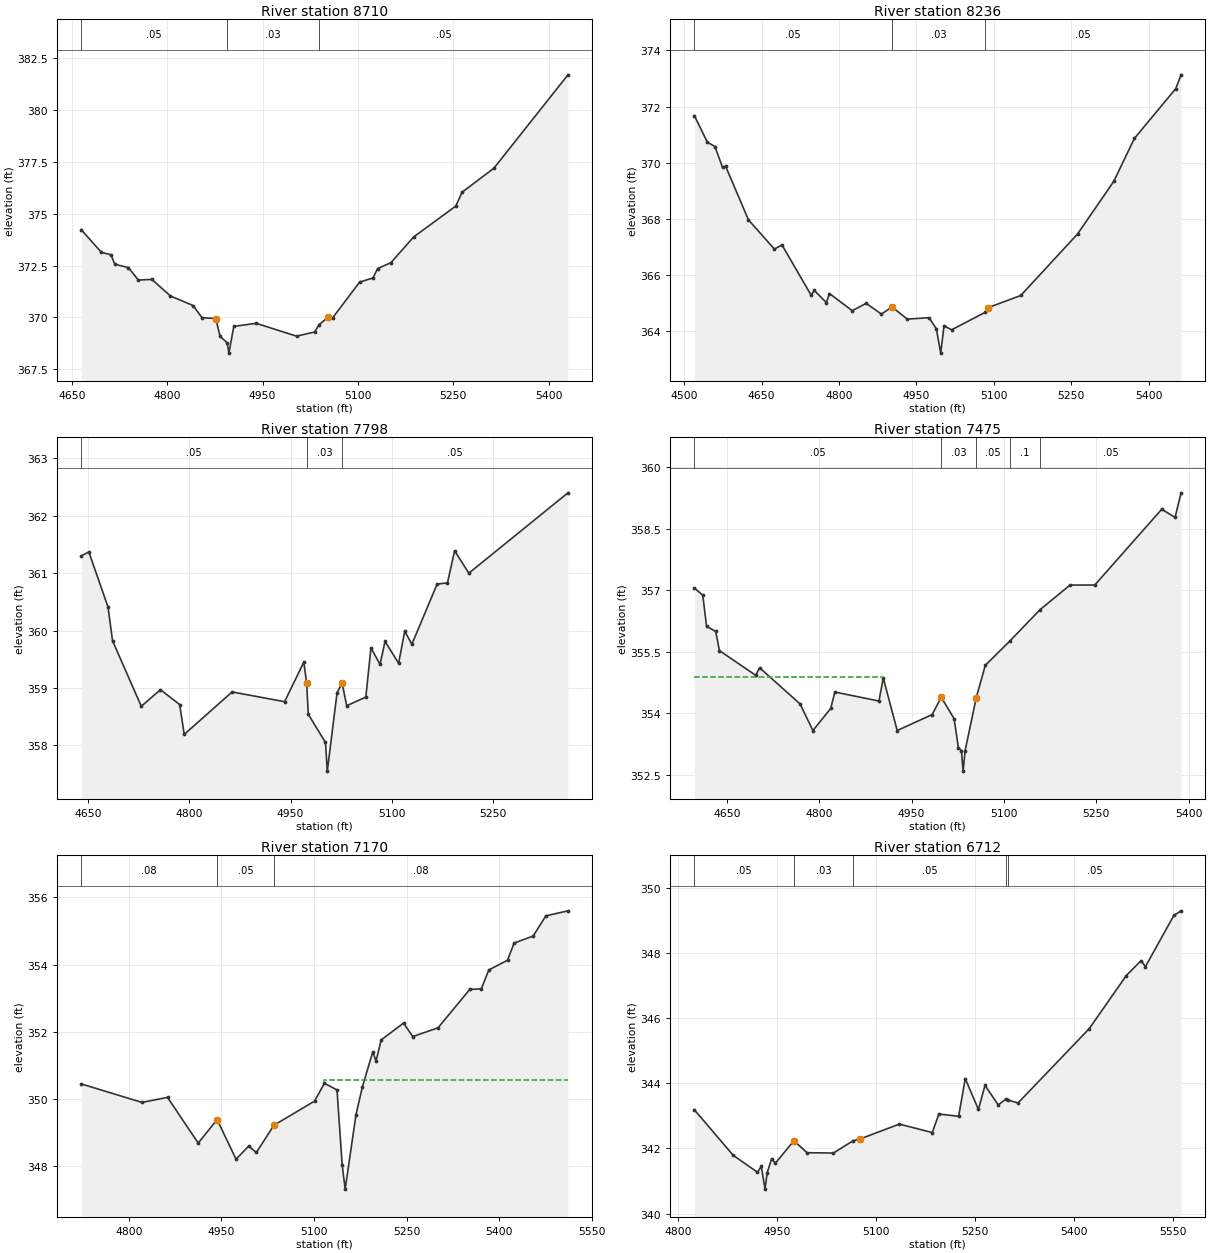
Type RM Length L Ch R = 1 ,8710    ,474,474,474
BEGIN DESCRIPTION:
UNT059 IN SUCR 11.0
END DESCRIPTION:
XS GIS Cut Line= 4
      2297427.53      13405334.1      2297293.82     13405415.63
      2297010.07      13405722.2       2297003.6     13405913.26
#Sta/Elev= 30
  4664.9  374.23  4696.5  373.14  4711.5  373.02  4717.8  372.56  4739.1   372.4
  4754.6   371.8  4775.9  371.83  4805.2  371.03  4840.7  370.57  4854.9  369.98
  4876.4  369.94  4883.3  369.08  4894.4  368.77  4897.2  368.27  4904.8  369.56
  4939.9  369.71  5003.5  369.09  5031.8  369.29  5039.2  369.65  5053.3  370.01
  5060.2  369.97  5102.7   371.7  5123.7   371.9    5131  372.35    5152  372.64
  5187.7  373.88  5253.9  375.37  5263.9  376.04  5313.9   377.2  5430.4  381.71
#Mann= 3 ,-1 , 0
  4664.9     .05       0  4894.4     .03       0  5039.2     .05       0
Bank Sta=4876.4,5053.3
XS Rating Curve= 0 ,0
Exp/Cntr=0.3,0.1

Type RM Length L Ch R = 1 ,8236    ,438,438,438
BEGIN DESCRIPTION:
UNT059 IN SUCR 10.0
END DESCRIPTION:
XS GIS Cut Line= 3
      2297205.77     13404959.02      2296706.76     13405321.05
      2296719.81     13405647.19
#Sta/Elev= 30
  4519.8  371.68    4545  370.73  4559.7  370.58  4574.3  369.84  4580.5  369.87
  4624.6  367.97  4674.9  366.93  4689.5  367.08    4746  365.29  4752.2  365.46
  4775.4  365.03  4781.5  365.35  4825.6  364.74  4852.7     365    4882  364.62
  4902.9  364.87  4932.3  364.44  4974.5  364.49  4988.7  364.09    4997  363.23
  5003.4   364.2  5018.1  364.06  5083.1  364.68  5089.2  364.85  5152.1  365.28
  5262.2  367.47  5332.3  369.34  5372.3  370.87  5452.4  372.64  5462.7  373.13
#Mann= 3 ,-1 , 0
  4519.8     .05       0  4902.9     .03       0  5083.1     .05       0
Bank Sta=4902.9,5089.2
XS Rating Curve= 0 ,0
Exp/Cntr=0.3,0.1

Type RM Length L Ch R = 1 ,7798    ,323,323,323
BEGIN DESCRIPTION:
Mapping XS 305d409e
END DESCRIPTION:
XS GIS Cut Line= 3
       2296762.2     13404655.73      2296452.37     13405004.69
      2296370.84     13405246.04
#Sta/Elev= 30
  4639.7   361.3  4650.9  361.37  4679.4  360.41  4686.1  359.82  4728.7  358.68
  4757.1  358.97  4785.6  358.71  4792.3  358.19  4863.3  358.93  4941.1  358.76
  4969.6  359.45 4973.82  359.08  4976.2  358.54  5001.7  358.05  5004.4  357.55
  5018.9  358.92  5026.4  359.08  5033.1  358.69  5061.5  358.84  5069.1   359.7
  5082.5  359.41    5090  359.81  5110.1  359.43  5119.2  359.99  5129.7  359.76
  5167.2  360.81  5182.5  360.83  5193.1  361.39  5214.2     361  5361.1   362.4
#Mann= 3 , 0 , 0
  4639.7     .05       0 4973.82     .03       0  5026.4     .05       0
#XS Ineff= 2 , 0
         4969.63  359.43
Permanent Ineff=
       T       T
Bank Sta=4973.82,5026.4
XS Rating Curve= 0 ,0
Exp/Cntr=0.3,0.1

Type RM Length L Ch R = 1 ,7475    ,305,305,305
BEGIN DESCRIPTION:
UNT059 IN SUCR 9.0
END DESCRIPTION:
XS GIS Cut Line= 3
      2296533.93     13404365.42      2296253.43     13404766.61
       2296230.6     13405066.62
#Sta/Elev= 30
  4597.2  357.06  4610.9  356.88    4617  356.12  4631.8     356  4637.9  355.53
  4696.6  354.93  4703.3  355.11  4768.8  354.23  4789.7  353.58  4818.6  354.12
  4825.4  354.52  4896.9   354.3    4904  354.86  4926.6  353.58  4983.3  353.97
  4998.1  354.39    5019  353.87    5026  353.16  5030.9  353.09  5033.6  352.59
  5036.9  353.09  5054.8  354.37  5069.6  355.17  5109.9  355.77  5158.6  356.53
  5207.3  357.13  5247.4  357.13  5356.2  358.98  5377.8  358.78  5387.6  359.38
#Mann= 5 ,-1 , 0
  4597.2     .05       0  4998.1     .03       0  5054.8     .05       0
  5109.9      .1       0  5158.6     .05       0
#XS Ineff= 2 , 0
         4903.93  354.88
Permanent Ineff=
       T       T
Bank Sta=4998.1,5054.8
XS Rating Curve= 0 ,0
Exp/Cntr=0.3,0.1

Type RM Length L Ch R = 1 ,7170    ,458,458,458
BEGIN DESCRIPTION:
UNT059 IN SUCR 8.0
END DESCRIPTION:
XS GIS Cut Line= 4
      2296207.74     13404257.86      2296113.19     13404352.41
       2296018.6     13404799.22      2296064.27     13404991.65
#Sta/Elev= 30
  4723.1  350.45  4821.4   349.9  4862.8  350.05  4912.5  348.69  4943.1  349.39
  4973.8  348.21  4994.2   348.6  5006.7  348.41  5035.1  349.22    5101  349.94
  5116.9  350.47  5137.3  350.27  5145.6  348.05  5150.5  347.32    5168  349.53
  5178.2  350.35  5195.3  351.41  5200.4  351.13  5208.9  351.76    5245  352.26
    5260  351.86  5300.9  352.12  5352.2  353.26  5371.1  353.28    5383  353.84
  5413.4  354.13  5424.1  354.64    5455  354.85  5475.5  355.45  5511.3   355.6
#Mann= 3 , 0 , 0
  4723.1     .08       0  4943.1     .05       0  5035.1     .08       0
#XS Ineff= 2 , 0
                         5117.02          350.56
Permanent Ineff=
       T       T
Bank Sta=4943.1,5035.1
XS Rating Curve= 0 ,0
Exp/Cntr=0.3,0.1

Type RM Length L Ch R = 1 ,6712    ,229,229,229
BEGIN DESCRIPTION:
Mapping XS 990d0cda
END DESCRIPTION:
XS GIS Cut Line= 4
      2295725.06     13404244.82      2295656.59     13404358.93
      2295663.11       13404734.       2295844.2     13404876.28
#Sta/Elev= 30
  4824.4  343.19  4883.3  341.79  4920.1  341.27    4926  341.45  4931.6  340.75
  4934.8  341.25  4941.6  341.68  4947.4  341.55  4975.4  342.24  4995.4  341.87
  5035.4  341.86  5065.4  342.24  5075.4  342.29  5135.4  342.75  5185.4  342.49
  5195.4  343.06  5225.4  342.99  5235.4  344.15  5255.4   343.2  5265.4  343.94
  5285.5  343.34  5297.1  343.52  5300.3  343.49  5315.5   343.4  5423.7  345.69
  5479.8  347.32  5502.3  347.78  5508.7  347.59    5552  349.17  5562.9  349.31
#Mann= 5 ,-1 , 0
  4824.4     .05       0  4975.4     .03       0  5065.4     .05       0
  5297.1      .1       0  5300.3     .05       0
#XS Ineff= 1 ,-1
 4843.98 4973.82  342.09
Permanent Ineff=
       T
Bank Sta=4975.4,5075.4
XS Rating Curve= 0 ,0
Exp/Cntr=0.3,0.1

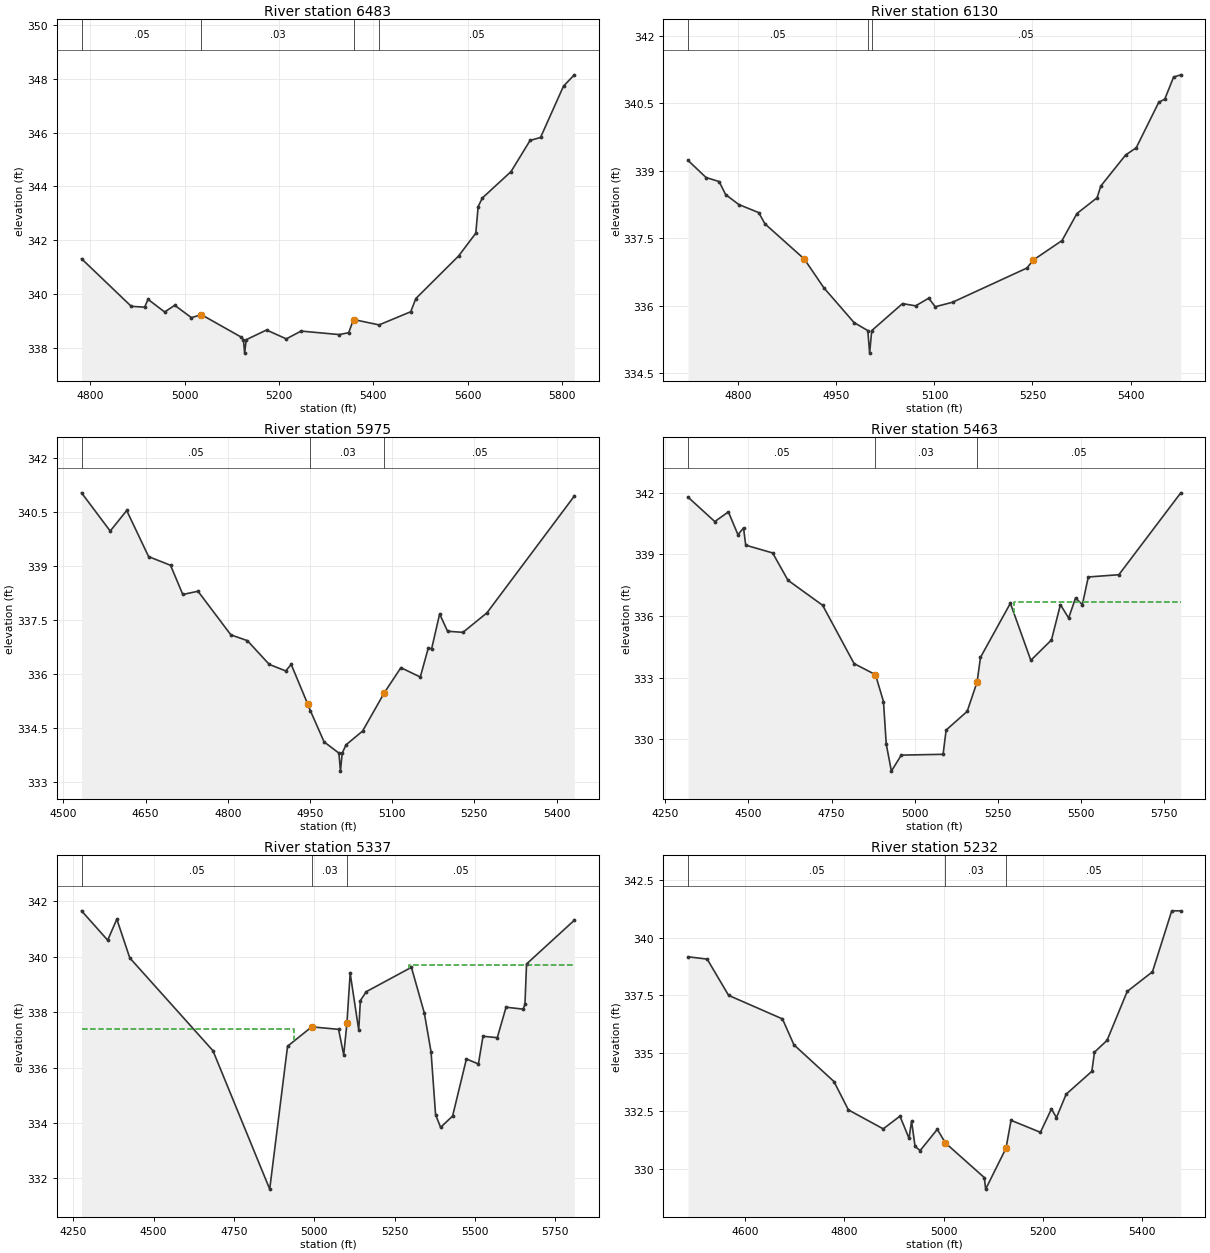
Type RM Length L Ch R = 1 ,6483    ,353,353,353
BEGIN DESCRIPTION:
Mapping XS 5fbf7dc4
END DESCRIPTION:
XS GIS Cut Line= 3
       2295581.6      13404241.5      2295307.62     13404525.26
      2294665.08     13404623.11
#Sta/Elev= 30
  4781.5  341.31  4886.9  339.54  4915.2  339.51  4922.4   339.8  4957.7  339.33
    4979  339.58  5014.3  339.12  5035.6  339.23  5120.5  338.39  5124.5   338.3
  5127.2   337.8  5130.5   338.3  5173.6  338.66  5215.5  338.33  5246.7  338.62
  5327.6  338.49  5347.7  338.56  5357.9  339.05  5412.1  338.85  5479.3  339.34
    5490  339.83  5580.5  341.41  5617.1  342.26  5622.1  343.25    5631  343.57
  5691.7  344.55  5732.2  345.71  5754.3  345.82    5803  347.73  5825.9  348.15
#Mann= 4 ,-1 , 0
  4781.5     .05       0  5035.6     .03       0  5357.9     .05       0
  5412.1     .05       0
Bank Sta=5035.6,5357.9
XS Rating Curve= 0 ,0
Exp/Cntr=0.3,0.1

Type RM Length L Ch R = 1 ,6130    ,155,155,155
BEGIN DESCRIPTION:
UNT059 IN SUCR 7.0
END DESCRIPTION:
XS GIS Cut Line= 3
      2295415.21       13404235.      2294873.85     13404270.88
       2294688.1      13404371.9
#Sta/Elev= 30
  4722.9  339.23  4750.5  338.85  4770.5  338.76  4780.5  338.47  4800.6  338.25
  4831.1  338.07  4840.7  337.82  4900.8  337.04  4930.8   336.4  4976.9  335.63
    4998  335.45  5000.8  334.95    5004  335.45  5051.1  336.05  5071.2     336
  5091.2  336.17  5101.2  335.98  5127.7  336.08  5241.5  336.84  5251.5  337.02
  5295.2  337.45    5318  338.05  5348.8   338.4  5354.5  338.66  5392.5  339.35
  5408.7  339.51  5443.2  340.52  5452.4  340.59  5465.9  341.08  5476.9  341.13
#Mann= 3 ,-1 , 0
  4722.9     .05       0    4998     .03       0    5004     .05       0
Bank Sta=4900.8,5251.5
XS Rating Curve= 0 ,0
Exp/Cntr=0.3,0.1

Type RM Length L Ch R = 1 ,5975    ,512,512,512
BEGIN DESCRIPTION:
UNT059 IN SUCR 6.0
END DESCRIPTION:
XS GIS Cut Line= 4
      2295500.02     13404124.11       2294886.9      13404150.2
       2294844.5     13404205.65      2294665.25     13404325.86
#Sta/Elev= 30
  4533.1  341.03  4585.4  339.97  4615.5  340.54  4655.5  339.26  4695.5  339.02
  4717.9  338.21  4745.6   338.3  4805.6  337.09  4835.7  336.93  4875.7  336.27
  4905.7  336.09  4915.7  336.27  4945.6  335.18  4950.6  334.99  4975.8  334.12
  5002.8  333.81  5005.6  333.31  5008.8  333.81  5015.8  334.04  5045.9  334.42
  5085.9  335.49  5115.9  336.18  5151.3  335.92  5165.8  336.72  5172.1  336.71
  5186.6  337.67  5201.1  337.19  5229.2  337.16  5272.9   337.7  5432.4  340.94
#Mann= 3 ,-1 , 0
  4533.1     .05       0  4950.6     .03       0  5085.9     .05       0
Bank Sta=4945.6,5085.9
XS Rating Curve= 0 ,0
Exp/Cntr=0.3,0.1

Type RM Length L Ch R = 1 ,5463    ,126,126,126
BEGIN DESCRIPTION:
Mapping XS 163c0a03
END DESCRIPTION:
XS GIS Cut Line= 6
      2295500.31     13403742.74      2294984.74     13403546.84
      2294899.94     13403755.57      2294896.68      13403964.3
      2294841.24     13404176.29      2294605.84     13404320.18
#Sta/Elev= 30
  4318.1  341.79  4398.6   340.6  4439.6  341.07  4468.3  339.96  4485.1  340.29
  4491.6  339.45  4572.7  339.07  4618.7  337.74    4723  336.52  4817.6  333.68
  4881.9  333.14    4906  331.83  4914.3  329.76  4929.8  328.44  4959.5  329.22
  5085.3  329.26  5094.4  330.44  5157.7  331.35  5187.7  332.79  5197.7  333.98
  5287.7  336.62  5349.2  333.84  5411.2  334.83  5438.2  336.55  5462.9   335.9
  5483.8  336.88  5504.2  336.55    5522   337.9    5614  338.01  5800.2     342
#Mann= 3 , 0 , 0
  4318.1     .05       0  4881.9     .03       0  5187.7     .05       0
#XS Ineff= 2 , 0
                         5298.95          336.66
Permanent Ineff=
       T       T
Bank Sta=4881.9,5187.7
XS Rating Curve= 0 ,0
Exp/Cntr=0.3,0.1

Type RM Length L Ch R = 1 ,5337    ,105,105,105
BEGIN DESCRIPTION:
UNT059 IN SUCR 5.0
END DESCRIPTION:
XS GIS Cut Line= 6
       2295504.3     13403736.71      2294997.78     13403497.92
      2294890.16     13403514.23      2294828.19     13403641.42
      2294851.02     13403912.12      2294574.71     13404255.07
#Sta/Elev= 30
  4275.7  341.66    4357   340.6  4385.5  341.36  4425.8  339.96  4684.6  336.61
  4861.3  331.61  4916.8  336.77  4992.1  337.47  5075.6  337.38  5091.6  336.46
  5101.6   337.6  5111.7  339.41  5138.4  337.35  5143.4  338.42  5161.8  338.74
  5302.3  339.62  5342.5  337.97  5363.4  336.57  5377.5   334.3  5393.2  333.84
  5430.5  334.25  5473.5  336.31  5510.8  336.13  5525.1  337.13  5569.6  337.08
  5596.9  338.18  5649.9  338.11  5655.7  338.28  5660.6  339.74  5809.3  341.32
#Mann= 3 , 0 , 0
  4275.7     .05       0  4992.1     .03       0  5101.6     .05       0
#XS Ineff= 2 , 0
          4937.7  337.41 5294.24          339.72
Permanent Ineff=
       T       T
Bank Sta=4992.1,5101.6
XS Rating Curve= 0 ,0
Exp/Cntr=0.3,0.1

Type RM Length L Ch R = 1 ,5232    ,156,156,156
BEGIN DESCRIPTION:
Mapping XS 279110c7
END DESCRIPTION:
XS GIS Cut Line= 3
      2295302.91     13403632.97      2294966.98     13403440.27
      2294371.65     13403554.66
#Sta/Elev= 30
  4484.7  339.17  4523.3  339.07  4566.5   337.5  4675.1  336.48  4698.2  335.36
  4778.9  333.77  4808.1  332.54  4878.3  331.72    4912  332.27  4930.3  331.31
  4935.4  332.06  4942.5  330.96  4952.7  330.78  4987.3   331.7  5003.6  331.11
  5082.1  329.61  5084.8  329.11  5125.8  330.88    5136  332.09  5195.2  331.57
  5217.4  332.58  5227.6  332.21  5247.1  333.22  5298.9  334.21  5304.2  335.04
  5329.5  335.55  5370.2  337.67  5421.1  338.52    5460  341.16  5478.2  341.16
#Mann= 3 , 0 , 0
  4484.7     .05       0  5003.6     .03       0  5125.8     .05       0
Bank Sta=5003.6,5125.8
XS Rating Curve= 0 ,0
Exp/Cntr=0.3,0.1

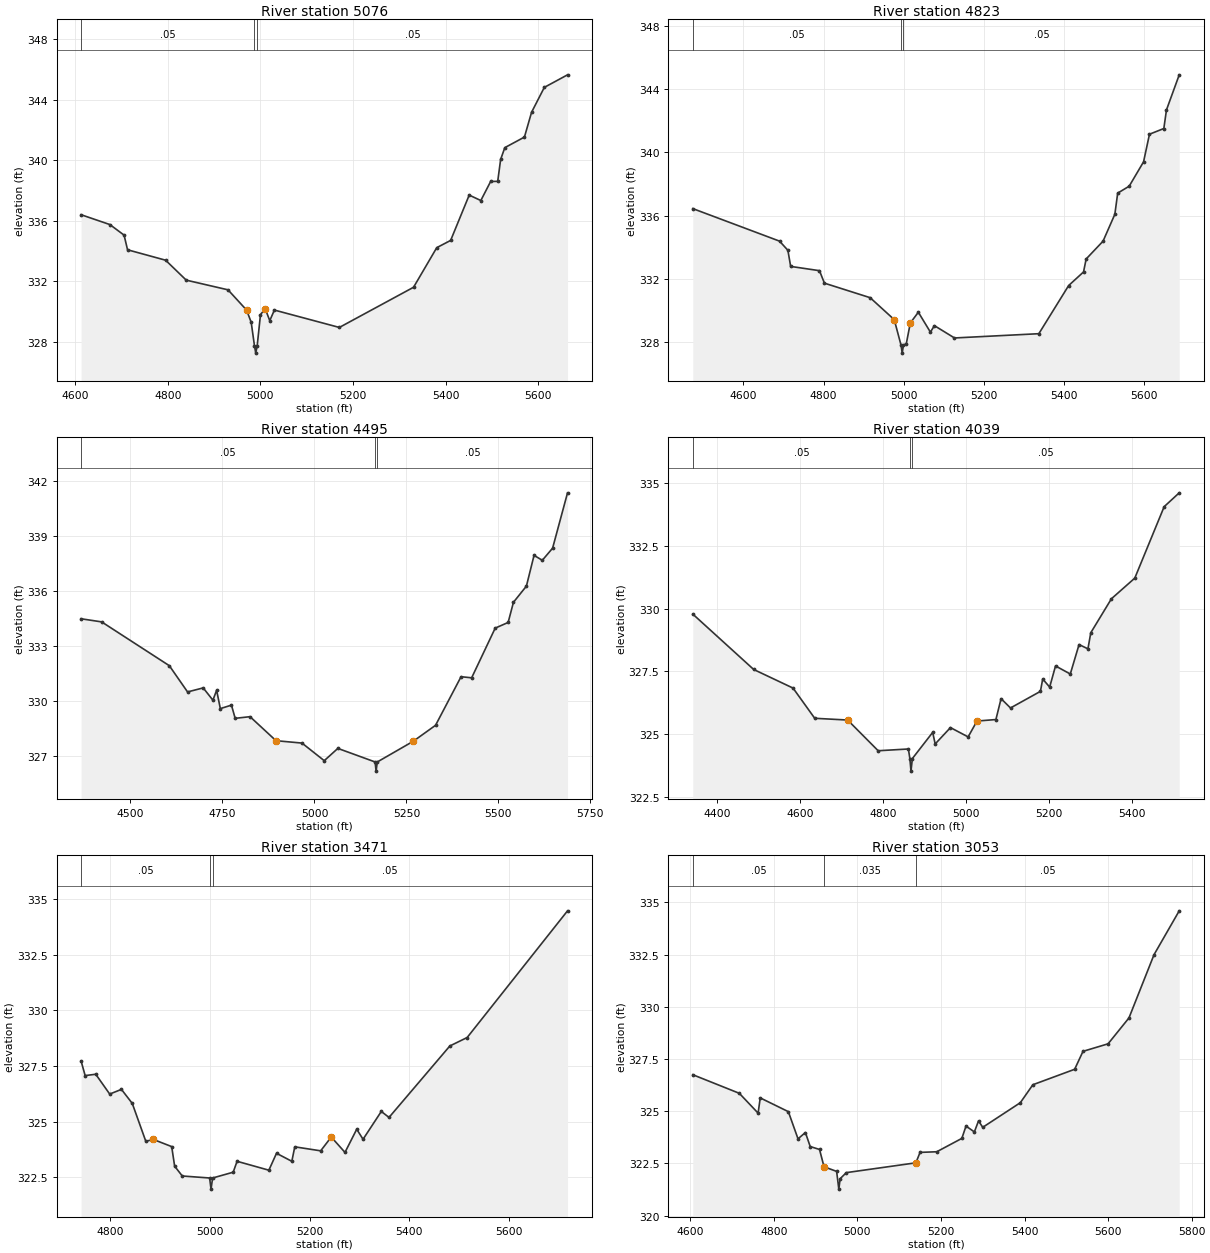
Type RM Length L Ch R = 1 ,5076    ,253,253,253
BEGIN DESCRIPTION:
UNT059 IN SUCR 4.0
END DESCRIPTION:
XS GIS Cut Line= 4
      2295219.53     13403400.06       2295030.4     13403298.98
      2294391.16     13403338.11      2294225.29     13403442.19
#Sta/Elev= 30
  4612.7   336.4  4674.8  335.75  4705.5  335.05    4713  334.08  4795.2  333.39
  4839.8  332.07    4930  331.43  4970.1  330.09  4980.1  329.28  4987.1  327.74
  4989.9  327.24  4993.1  327.74  5000.1  329.78  5010.2  330.19  5020.2  329.39
  5030.2  330.09  5170.5  328.94  5330.8   331.6  5380.9  334.22  5410.9   334.7
    5451   337.7  5476.1  337.34  5497.3   338.6  5512.6  338.61  5518.9  340.06
  5527.9  340.84  5570.3  341.54  5585.7  343.18  5613.3  344.83  5663.4  345.66
#Mann= 3 ,-1 , 0
  4612.7     .05       0  4987.1     .03       0  4993.1     .05       0
Bank Sta=4970.1,5010.2
XS Rating Curve= 0 ,0
Exp/Cntr=0.3,0.1

Type RM Length L Ch R = 1 ,4823    ,328,328,328
BEGIN DESCRIPTION:
UNT059 IN SUCR 3.0
END DESCRIPTION:
XS GIS Cut Line= 4
       2295320.7     13403246.82      2295059.75     13403044.59
      2294423.78     13403083.72      2294221.57     13403223.96
#Sta/Elev= 30
  4473.8  336.44  4690.2  334.38    4711   333.8  4717.9  332.78  4789.8  332.51
  4802.1  331.72  4916.2   330.8  4976.3  329.41  4993.3  327.79  4996.1  327.29
  4999.3  327.79  5006.4  327.89  5016.4   329.2  5036.4  329.88  5066.5  328.62
  5076.5  329.03  5126.6  328.25    5337  328.52  5411.4  331.57  5448.5  332.43
    5455  333.25  5497.2  334.38  5526.6  336.08  5533.7  337.42  5562.4  337.86
  5598.2   339.4    5613  341.15  5648.8  341.51  5655.4  342.69  5687.2  344.91
#Mann= 3 ,-1 , 0
  4473.8     .05       0  4993.3     .03       0  4999.3     .05       0
Bank Sta=4976.3,5016.4
XS Rating Curve= 0 ,0
Exp/Cntr=0.3,0.1

Type RM Length L Ch R = 1 ,4495    ,456,456,456
BEGIN DESCRIPTION:
UNT059 IN SUCR 2.0
END DESCRIPTION:
XS GIS Cut Line= 4
      2295346.77     13402936.97      2295102.15     13402695.61
       2294430.3     13402783.67      2294196.08     13402972.35
#Sta/Elev= 30
  4365.8  334.51  4421.7  334.34  4605.6  331.95  4655.1  330.52  4697.6  330.74
    4724  330.07  4734.1  330.61  4744.2  329.61  4774.4   329.8  4784.5  329.08
  4824.9  329.17  4895.5  327.86  4966.1  327.73  5026.6  326.77  5063.6  327.44
  5164.8   326.7  5167.5   326.2  5170.8   326.7  5268.6  327.83  5329.1   328.7
  5398.4  331.35  5427.2  331.29  5491.2     334  5526.4  334.31  5540.8  335.41
    5576  336.29  5596.8  337.97  5619.2   337.7  5647.2  338.36  5687.8  341.38
#Mann= 3 ,-1 , 0
  4365.8     .05       0  5164.8     .03       0  5170.8     .05       0
Bank Sta=4895.5,5268.6
XS Rating Curve= 0 ,0
Exp/Cntr=0.3,0.1

Type RM Length L Ch R = 1 ,4039    ,568,568,568
BEGIN DESCRIPTION:
Mapping XS f974b214
END DESCRIPTION:
XS GIS Cut Line= 3
      2295151.05     13402017.25       2294430.3     13402457.53
      2294205.26     13402695.62
#Sta/Elev= 30
  4341.2  329.78  4487.9  327.58  4582.8  326.84    4635  325.64  4714.4  325.57
  4787.9  324.35  4860.7  324.42  4864.3  324.04    4867  323.54  4870.3  324.04
  4919.3  325.08  4925.3  324.62  4962.1  325.27  5004.7   324.9    5026  325.53
  5071.6  325.59  5084.1  326.42  5106.8  326.05  5178.9  326.71  5184.4   327.2
  5201.2  326.88  5215.3  327.72  5250.9   327.4    5272  328.57  5293.4   328.4
  5300.3  329.04    5350  330.39  5406.3  331.21  5477.1  334.05  5513.4   334.6
#Mann= 3 ,-1 , 0
  4341.2     .05       0  4864.3     .03       0  4870.3     .05       0
Bank Sta=4714.4,5026
XS Rating Curve= 0 ,0
Exp/Cntr=0.3,0.1

Type RM Length L Ch R = 1 ,3471    ,418,418,418
BEGIN DESCRIPTION:
Mapping XS aa51aeef
END DESCRIPTION:
XS GIS Cut Line= 3
      2294489.01     13401668.26      2294143.29     13402222.71
      2294087.85     13402539.08
#Sta/Elev= 30
  4742.3  327.72  4750.4  327.07  4771.6  327.13  4799.6  326.24  4823.1  326.45
  4844.8  325.82  4871.9  324.12  4887.2   324.2  4923.8  323.88  4929.7     323
    4945  322.56  4999.8  322.47  5002.6  321.97  5005.8  322.47    5047  322.73
  5054.8  323.22  5118.5  322.82  5133.8  323.58  5164.5  323.22  5170.4  323.87
  5222.3  323.69  5243.5  324.31    5271  323.62  5294.5  324.66  5307.2  324.21
  5343.8  325.46  5359.2  325.19  5481.1   328.4  5515.8  328.78  5716.9  334.47
#Mann= 3 ,-1 , 0
  4742.3     .05       0  4999.8     .03       0  5005.8     .05       0
Bank Sta=4887.2,5243.5
XS Rating Curve= 0 ,0
Exp/Cntr=0.3,0.1

Type RM Length L Ch R = 1 ,3053    ,147,147,147
BEGIN DESCRIPTION:
Mapping XS dca0b407
END DESCRIPTION:
XS GIS Cut Line= 4
      2294292.89     13401509.45      2294073.33     13401555.09
      2293990.01     13401740.02      2293990.01     13402477.14
#Sta/Elev= 30
  4606.1  326.75  4717.4  325.86  4762.4  324.91  4767.5  325.64  4834.8  324.98
  4857.9  323.68  4875.6  323.98  4887.1  323.31  4909.4  323.17  4920.2  322.34
  4950.3  322.12  4955.6  321.27  4958.8  321.77  4973.5  322.06    5140  322.53
    5150  323.03    5190  323.06    5250   323.7    5260  324.29    5280  324.01
    5290  324.54    5300  324.23    5390  325.41    5420  326.27    5520  327.01
    5540  327.87    5600  328.23    5650  329.47    5710   332.5  5770.3   334.6
#Mann= 3 , 0 , 0
  4606.1     .05       0  4920.2    .035       0    5140     .05       0
Bank Sta=4920.2,5140
XS Rating Curve= 0 ,0
Exp/Cntr=0.3,0.1

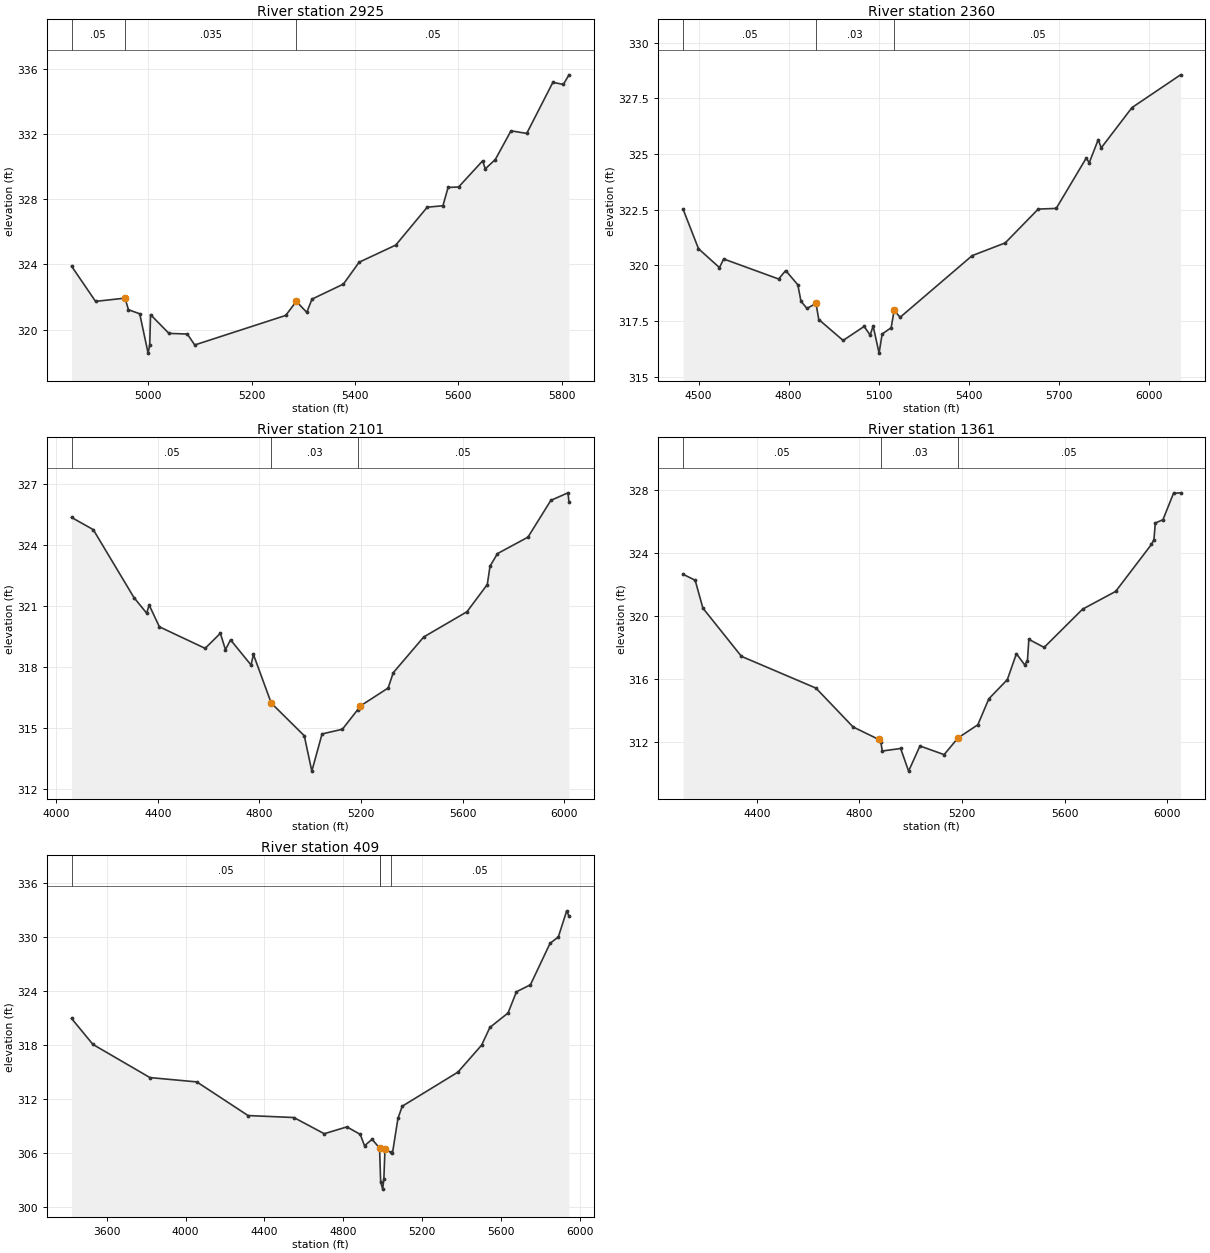
Type RM Length L Ch R = 1 ,2925    ,1111,1111,1111
BEGIN DESCRIPTION:
Mapping XS b8a73c7f
END DESCRIPTION:
XS GIS Cut Line= 3
      2293981.32     13401564.63      2293820.42     13401749.81
      2293706.26     13402457.54
#Sta/Elev= 30
  4851.7   323.9  4898.2  321.74  4955.1  321.94  4961.8  321.23  4983.6  320.98
  4999.8  318.57    5003  319.07  5004.5  320.93  5040.1  319.78  5075.7  319.74
    5090  319.07    5266  320.88  5286.5  321.74  5306.7  321.07  5316.9  321.88
  5377.6   322.8    5408  324.14  5478.9  325.19  5539.7  327.51  5570.1   327.6
  5580.1  328.72  5600.5  328.75  5646.9  330.35    5652  329.86  5671.4  330.43
  5701.8  332.19  5732.2  332.03  5782.8  335.16  5803.1  335.03  5813.9  335.62
#Mann= 3 , 0 , 0
  4851.7     .05       0  4955.1    .035       0  5286.5     .05       0
Bank Sta=4955.1,5286.5
XS Rating Curve= 0 ,0
Exp/Cntr=0.3,0.1

Type RM Length L Ch R = 1 ,2360    ,259,259,259
BEGIN DESCRIPTION:
Mapping XS c2dd2dca
END DESCRIPTION:
XS GIS Cut Line= 4
      2293918.82     13401585.32      2293608.48     13401600.51
      2293451.02      13401623.9       2292263.5     13401644.74
#Sta/Elev= 30
  4448.4  322.51  4499.6  320.74  4569.6  319.89  4583.4  320.28  4766.6  319.38
  4790.2  319.76  4830.6  319.12  4841.1  318.38    4861  318.06  4891.3  318.28
  4900.4  317.56  4981.6  316.62  5051.6  317.25  5071.6  316.86  5081.6  317.27
  5101.4  316.05  5111.6  316.91  5141.6  317.19  5151.6  317.97  5171.6  317.66
  5411.7  320.43  5521.7     321  5631.7  322.52  5691.7  322.55  5791.7  324.81
  5801.7   324.6  5831.7  325.64  5841.7  325.27  5944.3  327.08    6106  328.55
#Mann= 3 , 0 , 0
  4448.4     .05       0  4891.3     .03       0  5151.6     .05       0
Bank Sta=4891.3,5151.6
XS Rating Curve= 0 ,0
Exp/Cntr=0.3,0.1

Type RM Length L Ch R = 1 ,2101    ,740,740,740
BEGIN DESCRIPTION:
Mapping XS 757e6884
END DESCRIPTION:
XS GIS Cut Line= 2
      2294173.21     13401429.46      2292216.51     13401491.91
#Sta/Elev= 30
  4060.8  325.38  4146.3  324.78  4306.4  321.44  4356.4  320.67  4366.4  321.07
  4406.5     320  4586.6  318.94  4646.6  319.68  4666.6  318.87  4686.6  319.36
  4767.3  318.12  4776.7  318.64  4846.7  316.25  4976.8  314.64  5006.5   312.9
  5046.8  314.73  5126.8  314.96  5186.9  315.92  5196.9   316.1  5306.9  316.99
  5326.9  317.74    5447   319.5  5617.1  320.74  5697.1  322.08  5707.8  322.98
  5737.1   323.6  5857.2  324.41  5947.3  326.22  6014.6  326.59  6018.5  326.15
#Mann= 3 ,-1 , 0
  4060.8     .05       0  4846.7     .03       0  5186.9     .05       0
Bank Sta=4846.7,5196.9
XS Rating Curve= 0 ,0
Exp/Cntr=0.3,0.1

Type RM Length L Ch R = 1 ,1361    ,658,658,658
BEGIN DESCRIPTION:
Mapping XS ccee50e6
END DESCRIPTION:
XS GIS Cut Line= 3
      2293634.56      13400888.8      2293076.81     13400852.92
      2291792.24     13401358.27
#Sta/Elev= 30
  4112.4  322.67  4159.3  322.29  4189.4  320.52  4339.7  317.45  4630.3  315.43
    4775  312.96  4874.5  312.17  4883.4  311.99  4888.8  311.43  4960.5  311.59
  4991.5  310.15  5035.7  311.75  5129.9   311.2  5184.1  312.26  5261.4   313.1
  5304.3  314.75  5376.4  315.97  5411.8  317.62    5444  316.91  5454.8  317.18
  5460.3  318.53  5519.9  318.02  5669.7  320.45  5798.7  321.58  5938.3  324.57
    5948  324.87  5953.3  325.93  5983.1  326.14  6024.3  327.82  6051.7  327.85
#Mann= 3 ,-1 , 0
  4112.4     .05       0  4883.4     .03       0  5184.1     .05       0
Bank Sta=4874.5,5184.1
XS Rating Curve= 0 ,0
Exp/Cntr=0.3,0.1

Type RM Length L Ch R = 1 ,409     ,0,0,0
BEGIN DESCRIPTION:
UNT059 IN SUCR 1.0
END DESCRIPTION:
XS GIS Cut Line= 5
      2293532.56     13400767.37      2292291.65     13400442.98
      2292152.76     13400387.43      2291684.01      13400640.9
      2291312.57     13401057.47
#Sta/Elev= 30
  3421.4  320.99  3529.8   318.1  3819.2  314.41  4056.9  313.93  4316.8  310.19
  4549.1  309.97  4703.4  308.17    4818  308.93  4885.8   308.1  4907.7  306.83
  4945.8  307.55  4983.9  306.58  4989.5  302.81  4999.8  302.01  5005.7  303.15
  5011.4  306.44  5041.2   306.1  5049.5  306.03  5077.1  309.87    5099  311.23
  5381.5  315.02  5501.6  318.02  5543.6  319.99  5635.6  321.59  5678.2  323.95
  5749.3  324.73  5848.8  329.34  5890.6  330.04  5933.2  332.95  5944.6  332.37
#Mann= 4 ,-1 , 0
  3421.4     .05       0  4983.9    .035       0  4983.9     .07       0
  5041.2     .05       0
Bank Sta=4983.9,5011.4
XS Rating Curve= 0 ,0
Exp/Cntr=0.3,0.1

Chan Stop Cuts=-1
Use User Specified Reach Order=0
Composite Channel Slope=5