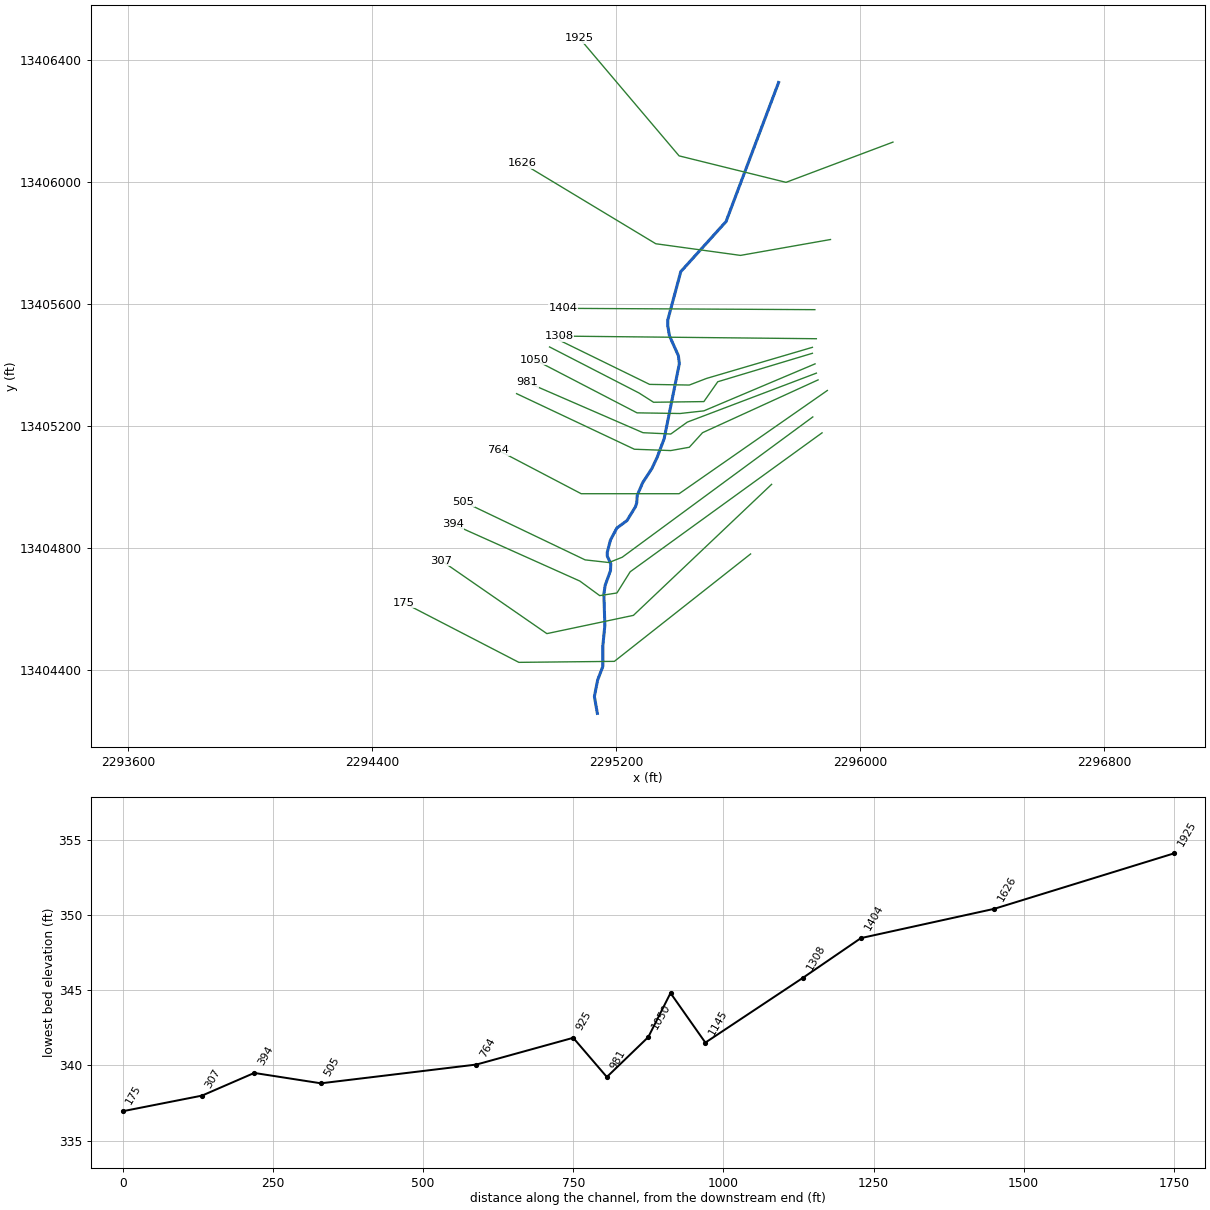
--- UNT060 IN SUCR.prj (project) ---

Proj Title=UNT060 IN SUCR Base Level Engineering
Current Plan=p01
Default Exp/Contr=0.3,0.1
English Units
Geom File=g01
Flow File=f01
Plan File=p01
BEGIN DESCRIPTION:
UNT060 IN SUCR
END DESCRIPTION:

--- UNT060 IN SUCR.p01 (plan) ---

Plan Title=Multiple Run
Short Identifier=Multiple
Geom File=g01
Flow File=f01
Subcritical Flow
K Sum by GR= 0
Std Step Tol= 0.01
Critical Tol= 0.01
Num of Std Step Trials= 20
Max Error Tol= 0.3
Flow Tol Ratio= 0.001
Split Flow NTrial= 30
Split Flow Tol= 0.02
Split Flow Ratio= 0.02
Log Output Level= 0
Friction Slope Method= 1
Unsteady Friction Slope Method= 2
Unsteady Bridges Friction Slope Method= 1
Parabolic Critical Depth
Global Vel Dist=  1 , 1 , 1
Global Log Level= 0
CheckData=True
Encroach Param= -1, 0, 0, 0
BEGIN DESCRIPTION:
Multiple Run
END DESCRIPTION:

--- UNT060 IN SUCR.f01 (steady flow) ---

Flow Title=Multiple
Number of Profiles=7
Profile Names=10-year,25-year,50-year,1pct_min,100-year,1pct_plu,500-year
River Rch & RM= UNT060 IN SUCR,Reach-1,1925
     314     430     524     468     634     857     928
Boundary for River Rch & Prof#=UNT060 IN SUCR,Reach-1,1
Up Type=0
Dn Type=3
Dn Slope=0.005
Boundary for River Rch & Prof#=UNT060 IN SUCR,Reach-1,2
Up Type=0
Dn Type=3
Dn Slope=0.005
Boundary for River Rch & Prof#=UNT060 IN SUCR,Reach-1,3
Up Type=0
Dn Type=3
Dn Slope=0.005
Boundary for River Rch & Prof#=UNT060 IN SUCR,Reach-1,4
Up Type=0
Dn Type=3
Dn Slope=0.005
Boundary for River Rch & Prof#=UNT060 IN SUCR,Reach-1,5
Up Type=0
Dn Type=3
Dn Slope=0.005
Boundary for River Rch & Prof#=UNT060 IN SUCR,Reach-1,6
Up Type=0
Dn Type=3
Dn Slope=0.005
Boundary for River Rch & Prof#=UNT060 IN SUCR,Reach-1,7
Up Type=0
Dn Type=3
Dn Slope=0.005

--- UNT060 IN SUCR.g01 (geometry) ---

Geom Title=Existing Conditions

River Reach=UNT060 IN SUCR,Reach-1
Reach XY= 30
      2295732.13     13406325.76      2295559.71     13405869.60
      2295411.38     13405705.53      2295368.72     13405547.13
      2295368.72     13405527.60      2295374.14     13405495.05
      2295403.44     13405429.94      2295406.69     13405403.90
      2295356.78     13405157.59      2295333.99     13405096.83
      2295316.63     13405059.94      2295286.25     13405013.28
      2295268.54     13404971.91      2295266.88     13404947.43
      2295262.63     13404934.33      2295234.68     13404888.92
      2295201.48     13404864.43      2295180.75     13404825.25
      2295170.22     13404785.21      2295170.39     13404772.44
      2295181.87     13404747.65      2295180.78     13404724.87
      2295163.42     13404677.12      2295159.08     13404647.83
      2295162.34     13404545.83      2295155.83     13404479.64
      2295155.83     13404411.28      2295138.67     13404366.25
      2295128.04     13404312.23      2295137.72     13404256.86

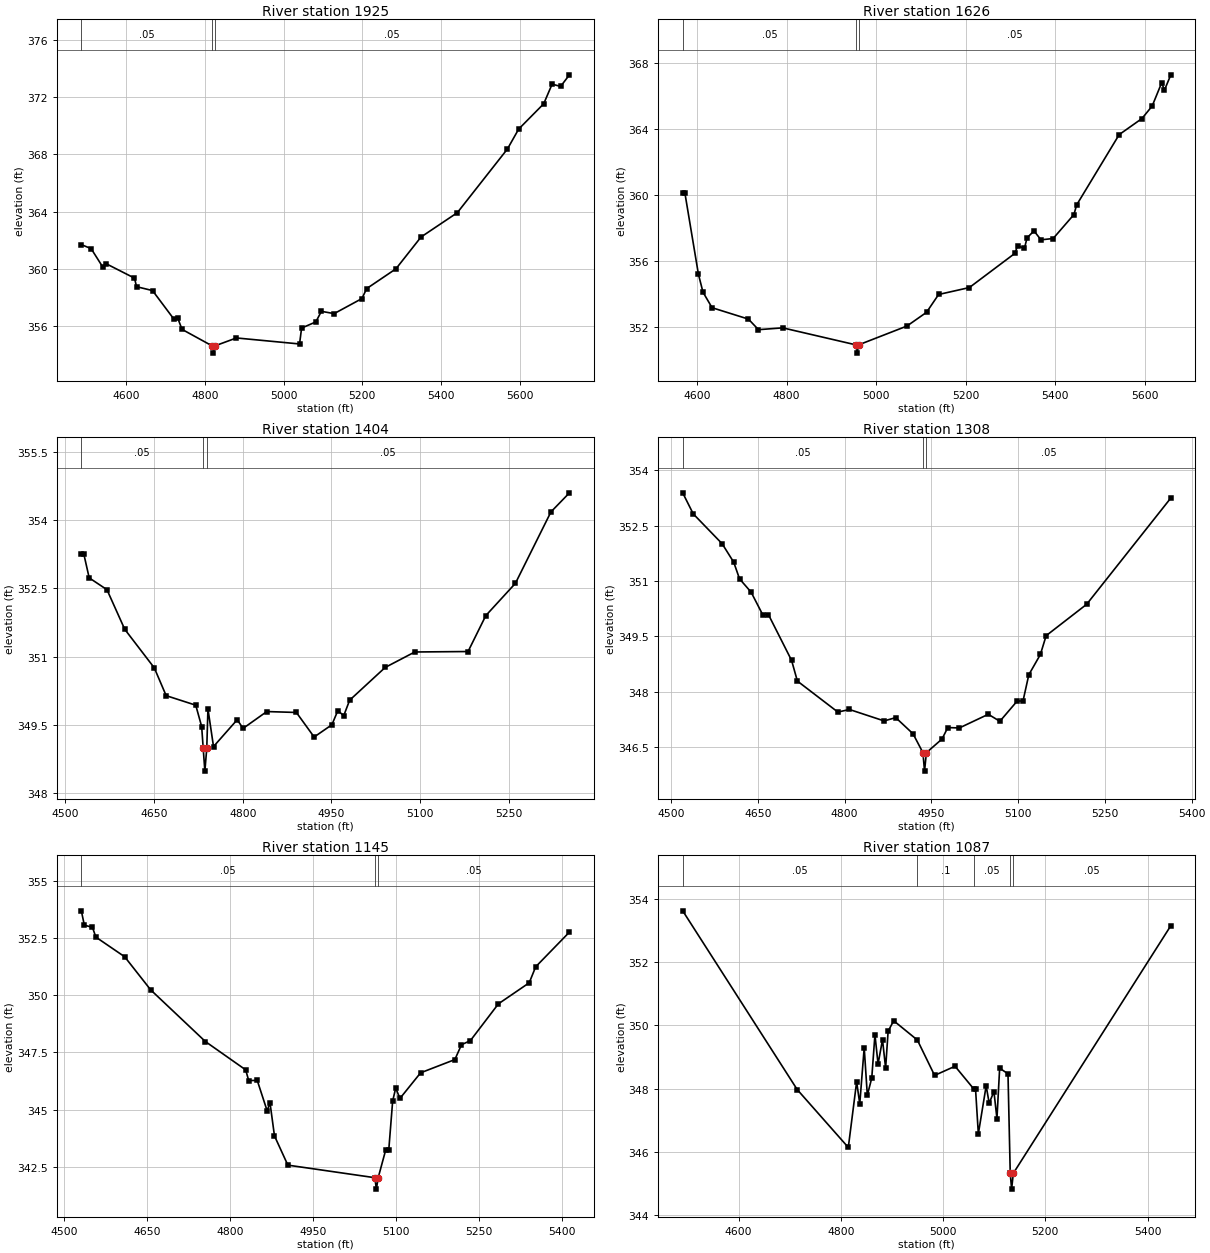
Type RM Length L Ch R = 1,1925,299,299,299
BEGIN DESCRIPTION:
UNT060 IN SUCR 4.0
END DESCRIPTION:
XS GIS Cut Line= 4
      2296107.14     13406130.22      2295756.47     13405998.29
      2295405.77     13406085.09      2295079.38     13406470.51
#Sta/Elev= 30
  4485.8  361.70  4510.7  361.42  4540.9  360.11  4549.3  360.36  4620.9  359.36
  4626.3  358.76  4666.8  358.49  4720.2  356.53  4730.9  356.57  4741.8  355.78
  4818.8  354.62  4821.6  354.12  4824.8  354.62  4880.1  355.18  5040.6  354.76
  5045.8  355.87  5082.0  356.30  5096.1  357.04  5128.6  356.88  5199.1  357.93
  5211.4  358.63  5285.7  360.01  5349.4  362.23  5441.7  363.93  5569.1  368.38
  5597.7  369.77  5661.4  371.54  5682.7  372.91  5704.3  372.75  5726.8  373.56
#Mann=3,-1,0
  4485.8    0.05       0  4818.8   0.035       0  4824.8    0.05       0
Bank Sta=4818.8,4824.8
Exp/Cntr=0.3,0.1

Type RM Length L Ch R = 1,1626,222,222,222
BEGIN DESCRIPTION:
Mapping XS 9d3e1545
END DESCRIPTION:
XS GIS Cut Line= 4
      2295902.29     13405810.78      2295607.16     13405758.70
      2295329.38     13405796.90      2294892.31     13406060.53
#Sta/Elev= 30
  4567.7  360.14  4572.5  360.14  4602.8  355.21  4613.0  354.12  4633.3  353.18
  4714.5  352.49  4737.0  351.85  4791.2  351.96  4954.7  350.93  4957.4  350.43
  4960.7  350.93  5068.7  352.07  5112.4  352.90  5139.4  353.98  5208.1  354.40
  5309.8  356.47  5315.7  356.92  5331.2  356.78  5337.0  357.41  5352.5  357.83
  5368.1  357.29  5395.3  357.37  5441.7  358.82  5447.7  359.40  5542.8  363.66
  5593.5  364.63  5616.5  365.39  5637.9  366.81  5643.7  366.34  5658.2  367.28
#Mann=3,-1,0
  4567.7    0.05       0  4954.7    0.03       0  4960.7    0.05       0
Bank Sta=4954.7,4960.7
Exp/Cntr=0.3,0.1

Type RM Length L Ch R = 1,1404,96,96,96
BEGIN DESCRIPTION:
UNT060 IN SUCR 3.0
END DESCRIPTION:
XS GIS Cut Line= 2
      2295851.04     13405580.75      2295026.45     13405585.09
#Sta/Elev= 30
  4527.4  353.26  4531.5  353.26  4540.7  352.73  4570.7  352.47  4600.7  351.60
  4650.7  350.75  4670.7  350.14  4720.7  349.93  4730.7  349.46  4733.3  348.98
  4736.1  348.48  4739.3  348.98  4741.3  349.85  4750.7  349.02  4790.7  349.61
  4800.7  349.42  4840.7  349.79  4890.7  349.77  4920.7  349.23  4950.7  349.50
  4960.7  349.81  4970.7  349.70  4980.7  350.04  5040.7  350.76  5090.7  351.10
  5180.7  351.11  5210.7  351.90  5260.7  352.61  5320.7  354.18  5352.0  354.60
#Mann=3,-1,0
  4527.4    0.05       0  4733.3    0.03       0  4739.3    0.05       0
Bank Sta=4733.3,4739.3
Exp/Cntr=0.3,0.1

Type RM Length L Ch R = 1,1308,163,163,163
BEGIN DESCRIPTION:
Mapping XS 842e0d69
END DESCRIPTION:
XS GIS Cut Line= 2
      2295855.92     13405485.45      2295012.26     13405494.12
#Sta/Elev= 30
  4520.3  353.39  4538.5  352.82  4588.5  352.01  4608.5  351.51  4618.5  351.06
  4638.5  350.70  4658.5  350.09  4668.5  350.09  4708.5  348.85  4718.5  348.29
  4788.5  347.45  4808.5  347.52  4868.5  347.21  4888.5  347.30  4918.5  346.86
  4935.5  346.35  4938.3  345.85  4941.5  346.35  4968.5  346.72  4978.5  347.03
  4998.5  347.02  5048.5  347.39  5068.5  347.20  5098.5  347.75  5108.5  347.75
  5118.5  348.46  5138.5  349.01  5148.5  349.52  5218.5  350.37  5364.0  353.25
#Mann=3,-1,0
  4520.3    0.05       0  4935.5    0.03       0  4941.5    0.05       0
Bank Sta=4935.5,4941.5
Exp/Cntr=0.3,0.1

Type RM Length L Ch R = 1,1145,58,58,58
BEGIN DESCRIPTION:
Mapping XS 2dd49276
END DESCRIPTION:
XS GIS Cut Line= 5
      2295842.98     13405457.25      2295495.72     13405355.24
      2295439.30     13405333.54      2295309.09     13405335.71
      2295012.30     13405480.86
#Sta/Elev= 30
  4530.9  353.70  4536.4  353.07  4551.0  352.98  4557.2  352.55  4609.3  351.69
  4656.4  350.24  4755.3  347.98  4828.2  346.74  4833.7  346.27  4849.1  346.28
  4867.0  344.95  4872.2  345.30  4880.3  343.85  4904.5  342.57  5061.9  342.02
  5064.6  341.52  5067.9  342.02  5081.7  343.25  5087.1  343.25  5094.1  345.38
  5099.6  345.94  5107.3  345.49  5144.6  346.61  5206.6  347.19  5218.6  347.84
  5234.7  348.02  5285.4  349.63  5341.1  350.55  5352.8  351.25  5413.9  352.77
#Mann=3,-1,0
  4530.9    0.05       0  5061.9    0.03       0  5067.9    0.05       0
Bank Sta=5061.9,5067.9
Exp/Cntr=0.3,0.1

Type RM Length L Ch R = 1,1087,37,37,37
BEGIN DESCRIPTION:
Mapping XS fa54ae81
END DESCRIPTION:
XS GIS Cut Line= 6
      2295842.93     13405437.70      2295532.62     13405344.39
      2295487.04     13405279.28      2295322.11     13405277.11
      2295274.37     13405307.50      2294980.99     13405458.50
#Sta/Elev= 30
  4490.6  353.63  4714.7  347.97  4814.6  346.14  4830.9  348.22  4837.0  347.52
  4845.7  349.30  4851.8  347.79  4860.5  348.34  4866.7  349.71  4872.8  348.78
  4881.5  349.55  4887.6  348.65  4892.5  349.82  4903.4  350.15  4949.7  349.54
  4983.4  348.42  5023.4  348.71  5060.1  347.99  5063.5  347.99  5069.0  346.57
  5084.3  348.09  5090.2  347.54  5099.5  347.91  5105.4  347.05  5110.7  348.65
  5127.0  348.47  5131.4  345.32  5134.1  344.82  5137.4  345.32  5445.6  353.16
#Mann=5,-1,0
  4490.6    0.05       0  4949.7     0.1       0  5060.1    0.05       0
  5131.4    0.07       0  5137.4    0.05       0
Bank Sta=5131.4,5137.4
Exp/Cntr=0.3,0.1

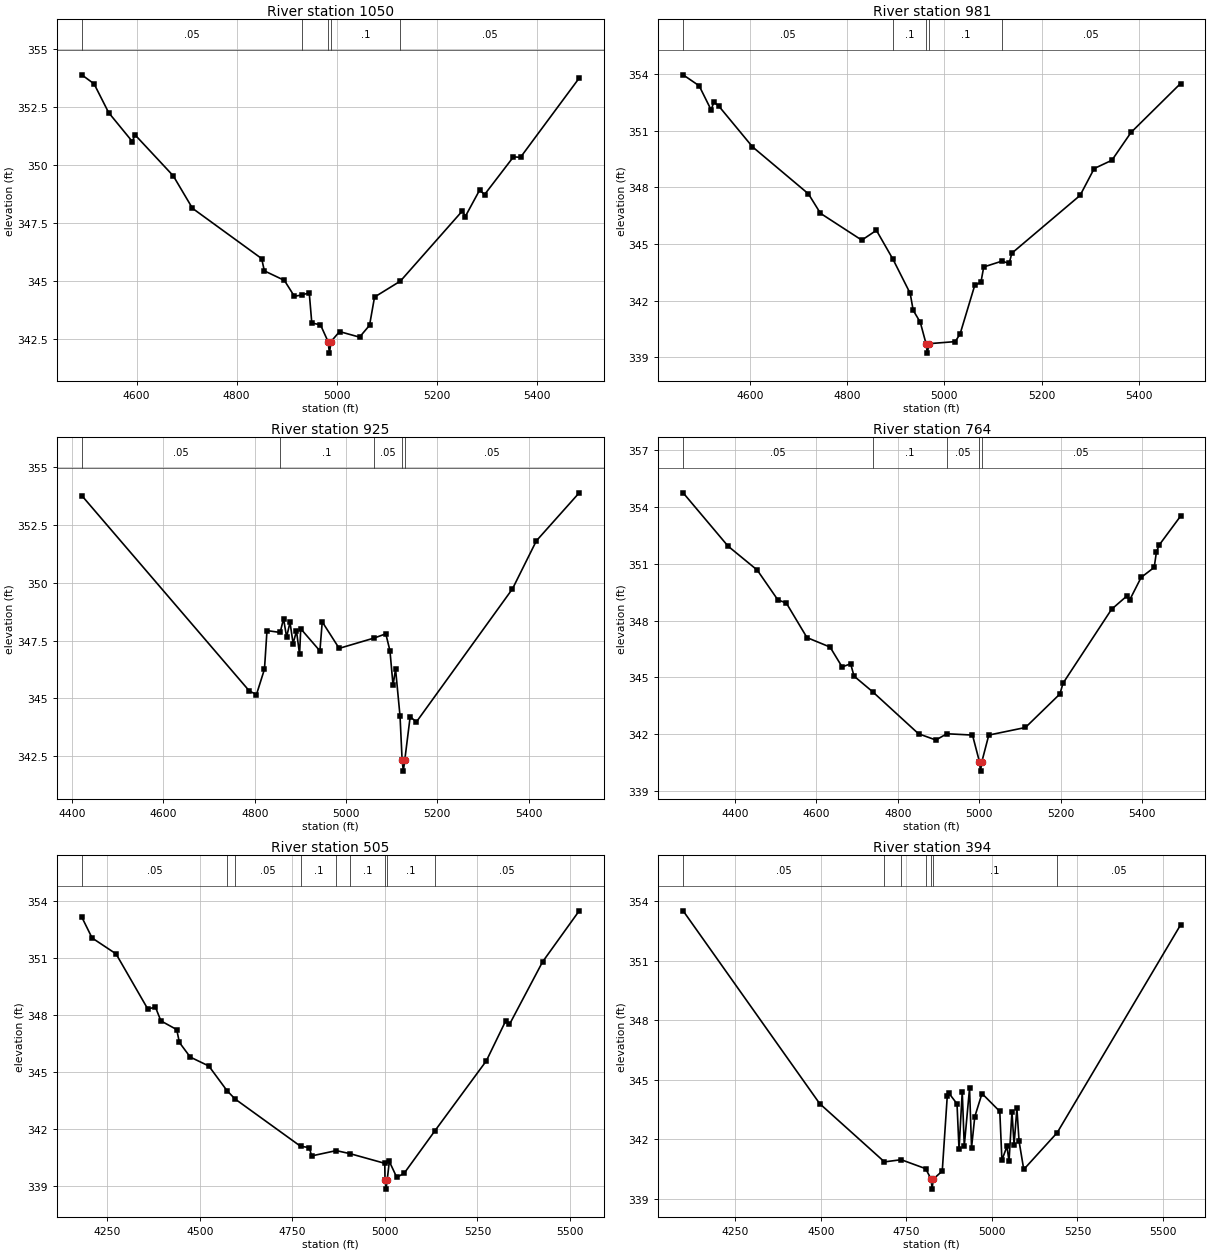
Type RM Length L Ch R = 1,1050,69,69,69
BEGIN DESCRIPTION:
Mapping XS 3dbebcdf
END DESCRIPTION:
XS GIS Cut Line= 5
      2295851.63     13405402.98      2295487.04     13405248.90
      2295408.92     13405240.22      2295267.86     13405242.39
      2294931.04     13405417.28
#Sta/Elev= 30
  4490.3  353.90  4514.9  353.51  4544.0  352.27  4591.4  351.02  4596.8  351.31
  4673.3  349.54  4711.7  348.14  4850.1  345.97  4855.5  345.44  4895.5  345.03
  4915.6  344.34  4930.1  344.40  4945.3  344.49  4950.4  343.19  4967.8  343.11
  4982.9  342.39  4985.7  341.89  4988.9  342.39  5005.9  342.82  5045.9  342.58
  5065.9  343.09  5075.9  344.31  5127.7  345.00  5251.7  348.03  5257.3  347.78
  5286.2  348.93  5295.9  348.73  5353.8  350.36  5367.9  350.34  5485.3  353.76
#Mann=5,-1,0
  4490.3    0.05       0  4930.1     0.1       0  4982.9    0.07       0
  4988.9     0.1       0  5127.7    0.05       0
Bank Sta=4982.9,4988.9
Exp/Cntr=0.3,0.1

Type RM Length L Ch R = 1,981,56,56,56
BEGIN DESCRIPTION:
Mapping XS 00436e88
END DESCRIPTION:
XS GIS Cut Line= 5
      2295856.00     13405372.61      2295432.79     13405212.01
      2295378.54     13405172.95      2295287.39     13405177.29
      2294908.08     13405342.02
#Sta/Elev= 30
  4462.0  353.96  4495.0  353.38  4519.7  352.10  4525.1  352.51  4535.0  352.32
  4604.8  350.15  4720.0  347.66  4744.8  346.63  4829.9  345.21  4860.0  345.73
  4894.3  344.19  4929.6  342.39  4935.7  341.50  4950.4  340.86  4962.2  339.73
  4964.9  339.23  4968.2  339.73  5022.4  339.84  5032.4  340.25  5062.4  342.81
  5075.3  342.99  5081.0  343.79  5118.5  344.10  5133.4  343.98  5138.9  344.52
  5279.5  347.58  5308.5  349.00  5345.0  349.44  5384.3  350.91  5486.3  353.50
#Mann=5,-1,0
  4462.0    0.05       0  4894.3     0.1       0  4962.2    0.07       0
  4968.2     0.1       0  5118.5    0.05       0
Bank Sta=4962.2,4968.2
Exp/Cntr=0.3,0.1

Type RM Length L Ch R = 1,925,161,161,161
BEGIN DESCRIPTION:
Mapping XS 15de79e6
END DESCRIPTION:
XS GIS Cut Line= 6
      2295861.58     13405350.45      2295482.70     13405177.29
      2295439.30     13405129.54      2295378.54     13405118.69
      2295259.18     13405123.03      2294872.89     13405305.33
#Sta/Elev= 30
  4421.3  353.78  4788.4  345.31  4803.9  345.16  4821.4  346.26  4826.9  347.93
  4855.7  347.85  4863.2  348.44  4869.9  347.65  4877.3  348.29  4884.1  347.37
  4891.5  347.91  4898.3  346.90  4900.8  348.01  4942.8  347.05  4947.9  348.31
  4985.0  347.16  5062.0  347.61  5087.1  347.79  5096.2  347.06  5103.0  345.56
  5108.5  346.26  5118.3  344.22  5122.8  342.34  5125.5  341.84  5128.8  342.34
  5140.5  344.20  5154.1  343.97  5364.6  349.74  5416.9  351.82  5510.7  353.90
#Mann=5,-1,0
  4421.3    0.05       0  4855.7     0.1       0  5062.0    0.05       0
  5122.8    0.07       0  5128.8    0.05       0
Bank Sta=5122.8,5128.8
Exp/Cntr=0.3,0.1

Type RM Length L Ch R = 1,764,259,259,259
BEGIN DESCRIPTION:
UNT060 IN SUCR 2.0
END DESCRIPTION:
XS GIS Cut Line= 4
      2295892.03     13405315.77      2295405.88     13404977.20
      2295084.70     13404977.20      2294811.96     13405120.07
#Sta/Elev= 30
  4272.5  354.73  4382.8  351.92  4454.4  350.66  4505.0  349.09  4525.9  348.92
  4576.6  347.10  4633.3  346.60  4663.0  345.55  4683.9  345.72  4692.1  345.07
  4738.1  344.24  4850.5  342.03  4893.1  341.70  4920.2  342.03  4983.1  341.96
  5000.1  340.56  5002.8  340.06  5006.1  340.56  5023.1  341.96  5113.1  342.36
  5197.9  344.13  5205.3  344.69  5324.6  348.59  5363.1  349.31  5368.8  349.07
  5397.2  350.27  5429.3  350.80  5434.9  351.63  5442.3  352.00  5494.0  353.50
#Mann=5,-1,0
  4272.5    0.05       0  4738.1     0.1       0  4920.2    0.05       0
  5000.1    0.03       0  5006.1    0.05       0
Bank Sta=5000.1,5006.1
Exp/Cntr=0.3,0.1

Type RM Length L Ch R = 1,505,111,111,111
BEGIN DESCRIPTION:
Mapping XS ed7ce26c
END DESCRIPTION:
XS GIS Cut Line= 5
      2295844.27     13405228.96      2295219.25     13404768.87
      2295175.84     13404751.51      2295097.72     13404760.19
      2294698.40     13404951.17
#Sta/Elev= 30
  4181.0  353.15  4208.8  352.05  4273.6  351.21  4359.2  348.31  4380.1  348.40
  4394.7  347.68  4437.5  347.22  4444.8  346.54  4474.1  345.77  4524.3  345.30
  4573.4  344.00  4595.3  343.56  4772.1  341.07  4795.8  341.00  4802.0  340.56
  4868.5  340.84  4905.8  340.68  4999.7  340.17  5000.4  339.31  5003.1  338.81
  5006.4  339.31  5012.0  340.27  5032.1  339.43  5052.3  339.65  5135.8  341.90
  5274.1  345.57  5326.3  347.67  5336.6  347.49  5426.1  350.79  5525.1  353.48
#Mann=9,-1,0
  4181.0    0.05       0  4573.4     0.1       0  4595.3    0.05       0
  4772.1     0.1       0  4868.5    0.05       0  4905.8     0.1       0
  5000.4    0.07       0  5006.4     0.1       0  5135.8    0.05       0
Bank Sta=5000.4,5006.4
Exp/Cntr=0.3,0.1

Type RM Length L Ch R = 1,394,87,87,87
BEGIN DESCRIPTION:
Mapping XS 1d8c91a4
END DESCRIPTION:
XS GIS Cut Line= 6
      2295874.60     13405176.83      2295245.29     13404721.12
      2295201.89     13404651.68      2295145.46     13404643.00
      2295080.36     13404690.74      2294663.65     13404877.39
#Sta/Elev= 30
  4097.9  353.50  4496.9  343.80  4686.1  340.87  4735.0  340.98  4806.4  340.53
  4822.6  340.00  4825.3  339.50  4828.6  340.00  4855.0  340.41  4869.7  344.20
  4874.3  344.33  4898.1  343.79  4904.0  341.50  4913.4  344.41  4919.3  341.67
  4934.7  344.57  4940.6  341.59  4950.0  343.14  4971.1  344.31  5023.1  343.41
  5029.3  340.95  5043.9  341.65  5050.1  340.90  5058.6  343.39  5064.8  341.74
  5073.1  343.56  5079.4  341.91  5093.1  340.49  5190.8  342.34  5551.2  352.79
#Mann=7,-1,0
  4097.9    0.05       0  4686.1     0.1       0  4735.0    0.05       0
  4806.4     0.1       0  4822.6    0.07       0  4828.6     0.1       0
  5190.8    0.05       0
Bank Sta=4822.6,4828.6
Exp/Cntr=0.3,0.1

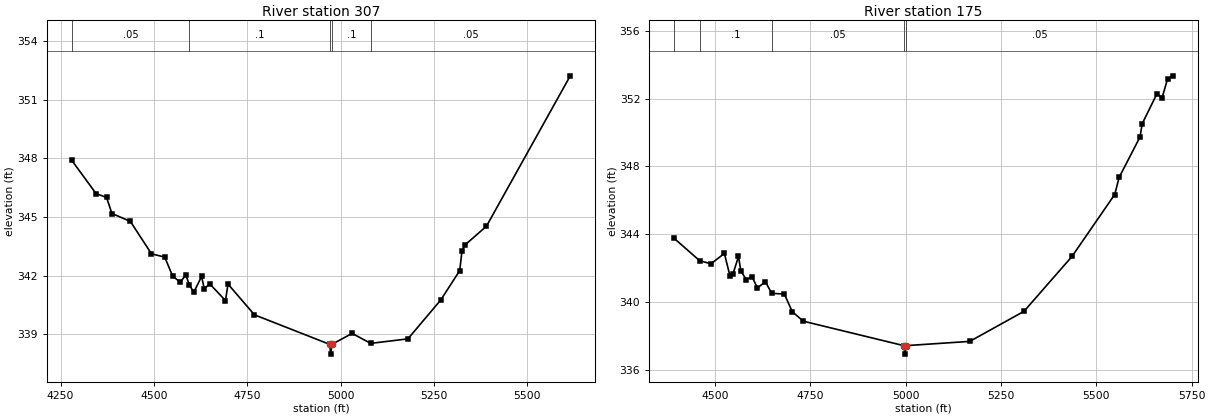
Type RM Length L Ch R = 1,307,132,132,132
BEGIN DESCRIPTION:
Mapping XS 7f98cb2b
END DESCRIPTION:
XS GIS Cut Line= 4
      2295709.14     13405007.94      2295256.05     13404578.29
      2294972.19     13404518.39      2294625.81     13404758.00
#Sta/Elev= 30
  4279.4  347.91  4344.9  346.20  4373.2  346.00  4387.3  345.18  4436.7  344.78
  4493.3  343.12  4528.9  342.95  4550.0  341.98  4571.0  341.66  4585.2  342.06
  4594.3  341.55  4606.6  341.15  4627.6  341.96  4634.9  341.32  4649.1  341.59
  4691.5  340.73  4698.4  341.57  4769.2  340.00  4970.6  338.49  4973.4  337.99
  4976.6  338.49  5030.9  339.05  5080.4  338.54  5180.2  338.77  5268.3  340.76
  5319.0  342.26  5325.0  343.25  5333.1  343.57  5390.6  344.53  5615.1  352.22
#Mann=5,-1,0
  4279.4    0.05       0  4594.3     0.1       0  4970.6    0.07       0
  4976.6     0.1       0  5080.4    0.05       0
Bank Sta=4970.6,4976.6
Exp/Cntr=0.3,0.1

Type RM Length L Ch R = 1,175,0,0,0
BEGIN DESCRIPTION:
UNT060 IN SUCR 1.0
END DESCRIPTION:
XS GIS Cut Line= 4
      2295640.28     13404779.66      2295193.47     13404427.42
      2294880.37     13404424.16      2294502.41     13404619.66
#Sta/Elev= 30
  4393.4  343.76  4460.0  342.45  4489.5  342.27  4524.7  342.88  4539.2  341.57
  4547.2  341.67  4561.7  342.70  4568.0  341.84  4582.5  341.33  4596.9  341.52
  4611.4  340.85  4632.2  341.21  4648.9  340.53  4681.9  340.49  4702.7  339.45
  4731.6  338.89  4995.1  337.45  4997.9  336.95  5001.1  337.45  5168.1  337.70
  5310.3  339.47  5436.1  342.70  5548.2  346.35  5559.9  347.36  5614.6  349.74
  5620.3  350.52  5658.9  352.28  5672.5  352.05  5686.7  353.15  5701.0  353.34
#Mann=5,-1,0
  4393.4    0.05       0  4460.0     0.1       0  4648.9    0.05       0
  4995.1    0.03       0  5001.1    0.05       0
Bank Sta=4995.1,5001.1
Exp/Cntr=0.3,0.1

Chan Stop Cuts=-1