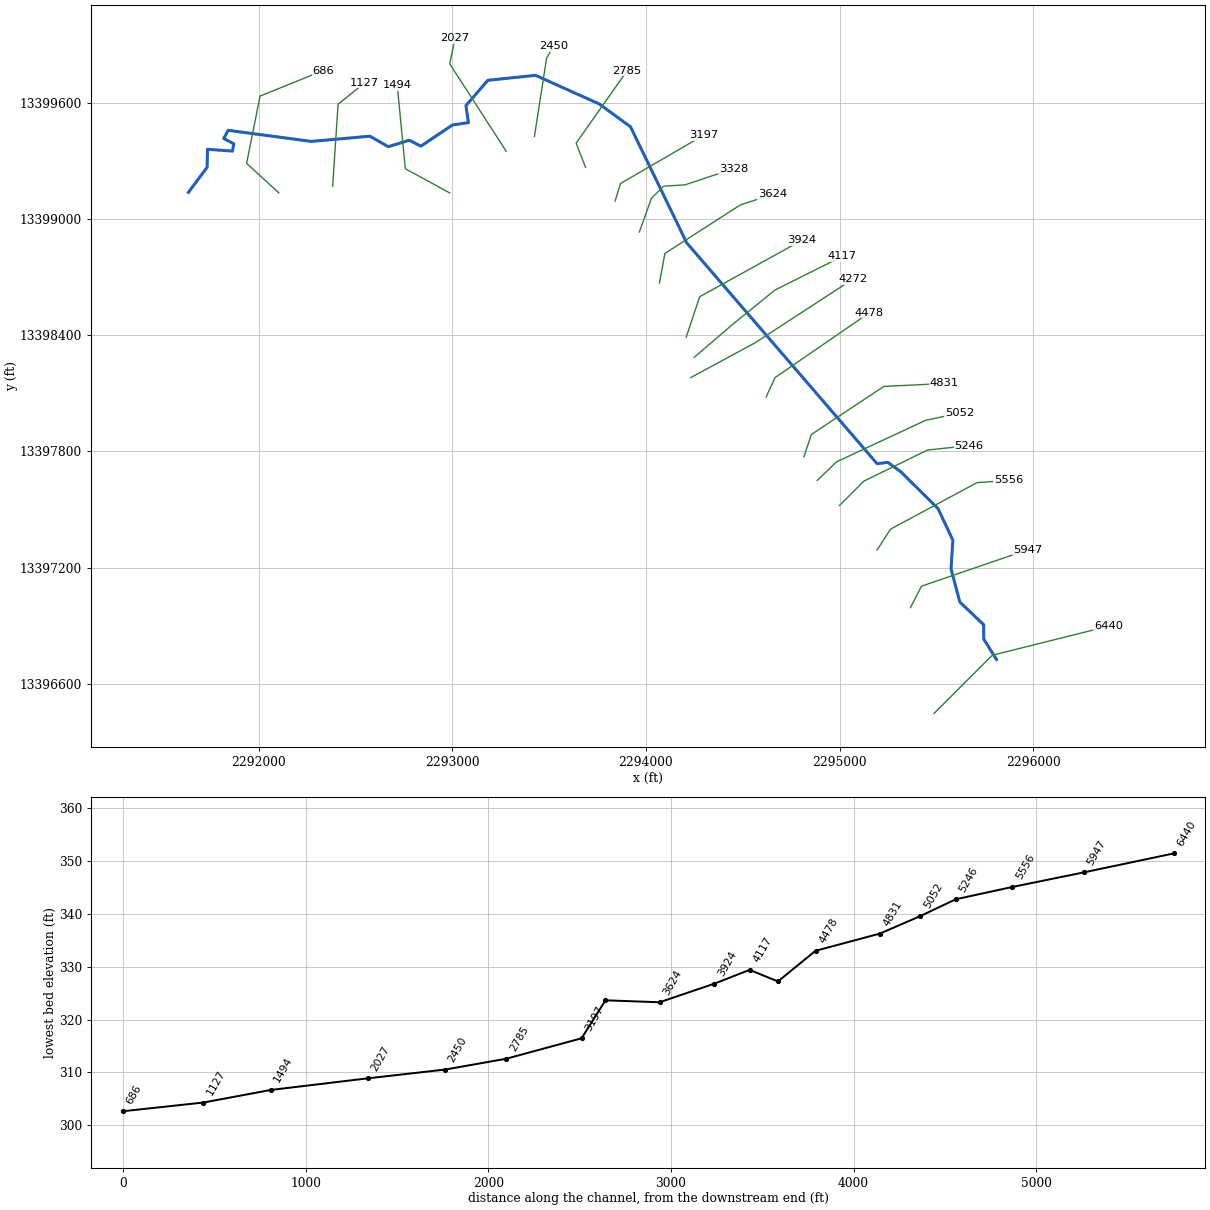
--- UNT061 IN SUCR.prj (project) ---

Proj Title=UNT061 IN SUCR Base Level Engineering
Current Plan=p01
Default Exp/Contr=0.3,0.1
English Units
Geom File=g01
Flow File=f01
Plan File=p01
Y Axis Title=Elevation
X Axis Title(PF)=Main Channel Distance
X Axis Title(XS)=Station
BEGIN DESCRIPTION:
UNT061 IN SUCR
END DESCRIPTION:
DSS Export Rating Curves= 0
DSS Export Rating Curve Sorted= 0
DSS Export Volume Flow Curves= 0
DXF OffsetX= 0
DXF OffsetY= 0
DXF ScaleX= 1
DXF ScaleY= 10

--- UNT061 IN SUCR.p01 (plan) ---

Plan Title=Multiple Run
Short Identifier=Multiple
Geom File=g01
Flow File=f01
Subcritical Flow
K Sum by GR= 0
Std Step Tol= 0.01
Critical Tol= 0.01
Num of Std Step Trials= 20
Max Error Tol= 0.3
Flow Tol Ratio= 0.001
Split Flow NTrial= 30
Split Flow Tol= 0.02
Split Flow Ratio= 0.02
Log Output Level= 0
Friction Slope Method= 1
Unsteady Friction Slope Method= 2
Unsteady Bridges Friction Slope Method= 1
Parabolic Critical Depth
Global Vel Dist=  1 , 1 , 1
Global Log Level= 0
CheckData=True
Encroach Param= -1, 0, 0, 0
BEGIN DESCRIPTION:
Multiple Run
END DESCRIPTION:

--- UNT061 IN SUCR.f01 (steady flow) ---

Flow Title=Multiple
Program Version=4.10
Number of Profiles= 7
Profile Names=10-year,25-year,50-year,1pct_min,100-year,1pct_plu,500-year
River Rch & RM=UNT061 IN SUCR,Reach-1         ,6440
     439     612     755     682     922    1247    1381
River Rch & RM=UNT061 IN SUCR,Reach-1         ,4272
     743    1069    1347    1239    1676    2266    2606
River Rch & RM=UNT061 IN SUCR,Reach-1         ,4117
     743    1069    1347    1239    1676    2266    2606
Boundary for River Rch & Prof#=UNT061 IN SUCR,Reach-1         , 1
Up Type= 0
Dn Type= 3
Dn Slope=0.0029
Boundary for River Rch & Prof#=UNT061 IN SUCR,Reach-1         , 2
Up Type= 0
Dn Type= 3
Dn Slope=0.0029
Boundary for River Rch & Prof#=UNT061 IN SUCR,Reach-1         , 3
Up Type= 0
Dn Type= 3
Dn Slope=0.0029
Boundary for River Rch & Prof#=UNT061 IN SUCR,Reach-1         , 4
Up Type= 0
Dn Type= 3
Dn Slope=0.0029
Boundary for River Rch & Prof#=UNT061 IN SUCR,Reach-1         , 5
Up Type= 0
Dn Type= 3
Dn Slope=0.0029
Boundary for River Rch & Prof#=UNT061 IN SUCR,Reach-1         , 6
Up Type= 0
Dn Type= 3
Dn Slope=0.0029
Boundary for River Rch & Prof#=UNT061 IN SUCR,Reach-1         , 7
Up Type= 0
Dn Type= 3
Dn Slope=0.0029
DSS Import GetInterval= 0
DSS Import GetPeak= 0
DSS Import FillOption= 0

--- UNT061 IN SUCR.g01 (geometry) ---

Geom Title=Existing Conditions
Program Version=4.10

River Reach=UNT061 IN SUCR  ,Reach-1
Reach XY= 30
      2295809.83     13396725.03      2295744.32     13396830.14
      2295743.31     13396905.05      2295620.68     13397021.48
       2295575.1     13397192.92      2295584.64     13397340.93
      2295508.34     13397503.53      2295315.89     13397694.37
      2295248.87     13397742.93      2295193.29     13397736.03
       2294210.2     13398876.57      2293920.27     13399475.53
      2293758.38     13399593.59      2293429.82     13399741.16
      2293183.73     13399715.55      2293070.44     13399584.91
      2293083.46      13399496.8      2293001.43     13399485.08
      2292837.81     13399375.71      2292777.91     13399406.09
       2292669.4     13399372.67      2292574.78     13399426.92
      2292271.83     13399400.01      2291843.01      13399457.3
      2291820.01      13399415.2        2291872.     13399387.47
      2291864.93     13399350.22      2291736.22     13399359.24
       2291734.1     13399266.25      2291637.72     13399136.86

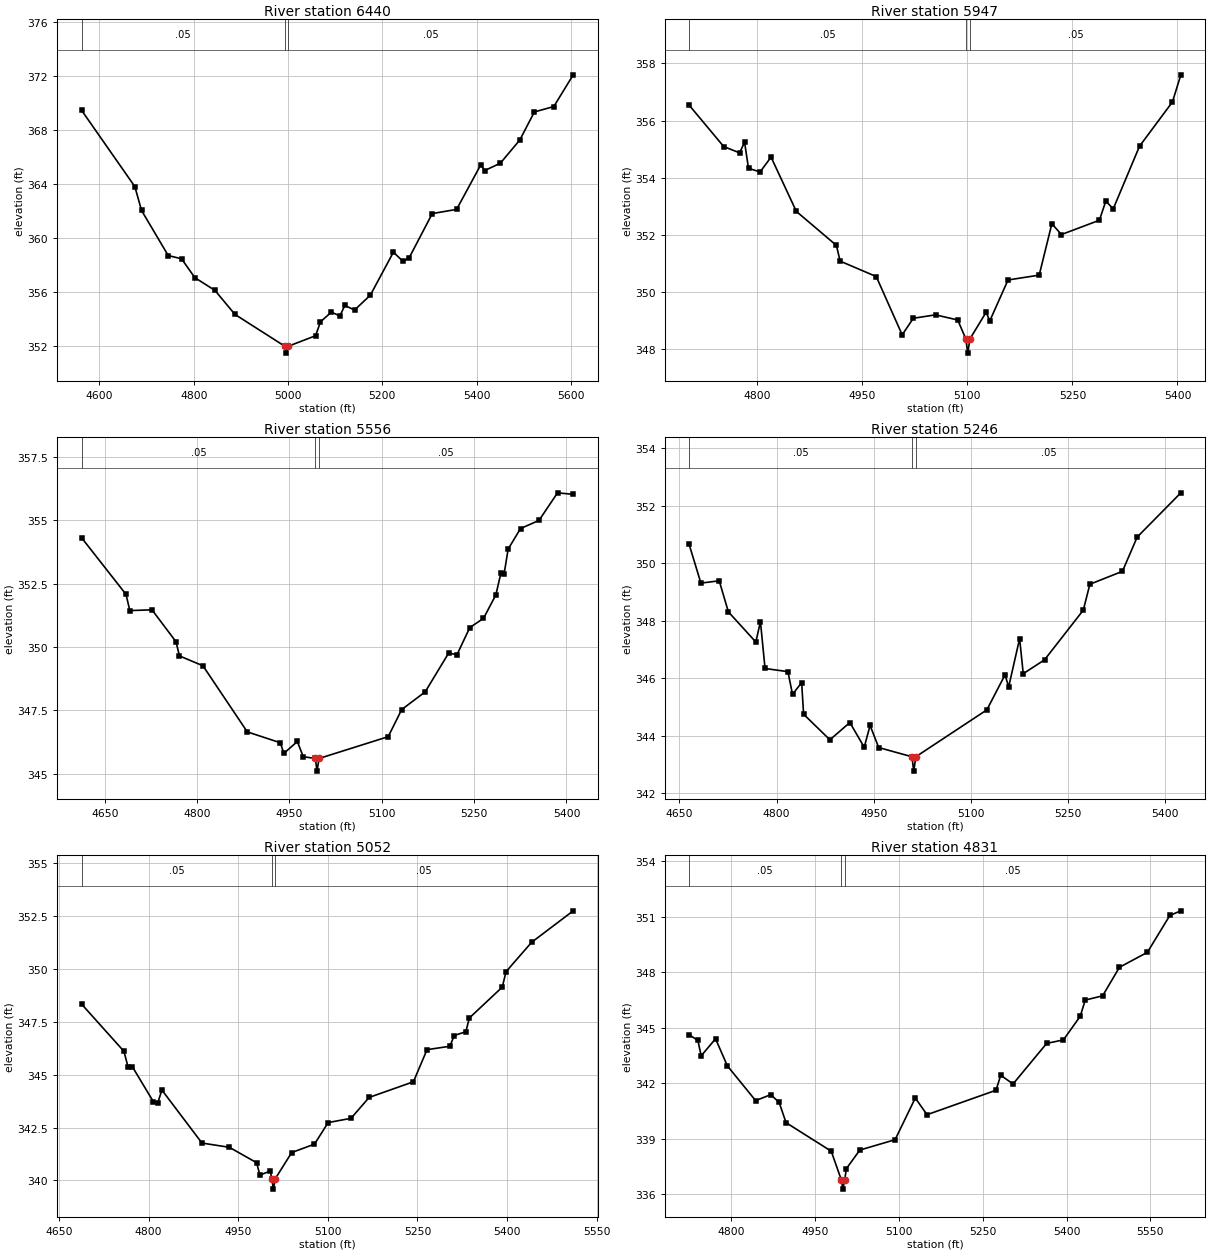
Type RM Length L Ch R = 1 ,6440    ,493,493,493
BEGIN DESCRIPTION:
UNT061 IN SUCR 8.0
END DESCRIPTION:
XS GIS Cut Line= 3
      2295487.71     13396446.85      2295787.72     13396746.85
      2296387.68     13396896.85
#Sta/Elev= 30
  4562.1  369.45  4675.2  363.79  4689.4  362.02    4746  358.68  4774.2  358.44
  4802.5  357.04    4845   356.1  4887.4  354.32  4993.7  351.95  4996.4  351.45
  4999.7  351.95  5058.5  352.74  5068.8  353.77    5092  354.49  5110.1   354.2
  5120.4  354.99    5141  354.64  5174.5  355.74  5223.5  358.93  5244.1  358.24
    5257  358.52  5305.9  361.79  5357.5   362.1    5409  365.42  5416.7  364.97
  5450.2  365.52  5491.5  367.24  5522.4  369.32  5563.6  369.72  5604.8  372.07
#Mann= 3 ,-1 , 0
  4562.1     .05       0  4993.7     .04       0  4999.7     .05       0
Bank Sta=4993.7,4999.7
XS Rating Curve= 0 ,0
Exp/Cntr=0.3,0.1

Type RM Length L Ch R = 1 ,5947    ,391,391,391
BEGIN DESCRIPTION:
UNT061 IN SUCR 7.0
END DESCRIPTION:
XS GIS Cut Line= 3
      2295365.61     13396992.93       2295422.9     13397103.68
      2295969.04     13397290.82
#Sta/Elev= 30
  4702.8  356.54  4752.2  355.09  4774.8  354.87    4782  355.24  4787.6  354.33
  4804.1   354.2  4819.8  354.72  4855.9  352.82  4913.1  351.63  4918.4  351.08
    4970  350.54    5007   348.5  5022.9  349.08  5054.6   349.2  5086.3  349.02
  5097.8  348.36  5100.6  347.86  5103.8  348.36  5126.8  349.29  5132.1  348.99
  5158.1  350.42  5202.6  350.59  5220.7  352.39  5234.3  352.01  5288.5  352.51
  5297.7  353.18  5308.3  352.91  5345.8   355.1  5392.8  356.65  5404.8   357.6
#Mann= 3 ,-1 , 0
  4702.8     .05       0  5097.8     .03       0  5103.8     .05       0
Bank Sta=5097.8,5103.8
XS Rating Curve= 0 ,0
Exp/Cntr=0.3,0.1

Type RM Length L Ch R = 1 ,5556    ,310,310,310
BEGIN DESCRIPTION:
UNT061 IN SUCR 6.0
END DESCRIPTION:
XS GIS Cut Line= 4
      2295193.77     13397290.84       2295262.5     13397397.75
      2295709.32     13397638.34      2295873.15     13397649.77
#Sta/Elev= 30
  4612.2  354.32  4684.5  352.08  4690.7  351.44  4726.7  351.47  4765.7  350.21
  4771.3  349.65  4809.5  349.26  4881.5  346.65  4935.2  346.22  4940.9   345.8
  4962.8  346.27  4972.4  345.67  4992.1   345.6  4994.8   345.1  4998.1   345.6
  5110.4  346.46  5132.3  347.53  5170.5  348.23  5208.6  349.76  5222.2   349.7
    5243  350.77  5265.2  351.13  5285.3  352.06  5293.7  352.94  5298.8   352.9
  5305.3  353.87  5325.4  354.68  5355.4     355  5385.5  356.09    5411  356.03
#Mann= 3 ,-1 , 0
  4612.2     .05       0  4992.1     .03       0  4998.1     .05       0
Bank Sta=4992.1,4998.1
XS Rating Curve= 0 ,0
Exp/Cntr=0.3,0.1

Type RM Length L Ch R = 1 ,5246    ,194,194,194
BEGIN DESCRIPTION:
Mapping XS d0a5a345
END DESCRIPTION:
XS GIS Cut Line= 4
      2294998.95     13397519.92      2295125.01     13397645.98
      2295453.45     13397806.38      2295667.34      13397829.3
#Sta/Elev= 30
  4665.1  350.66  4683.3  349.31  4711.6  349.39  4725.7  348.31  4768.1  347.26
  4775.2  347.97  4782.3  346.34  4817.6  346.23  4824.7  345.44  4838.8  345.85
  4841.8  344.75  4882.4  343.86  4913.2  344.46  4935.4   343.6  4944.4  344.36
  4957.7  343.59    5009  343.27  5011.8  342.77    5015  343.27  5124.6   344.9
  5152.7  346.12  5158.3   345.7  5175.2  347.38  5180.8  346.16  5213.6  346.64
  5273.5  348.37  5283.6  349.27  5333.9  349.72  5356.6  350.91    5424  352.45
#Mann= 3 ,-1 , 0
  4665.1     .05       0    5009     .03       0    5015     .05       0
Bank Sta=5009,5015
XS Rating Curve= 0 ,0
Exp/Cntr=0.3,0.1

Type RM Length L Ch R = 1 ,5052    ,221,221,221
BEGIN DESCRIPTION:
Mapping XS c1187a68
END DESCRIPTION:
XS GIS Cut Line= 4
       2294884.4     13397649.79      2294983.71     13397745.28
      2295441.99     13397959.14       2295617.7     13397997.34
#Sta/Elev= 30
  4687.6  348.35  4758.7  346.11  4765.6  345.36  4772.8  345.38  4808.1  343.72
  4815.3  343.67  4822.2  344.28  4889.3  341.77  4935.1  341.57  4980.8  340.84
  4986.3  340.25  5003.6  340.45  5006.2  340.09  5008.9  339.59  5012.2  340.09
  5039.5  341.32  5077.7  341.72  5100.6  342.74  5138.8  342.94  5169.2  343.93
  5243.3  344.67  5266.1  346.19  5304.3  346.35  5311.8  346.86  5331.1  347.04
    5337  347.69  5392.1  349.15  5398.4  349.88  5441.2  351.27  5510.9  352.76
#Mann= 3 ,-1 , 0
  4687.6     .05       0  5006.2     .03       0  5012.2     .05       0
Bank Sta=5006.2,5012.2
XS Rating Curve= 0 ,0
Exp/Cntr=0.3,0.1

Type RM Length L Ch R = 1 ,4831    ,353,353,353
BEGIN DESCRIPTION:
UNT061 IN SUCR 5.0
END DESCRIPTION:
XS GIS Cut Line= 4
      2294815.66     13397771.97      2294853.86     13397886.58
      2295228.13     13398134.82      2295537.43     13398150.09
#Sta/Elev= 30
  4724.8  344.62  4740.5  344.31  4746.4  343.48  4772.1   344.4  4793.2  342.94
  4843.8  341.06  4870.7  341.38  4885.8  340.97  4898.2  339.87    4979  338.33
  4997.1  336.78  4999.8  336.28  5003.1  336.78  5006.2  337.39  5030.2  338.39
  5093.3  338.95  5129.4   341.2  5150.4   340.3  5273.8  341.62  5282.2  342.43
  5304.3  341.96  5364.4  344.15  5394.4  344.34  5424.5  345.62  5433.4  346.49
  5464.5  346.72  5494.6  348.26  5544.6  349.07  5584.7  351.06  5604.4  351.31
#Mann= 3 ,-1 , 0
  4724.8     .05       0  4997.1     .03       0  5003.1     .05       0
Bank Sta=4997.1,5003.1
XS Rating Curve= 0 ,0
Exp/Cntr=0.3,0.1

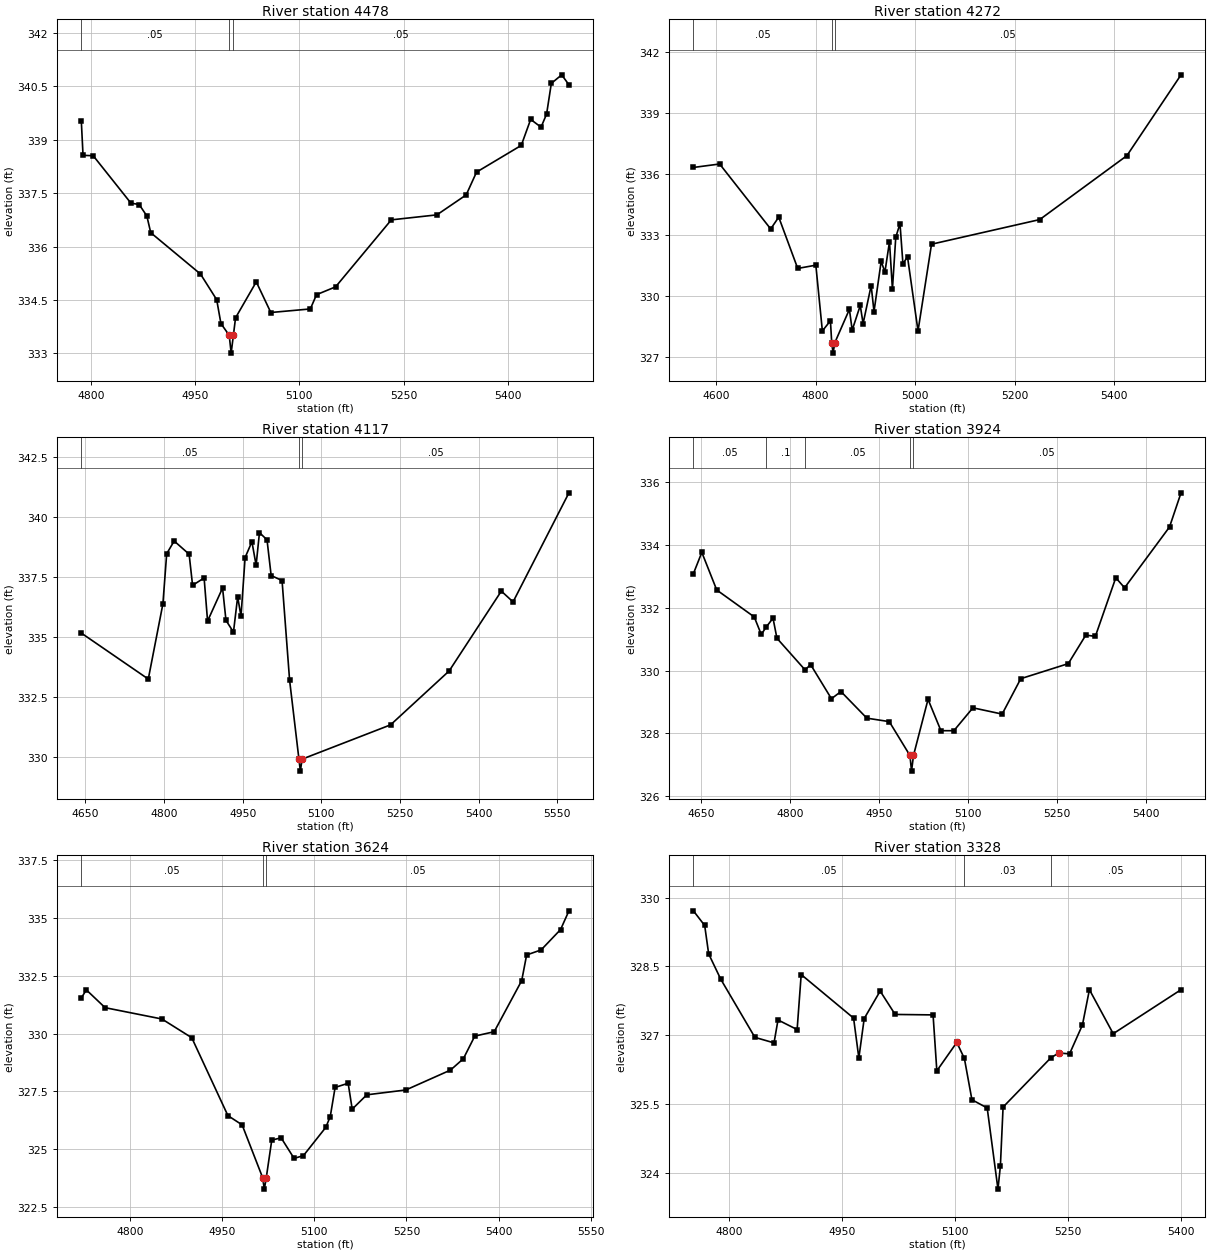
Type RM Length L Ch R = 1 ,4478    ,206,206,206
BEGIN DESCRIPTION:
Mapping XS a355ab6d
END DESCRIPTION:
XS GIS Cut Line= 3
      2294620.88     13398081.31      2294666.73     13398180.65
      2295154.14     13398515.74
#Sta/Elev= 30
  4786.5  339.53    4789  338.56  4803.6  338.55  4857.8  337.22  4869.7  337.18
  4880.7  336.86  4886.3  336.39  4957.8  335.23  4981.1  334.51  4987.2  333.84
  4999.1  333.51  5001.9  333.01  5005.1  333.51  5008.2     334    5038  335.01
  5058.9  334.15  5115.7  334.25  5124.6  334.65    5152  334.87  5232.1  336.75
  5297.6  336.89  5339.7  337.45  5354.6  338.09  5418.9  338.84  5432.4  339.57
  5447.3  339.35  5455.3  339.72  5462.1  340.58    5477  340.82  5487.4  340.54
#Mann= 3 ,-1 , 0
  4786.5     .05       0  4999.1     .03       0  5005.1     .05       0
Bank Sta=4999.1,5005.1
XS Rating Curve= 0 ,0
Exp/Cntr=0.3,0.1

Type RM Length L Ch R = 1 ,4272    ,155,155,155
BEGIN DESCRIPTION:
UNT061 IN SUCR 4.0
END DESCRIPTION:
XS GIS Cut Line= 3
      2294231.38     13398180.66      2294563.62     13398360.14
      2295067.75     13398688.59
#Sta/Elev= 30
  4554.5  336.33  4607.2   336.5  4709.7  333.31  4725.9  333.89    4764  331.37
  4800.4  331.53  4813.5   328.3  4829.7   328.8  4832.3  327.71  4835.1  327.21
  4838.3  327.71  4867.8  329.36  4873.4  328.34  4889.6  329.55  4895.3  328.66
  4911.5  330.53  4917.2  329.25  4931.6  331.72  4939.1  331.19  4948.3  332.68
  4954.2  330.35  4960.9   332.9  4969.4  333.57  4975.3   331.6  4984.5  331.94
  5005.6   328.3  5032.7  332.56    5250  333.77  5425.1  336.91  5533.8  340.88
#Mann= 3 ,-1 , 0
  4554.5     .05       0  4832.3     .03       0  4838.3     .05       0
Bank Sta=4832.3,4838.3
XS Rating Curve= 0 ,0
Exp/Cntr=0.3,0.1

Type RM Length L Ch R = 1 ,4117    ,193,193,193
BEGIN DESCRIPTION:
Mapping XS 4b4adb6c
END DESCRIPTION:
XS GIS Cut Line= 4
      2294249.49      13398285.4      2294443.94     13398452.07
      2294666.16     13398632.63      2295013.08     13398806.09
#Sta/Elev= 30
  4642.1  335.16  4769.9  333.24  4797.8  336.38    4805  338.47  4819.3     339
  4847.8  338.45  4854.4  337.15  4876.4  337.46    4883  335.66  4911.6  337.04
  4918.1  335.69  4932.4   335.2  4940.4  336.67  4946.8  335.86  4954.6  338.31
  4967.6  338.97  4975.6  337.99    4982  339.35  4996.4  339.05  5004.3  337.56
  5025.1  337.35  5039.5  333.19  5057.3   329.9    5060   329.4  5063.3   329.9
  5232.1  331.33  5343.9  333.58  5443.4  336.91  5465.8  336.46  5572.4  341.01
#Mann= 3 ,-1 , 0
  4642.1     .05       0  5057.3     .03       0  5063.3     .05       0
Bank Sta=5057.3,5063.3
XS Rating Curve= 0 ,0
Exp/Cntr=0.3,0.1

Type RM Length L Ch R = 1 ,3924    ,300,300,300
BEGIN DESCRIPTION:
UNT061 IN SUCR 3.0
END DESCRIPTION:
XS GIS Cut Line= 3
      2294207.83     13398389.59      2294277.27     13398597.91
      2294803.92     13398888.95
#Sta/Elev= 30
  4637.4  333.09  4651.6  333.77  4676.7  332.57  4739.9  331.71  4751.7  331.15
  4760.5   331.4  4771.5  331.67  4778.1  331.03  4825.5  330.02  4834.8  330.19
  4869.9   329.1  4885.9  329.33  4929.5  328.48  4967.3  328.37  5002.1  327.29
  5004.8  326.79  5008.1  327.29  5032.6  329.08  5054.3  328.08  5076.1  328.08
  5108.2  328.81  5157.4  328.61  5188.8  329.74  5268.8  330.22  5298.3  331.13
  5314.4  331.09  5348.8  332.96  5363.6  332.64  5439.3  334.58  5458.7  335.67
#Mann= 5 ,-1 , 0
  4637.4     .05       0  4760.5      .1       0  4825.5     .05       0
  5002.1     .03       0  5008.1     .05       0
Bank Sta=5002.1,5008.1
XS Rating Curve= 0 ,0
Exp/Cntr=0.3,0.1

Type RM Length L Ch R = 1 ,3624    ,296,296,296
BEGIN DESCRIPTION:
UNT061 IN SUCR 2.0
END DESCRIPTION:
XS GIS Cut Line= 4
      2294070.01     13398668.81      2294097.79     13398821.57
      2294486.68     13399071.57        2294653.     13399127.01
#Sta/Elev= 30
  4721.3  331.54  4729.5  331.89    4760  331.12  4852.4  330.63  4900.9  329.82
  4959.7  326.45  4982.8  326.05  5016.1  323.77  5018.9  323.27  5022.1  323.77
    5031  325.39  5046.2  325.49  5067.3   324.6  5082.5  324.72  5118.8  325.94
  5126.1  326.41    5134  327.67  5155.2  327.85  5161.8  326.73  5185.5  327.35
    5249  327.56  5321.6  328.42  5342.5  328.91  5361.1  329.89  5392.7  330.08
  5437.4  332.29  5445.4   333.4    5469  333.62  5500.6   334.5  5514.2  335.31
#Mann= 3 ,-1 , 0
  4721.3     .05       0  5016.1     .03       0  5022.1     .05       0
Bank Sta=5016.1,5022.1
XS Rating Curve= 0 ,0
Exp/Cntr=0.3,0.1

Type RM Length L Ch R = 1 ,3328    ,131,131,131
BEGIN DESCRIPTION:
Mapping XS 732f8380
END DESCRIPTION:
XS GIS Cut Line= 5
      2293965.84     13398932.68      2294028.34      13399106.3
      2294090.84      13399168.8      2294201.96     13399175.74
        2294452.     13399259.09
#Sta/Elev= 30
  4752.1  329.71  4767.1  329.39  4772.4  328.77  4788.4  328.22  4833.8  326.95
  4859.2  326.83  4864.5  327.33  4889.9  327.12  4895.3  328.32  4964.9  327.37
  4971.9   326.5    4979  327.36  5000.2  327.96  5020.1  327.45  5070.5  327.44
  5075.5  326.22    5102  326.84  5112.1  326.49  5122.1  325.59  5142.4  325.41
  5156.7  323.64  5159.9  324.14  5163.5  325.43  5226.7   326.5  5237.3  326.61
  5251.8  326.59  5268.9  327.22  5278.2  327.99  5309.8  327.03  5399.9  327.99
#Mann= 3 ,-1 , 0
  4752.1     .05       0  5112.1     .03       0  5226.7     .05       0
Bank Sta=5102,5237.3
XS Rating Curve= 0 ,0
Exp/Cntr=0.3,0.1

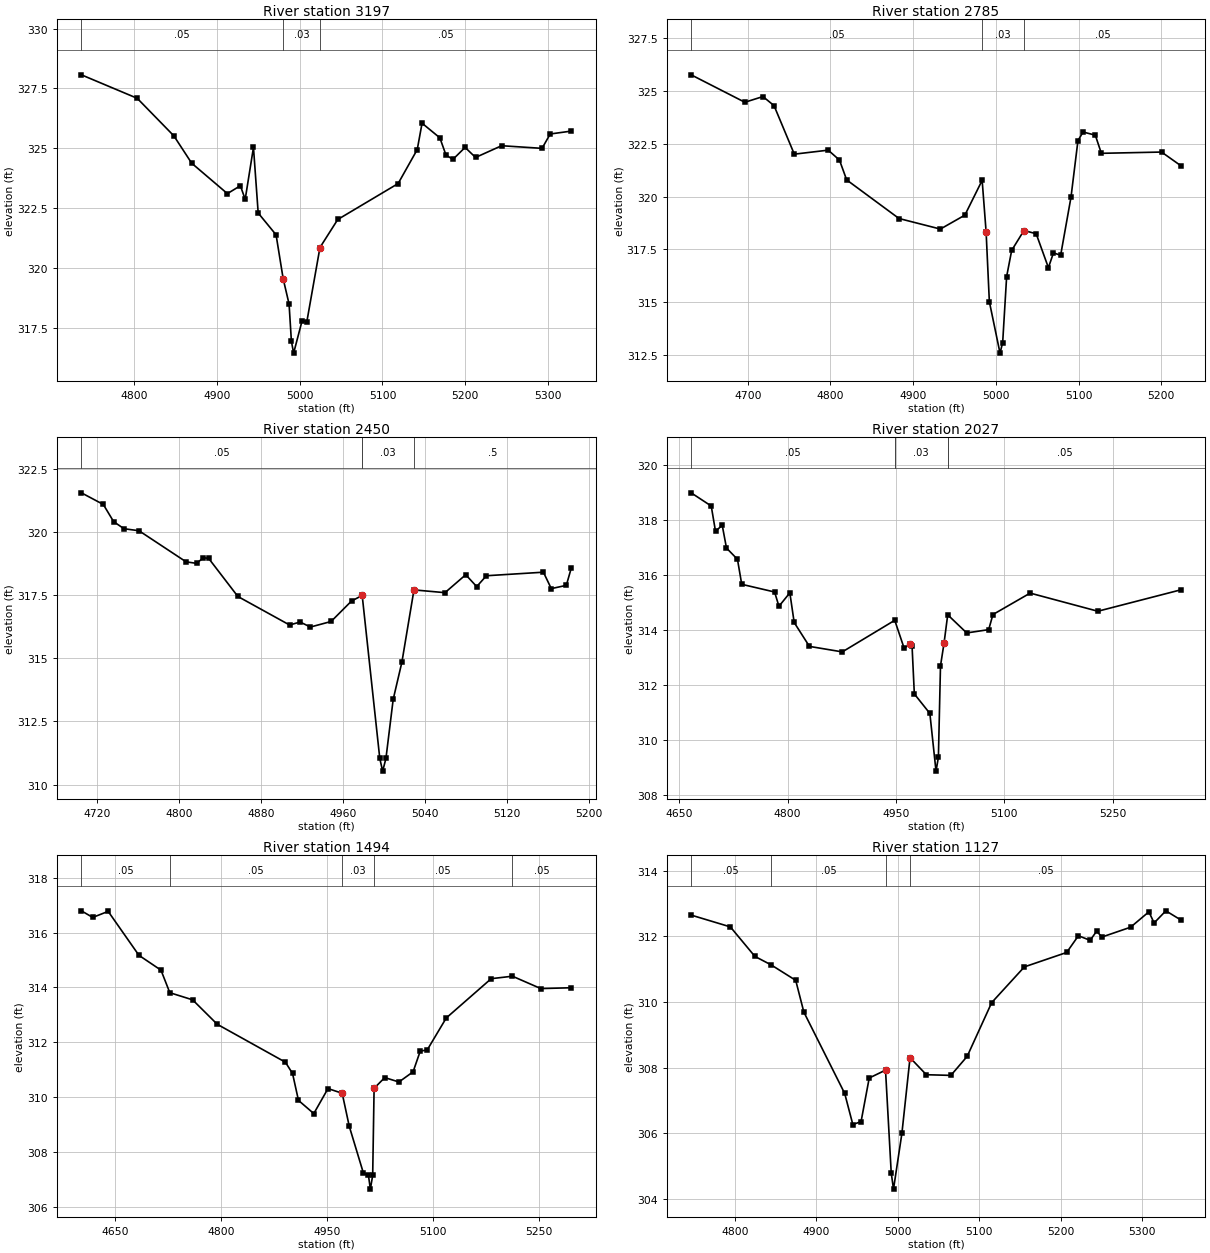
Type RM Length L Ch R = 1 ,3197    ,412,412,412
BEGIN DESCRIPTION:
Mapping XS 255340ba
END DESCRIPTION:
XS GIS Cut Line= 3
      2293840.85     13399092.42      2293868.62     13399182.68
      2294298.47     13399432.28
#Sta/Elev= 30
  4736.4  328.07  4803.8  327.09  4848.1  325.52  4869.6  324.38  4912.7  323.11
  4928.4  323.44  4934.2  322.87  4944.2  325.04  4949.9   322.3  4971.5  321.39
  4980.1  319.55  4987.2   318.5    4990  316.95  4992.7  316.45  5002.9   317.8
  5008.7  317.77  5024.5  320.86    5046  322.03  5118.9  323.53    5142  324.95
  5147.8  326.05  5169.3  325.44  5176.7  324.72  5185.1  324.54  5199.8  325.04
  5212.4  324.62  5243.9  325.11  5292.7     325  5302.6   325.6  5327.9  325.72
#Mann= 3 , 0 , 0
  4736.4     .05       0  4980.1     .03       0  5024.5     .05       0
Bank Sta=4980.1,5024.5
XS Rating Curve= 0 ,0
Exp/Cntr=0.3,0.1

Type RM Length L Ch R = 1 ,2785    ,335,335,335
BEGIN DESCRIPTION:
Mapping XS 70c8803c1
END DESCRIPTION:
XS GIS Cut Line= 3
      2293688.07       13399266.      2293639.46     13399391.02
      2293903.01     13399765.54
#Sta/Elev= 30
  4631.6  325.77  4696.5  324.47  4718.4  324.74  4731.8  324.31  4756.3  322.01
  4797.3   322.2  4810.9  321.73  4819.6  320.79  4882.9  318.96  4932.9  318.46
  4962.5  319.12  4983.4  320.77 4988.18  318.33  4992.1  315.02    5005  312.58
  5008.2  313.08    5013  316.21  5019.1  317.45  5033.9  318.39  5048.7  318.24
  5063.5  316.63  5069.6  317.33  5078.3  317.22  5090.8  319.97  5099.2  322.65
  5105.4  323.06  5120.2  322.91  5127.5  322.05  5200.3  322.11  5223.7  321.46
#Mann= 3 ,-1 , 0
  4631.6     .05       0  4983.4     .03       0  5033.9     .05       0
Bank Sta=4988.18,5033.9
XS Rating Curve= 0 ,0
Exp/Cntr=0.3,0.1

Type RM Length L Ch R = 1 ,2450    ,423,423,423
BEGIN DESCRIPTION:
Mapping XS 324daf0d
END DESCRIPTION:
XS GIS Cut Line= 3
      2293424.17     13399425.72      2293486.68     13399828.52
      2293521.39       13399891.
#Sta/Elev= 30
  4704.4  321.54  4725.8  321.08  4735.9   320.4    4746  320.12  4760.7  320.04
  4806.7  318.81  4816.9  318.75  4823.6  318.97  4828.7  318.95  4857.3  317.44
  4907.9  316.31  4918.1  316.43  4928.2  316.23  4948.4  316.45  4968.4  317.26
  4978.8  317.48    4996  311.03  4998.8  310.53    5002  311.03  5009.1  313.37
  5017.6  314.84  5029.4   317.7  5059.7  317.59    5080   318.3  5090.7  317.83
  5100.2  318.26  5155.9   318.4  5163.6  317.75  5178.3  317.88 5183.04  318.55
#Mann= 4 ,-1 , 0
  4704.4     .05       0  4978.8      .1       0  4978.8     .03       0
  5029.4      .5       0
Bank Sta=4978.8,5029.4
XS Rating Curve= 0 ,0
Exp/Cntr=0.3,0.1

Type RM Length L Ch R = 1 ,2027    ,533,533,533
BEGIN DESCRIPTION:
Mapping XS a1f5588e
END DESCRIPTION:
XS GIS Cut Line= 3
      2293278.34     13399349.35      2292986.68     13399800.74
      2293014.36     13399932.24
#Sta/Elev= 30
  4666.4     319  4694.2  318.52  4700.1   317.6  4709.4  317.82  4715.3  316.99
  4730.5  316.58  4736.4  315.67  4781.9  315.39  4787.9  314.87    4803  315.36
    4809  314.28  4830.1  313.41  4875.6  313.21  4948.2  314.36  4961.1  313.35
  4969.3  313.48 4972.14  313.43  4975.3  311.68  4996.8  310.97  5005.3  308.87
  5008.6  309.37  5011.5   312.7 5016.43  313.53  5021.5  314.56  5047.8   313.9
  5078.2  314.02  5084.1  314.57  5135.6  315.35  5229.3  314.69 5344.29  315.47
#Mann= 5 ,-1 , 0
  4666.4     .05       0  4948.2      .1       0  4948.2     .03       0
  5021.5      .1       0  5021.5     .05       0
Bank Sta=4969.3,5016.43
XS Rating Curve= 0 ,0
Exp/Cntr=0.3,0.1

Type RM Length L Ch R = 1 ,1494    ,367,367,367
BEGIN DESCRIPTION:
Mapping XS 70c8803c
END DESCRIPTION:
XS GIS Cut Line= 3
      2292986.64     13399134.09      2292757.51     13399259.07
      2292715.84     13399689.67
#Sta/Elev= 30
  4601.8  316.79  4617.8  316.55  4639.7  316.77  4683.3  315.17  4714.5  314.63
    4727  313.81  4759.3  313.55  4794.2  312.66  4890.7  311.28  4900.8  310.87
  4909.2  309.89  4930.9  309.41    4951  310.32  4971.1  310.15  4981.1  308.95
  5001.2  307.24  5008.3  307.16    5011  306.66  5014.3  307.16  5016.3  310.33
  5031.4  310.72  5051.5  310.56  5071.5  310.93  5081.6  311.68  5091.6  311.73
  5118.5  312.89  5182.1  314.32  5212.2  314.41  5252.4  313.96  5295.4  313.99
#Mann= 5 ,-1 , 0
  4601.8     .05       0    4727     .05       0  4971.1     .03       0
  5016.3     .05       0  5212.2     .05       0
Bank Sta=4971.1,5016.3
XS Rating Curve= 0 ,0
Exp/Cntr=0.3,0.1

Type RM Length L Ch R = 1 ,1127    ,441,441,441
BEGIN DESCRIPTION:
Mapping XS 2856d61b
END DESCRIPTION:
XS GIS Cut Line= 3
      2292382.51     13399168.84      2292410.29     13399592.41
      2292548.13     13399702.68
#Sta/Elev= 30
  4746.4  312.65  4794.5  312.29  4824.6  311.39  4844.6  311.13  4874.7  310.66
  4884.7  309.69  4934.8  307.21  4944.8  306.26  4954.9  306.35  4964.9  307.68
  4984.9  307.92  4991.9  304.79  4994.7  304.29    5005  305.99    5015   308.3
    5035  307.78  5065.1  307.76  5085.1  308.34  5115.2  309.98  5155.3  311.07
  5207.2  311.51  5221.6  312.02    5236  311.88    5244  312.16  5250.4  311.98
  5285.6  312.28  5308.1  312.75  5314.5  312.41  5328.9  312.78  5347.4   312.5
#Mann= 4 ,-1 , 0
  4746.4     .05       0  4844.6     .05       0  4984.9     .03       0
    5015     .05       0
Bank Sta=4984.9,5015
XS Rating Curve= 0 ,0
Exp/Cntr=0.3,0.1

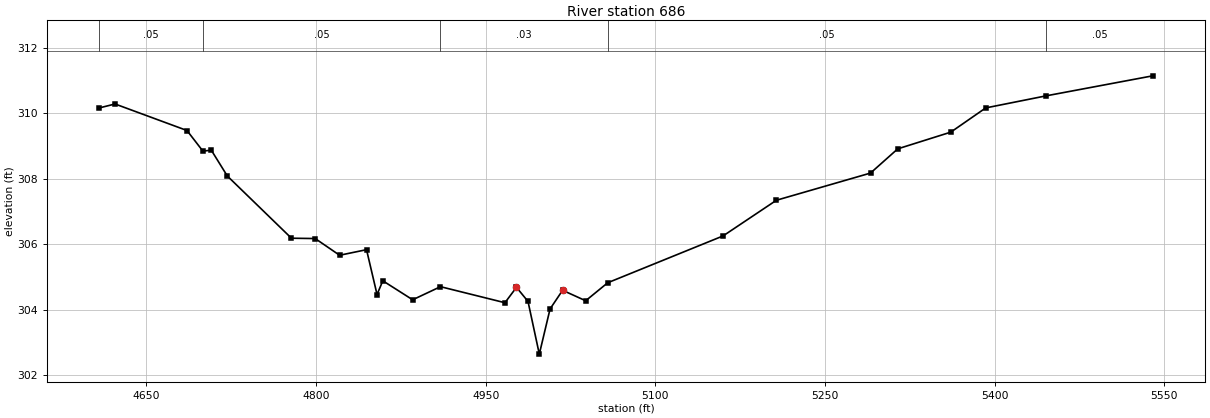
Type RM Length L Ch R = 1 ,686     ,0,0,0
BEGIN DESCRIPTION:
UNT061 IN SUCR 1.0
END DESCRIPTION:
XS GIS Cut Line= 4
      2292104.76     13399134.05      2291938.07     13399286.85
      2292007.51     13399634.07      2292333.27     13399765.76
#Sta/Elev= 30
  4608.3  310.16  4622.2  310.28  4685.8  309.47  4699.9  308.84  4707.3  308.87
  4721.5  308.08  4778.2  306.18  4799.2  306.17  4820.8  305.66  4844.6  305.83
  4853.9  304.46    4859  304.88  4885.4   304.3    4910   304.7    4967  304.21
  4977.2  304.68  4987.4  304.25  4997.4  302.64  5006.9  304.02    5018  304.59
  5038.4  304.27  5057.9  304.82  5159.9  306.25  5207.1  307.34  5290.3  308.17
  5314.4  308.91  5361.3  309.42  5392.2  310.16  5445.8  310.53  5539.9  311.14
#Mann= 5 ,-1 , 0
  4608.3     .05       0  4699.9     .05       0    4910     .03       0
  5057.9     .05       0  5445.8     .05       0
Bank Sta=4977.2,5018
XS Rating Curve= 0 ,0
Exp/Cntr=0.3,0.1

Chan Stop Cuts=-1
Use User Specified Reach Order=0
Composite Channel Slope=5