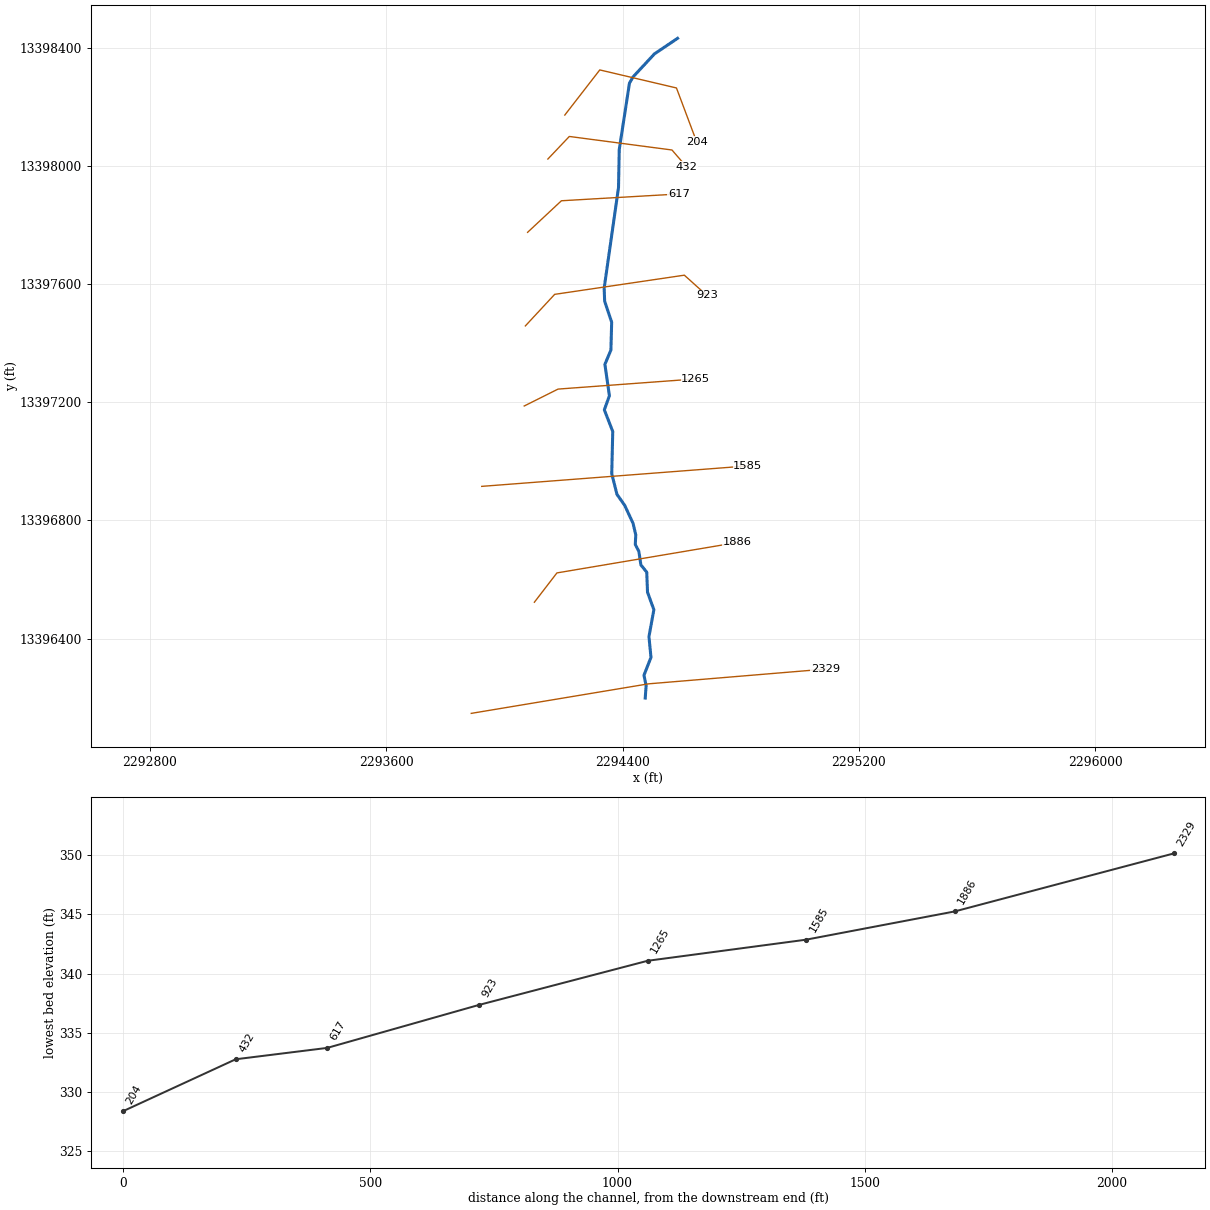
--- UNT062 IN SUCR.prj (project) ---

Proj Title=UNT062 IN SUCR Base Level Engineering
Current Plan=p01
Default Exp/Contr=0.3,0.1
English Units
Geom File=g01
Flow File=f01
Plan File=p01
BEGIN DESCRIPTION:
UNT062 IN SUCR
END DESCRIPTION:

--- UNT062 IN SUCR.p01 (plan) ---

Plan Title=Multiple Run
Short Identifier=Multiple
Geom File=g01
Flow File=f01
Subcritical Flow
K Sum by GR= 0
Std Step Tol= 0.01
Critical Tol= 0.01
Num of Std Step Trials= 20
Max Error Tol= 0.3
Flow Tol Ratio= 0.001
Split Flow NTrial= 30
Split Flow Tol= 0.02
Split Flow Ratio= 0.02
Log Output Level= 0
Friction Slope Method= 1
Unsteady Friction Slope Method= 2
Unsteady Bridges Friction Slope Method= 1
Parabolic Critical Depth
Global Vel Dist=  1 , 1 , 1
Global Log Level= 0
CheckData=True
Encroach Param= -1, 0, 0, 0
BEGIN DESCRIPTION:
Multiple Run
END DESCRIPTION:

--- UNT062 IN SUCR.f01 (steady flow) ---

Flow Title=Multiple
Number of Profiles=7
Profile Names=10-year,25-year,50-year,1pct_min,100-year,1pct_plu,500-year
River Rch & RM= UNT062 IN SUCR,Reach-1,2329
     420     588     726     658     889    1203    1337
Boundary for River Rch & Prof#=UNT062 IN SUCR,Reach-1,1
Up Type=0
Dn Type=3
Dn Slope=0.005
Boundary for River Rch & Prof#=UNT062 IN SUCR,Reach-1,2
Up Type=0
Dn Type=3
Dn Slope=0.005
Boundary for River Rch & Prof#=UNT062 IN SUCR,Reach-1,3
Up Type=0
Dn Type=3
Dn Slope=0.005
Boundary for River Rch & Prof#=UNT062 IN SUCR,Reach-1,4
Up Type=0
Dn Type=3
Dn Slope=0.005
Boundary for River Rch & Prof#=UNT062 IN SUCR,Reach-1,5
Up Type=0
Dn Type=3
Dn Slope=0.005
Boundary for River Rch & Prof#=UNT062 IN SUCR,Reach-1,6
Up Type=0
Dn Type=3
Dn Slope=0.005
Boundary for River Rch & Prof#=UNT062 IN SUCR,Reach-1,7
Up Type=0
Dn Type=3
Dn Slope=0.005

--- UNT062 IN SUCR.g01 (geometry) ---

Geom Title=Existing Conditions

River Reach=UNT062 IN SUCR,Reach-1
Reach XY= 30
      2294476.90     13396198.65      2294480.00     13396241.14
      2294472.57     13396275.85      2294496.40     13396336.50
      2294489.51     13396406.61      2294506.18     13396497.87
      2294484.66     13396557.27      2294482.08     13396624.94
      2294462.31     13396649.35      2294455.24     13396695.63
      2294443.22     13396718.66      2294444.89     13396751.41
      2294435.69     13396790.46      2294407.26     13396851.55
      2294381.23     13396888.37      2294363.55     13396958.67
      2294366.92     13397101.44      2294338.44     13397174.70
      2294355.67     13397222.55      2294340.33     13397328.72
      2294360.69     13397377.18      2294363.26     13397471.66
      2294339.49     13397542.66      2294337.86     13397586.65
      2294386.43     13397927.07      2294388.98     13398056.66
      2294423.51     13398280.90      2294435.55     13398302.01
      2294508.25     13398380.13      2294586.38     13398432.73

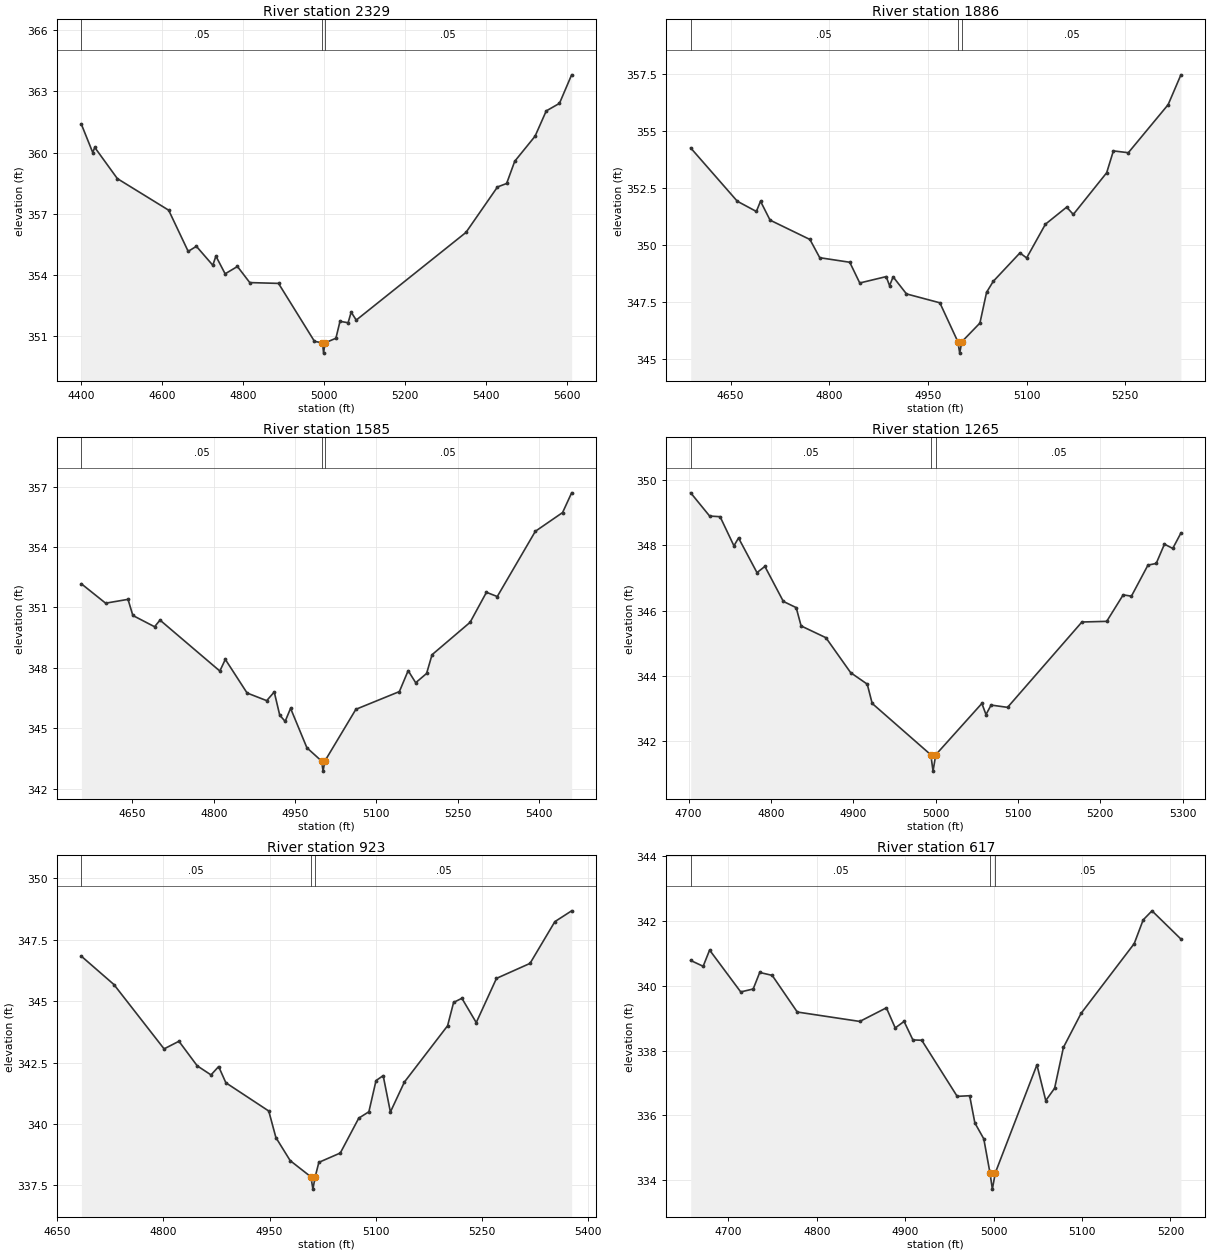
Type RM Length L Ch R = 1,2329,443,443,443
BEGIN DESCRIPTION:
UNT062 IN SUCR 5.0
END DESCRIPTION:
XS GIS Cut Line= 3
      2293887.74     13396146.86      2294487.72     13396246.85
      2295087.69     13396296.85
#Sta/Elev= 30
  4400.5  361.38  4428.4  360.00  4433.4  360.25  4489.2  358.72  4615.9  357.17
  4664.1  355.15  4684.3  355.40  4724.9  354.47  4732.5  354.92  4755.3  354.05
  4785.7  354.41  4816.1  353.62  4887.1  353.58  4975.8  350.74  4995.6  350.66
  4998.4  350.16  5001.6  350.66  5028.8  350.89  5038.9  351.72  5058.9  351.65
  5066.5  352.17  5079.0  351.78  5349.9  356.08  5427.7  358.31  5450.3  358.48
  5470.3  359.57  5520.5  360.80  5548.1  362.04  5580.7  362.41  5610.8  363.81
#Mann=3,-1,0
  4400.5    0.05       0  4995.6    0.04       0  5001.6    0.05       0
Bank Sta=4995.6,5001.6
Exp/Cntr=0.3,0.1

Type RM Length L Ch R = 1,1886,301,301,301
BEGIN DESCRIPTION:
UNT062 IN SUCR 4.0
END DESCRIPTION:
XS GIS Cut Line= 3
      2294101.52     13396523.20      2294177.89     13396622.48
      2294788.90     13396725.59
#Sta/Elev= 30
  4589.5  354.27  4660.3  351.93  4689.3  351.48  4695.6  351.93  4710.1  351.10
  4770.7  350.25  4785.6  349.45  4831.2  349.25  4846.4  348.34  4886.6  348.62
  4891.7  348.22  4897.1  348.61  4917.4  347.86  4968.1  347.47  4995.5  345.76
  4998.3  345.26  5001.5  345.76  5029.0  346.58  5039.1  347.93  5049.2  348.41
  5089.8  349.66  5100.0  349.44  5128.5  350.92  5160.8  351.67  5170.9  351.35
  5221.6  353.18  5231.8  354.14  5254.5  354.06  5315.0  356.17  5334.4  357.48
#Mann=3,-1,0
  4589.5    0.05       0  4995.5    0.03       0  5001.5    0.05       0
Bank Sta=4995.5,5001.5
Exp/Cntr=0.3,0.1

Type RM Length L Ch R = 1,1585,320,320,320
BEGIN DESCRIPTION:
Mapping XS 9e5b3839
END DESCRIPTION:
XS GIS Cut Line= 2
      2293923.24     13396915.57      2294824.38     13396984.89
#Sta/Elev= 30
  4556.1  352.17  4600.7  351.21  4642.0  351.40  4650.9  350.60  4691.0  350.04
  4701.0  350.37  4811.3  347.84  4821.4  348.42  4861.5  346.75  4897.7  346.37
  4911.6  346.80  4921.7  345.65  4931.7  345.34  4941.7  345.99  4971.8  344.03
  4998.9  343.37  5001.6  342.87  5004.9  343.37  5062.1  345.94  5142.3  346.82
  5158.5  347.86  5172.4  347.26  5192.5  347.72  5202.5  348.65  5272.7  350.26
  5302.8  351.75  5322.8  351.54  5393.0  354.78  5443.2  355.71  5459.9  356.69
#Mann=3,-1,0
  4556.1    0.05       0  4998.9    0.03       0  5004.9    0.05       0
Bank Sta=4998.9,5004.9
Exp/Cntr=0.3,0.1

Type RM Length L Ch R = 1,1265,342,342,342
BEGIN DESCRIPTION:
Mapping XS f499ee14
END DESCRIPTION:
XS GIS Cut Line= 3
      2294067.11     13397187.68      2294181.71     13397244.99
      2294647.62     13397279.36
#Sta/Elev= 30
  4702.5  349.60  4725.5  348.89  4738.2  348.87  4755.0  347.98  4760.6  348.22
  4783.0  347.16  4792.6  347.35  4815.0  346.28  4830.6  346.09  4836.6  345.53
  4866.7  345.17  4896.8  344.10  4916.9  343.75  4922.9  343.16  4994.1  341.59
  4996.8  341.09  5000.1  341.59  5056.1  343.16  5061.1  342.82  5067.3  343.11
  5087.3  343.04  5177.6  345.65  5207.7  345.67  5227.7  346.48  5237.7  346.44
  5257.8  347.39  5267.8  347.44  5277.8  348.03  5287.9  347.90  5297.8  348.37
#Mann=3,-1,0
  4702.5    0.05       0  4994.1    0.03       0  5000.1    0.05       0
Bank Sta=4994.1,5000.1
Exp/Cntr=0.3,0.1

Type RM Length L Ch R = 1,923,306,306,306
BEGIN DESCRIPTION:
UNT062 IN SUCR 3.0
END DESCRIPTION:
XS GIS Cut Line= 4
      2294070.93     13397458.82      2294170.26     13397565.78
      2294609.44     13397630.71      2294685.83     13397561.96
#Sta/Elev= 30
  4684.2  346.83  4730.1  345.68  4801.0  343.06  4822.0  343.37  4847.8  342.37
  4867.3  342.00  4878.1  342.34  4888.3  341.68  4948.9  340.53  4959.0  339.45
  4979.2  338.51  5008.5  337.85  5011.3  337.35  5014.5  337.85  5019.7  338.44
  5050.0  338.82  5076.1  340.24  5090.4  340.50  5100.5  341.77  5110.6  341.97
  5120.8  340.49  5140.6  341.71  5201.6  344.00  5210.1  344.95  5221.8  345.12
  5242.1  344.13  5270.7  345.93  5318.1  346.54  5353.2  348.24  5376.9  348.68
#Mann=3,-1,0
  4684.2    0.05       0  5008.5    0.03       0  5014.5    0.05       0
Bank Sta=5008.5,5014.5
Exp/Cntr=0.3,0.1

Type RM Length L Ch R = 1,617,185,185,185
BEGIN DESCRIPTION:
UNT062 IN SUCR 2.0
END DESCRIPTION:
XS GIS Cut Line= 3
      2294078.60     13397775.83      2294193.17     13397882.76
      2294590.40     13397905.68
#Sta/Elev= 30
  4657.3  340.78  4671.4  340.60  4678.7  341.10  4713.9  339.81  4728.0  339.90
  4735.4  340.41  4749.5  340.32  4777.9  339.19  4848.6  338.90  4878.7  339.32
  4888.7  338.70  4898.7  338.90  4908.7  338.33  4918.7  338.32  4958.8  336.59
  4972.9  336.61  4978.8  335.77  4988.9  335.28  4995.9  334.23  4998.6  333.73
  5001.9  334.23  5049.0  337.56  5059.0  336.46  5069.0  336.84  5079.0  338.10
  5099.0  339.15  5159.1  341.30  5169.2  342.03  5179.2  342.31  5211.9  341.44
#Mann=3,-1,0
  4657.3    0.05       0  4995.9    0.03       0  5001.9    0.05       0
Bank Sta=4995.9,5001.9
Exp/Cntr=0.3,0.1

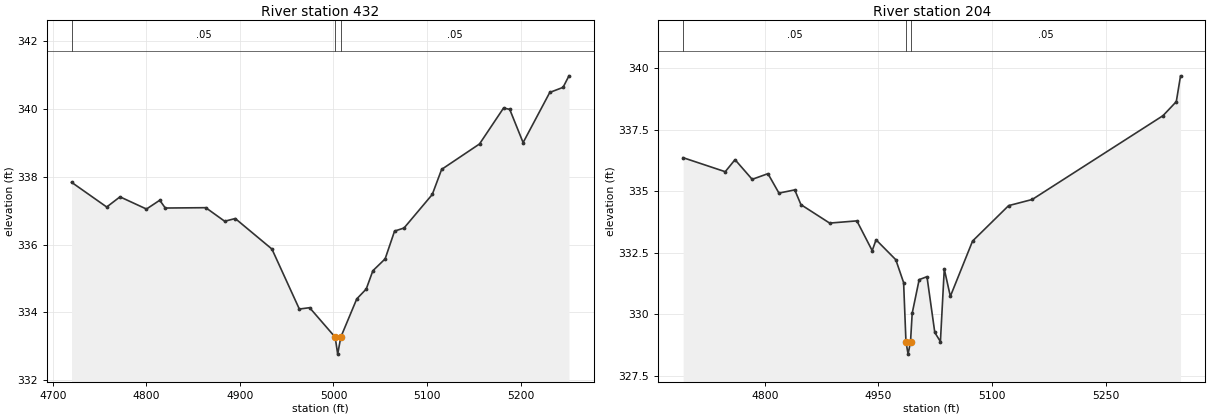
Type RM Length L Ch R = 1,432,228,228,228
BEGIN DESCRIPTION:
Mapping XS 19615ddd
END DESCRIPTION:
XS GIS Cut Line= 4
      2294147.31     13398024.03      2294219.90     13398100.45
      2294567.44     13398054.62      2294617.05     13397997.37
#Sta/Elev= 30
  4720.0  337.84  4757.6  337.11  4771.8  337.41  4800.1  337.05  4814.3  337.31
  4820.2  337.08  4863.5  337.09  4883.7  336.69  4895.0  336.77  4934.2  335.87
  4963.5  334.10  4974.5  334.14  5001.8  333.27  5004.5  332.77  5007.8  333.27
  5024.9  334.40  5035.0  334.69  5042.1  335.23  5055.2  335.58  5065.3  336.40
  5075.4  336.49  5105.6  337.48  5115.6  338.22  5156.1  338.97  5181.8  340.03
  5188.4  339.99  5202.7  339.01  5231.2  340.49  5245.4  340.64  5251.7  340.98
#Mann=3,-1,0
  4720.0    0.05       0  5001.8    0.03       0  5007.8    0.05       0
Bank Sta=5001.8,5007.8
Exp/Cntr=0.3,0.1

Type RM Length L Ch R = 1,204,0,0,0
BEGIN DESCRIPTION:
UNT062 IN SUCR 1.0
END DESCRIPTION:
XS GIS Cut Line= 4
      2294204.61     13398172.98      2294323.02     13398325.77
      2294582.71     13398264.67      2294651.36     13398081.60
#Sta/Elev= 30
  4692.5  336.37  4748.0  335.80  4760.9  336.29  4783.5  335.49  4804.3  335.72
  4818.8  334.93  4839.6  335.06  4847.8  334.46  4885.6  333.71  4921.5  333.80
  4941.7  332.59  4946.8  333.03  4972.8  332.22  4983.1  331.29  4986.2  328.88
  4989.0  328.38  4992.2  328.88  4994.4  330.04  5003.6  331.41  5013.9  331.53
  5024.2  329.26  5031.6  328.89  5036.7  331.84  5044.7  330.73  5074.0  332.98
  5121.5  334.42  5152.6  334.67  5325.0  338.08  5342.5  338.65  5348.1  339.70
#Mann=3,-1,0
  4692.5    0.05       0  4986.2    0.03       0  4992.2    0.05       0
Bank Sta=4986.2,4992.2
Exp/Cntr=0.3,0.1

Chan Stop Cuts=-1