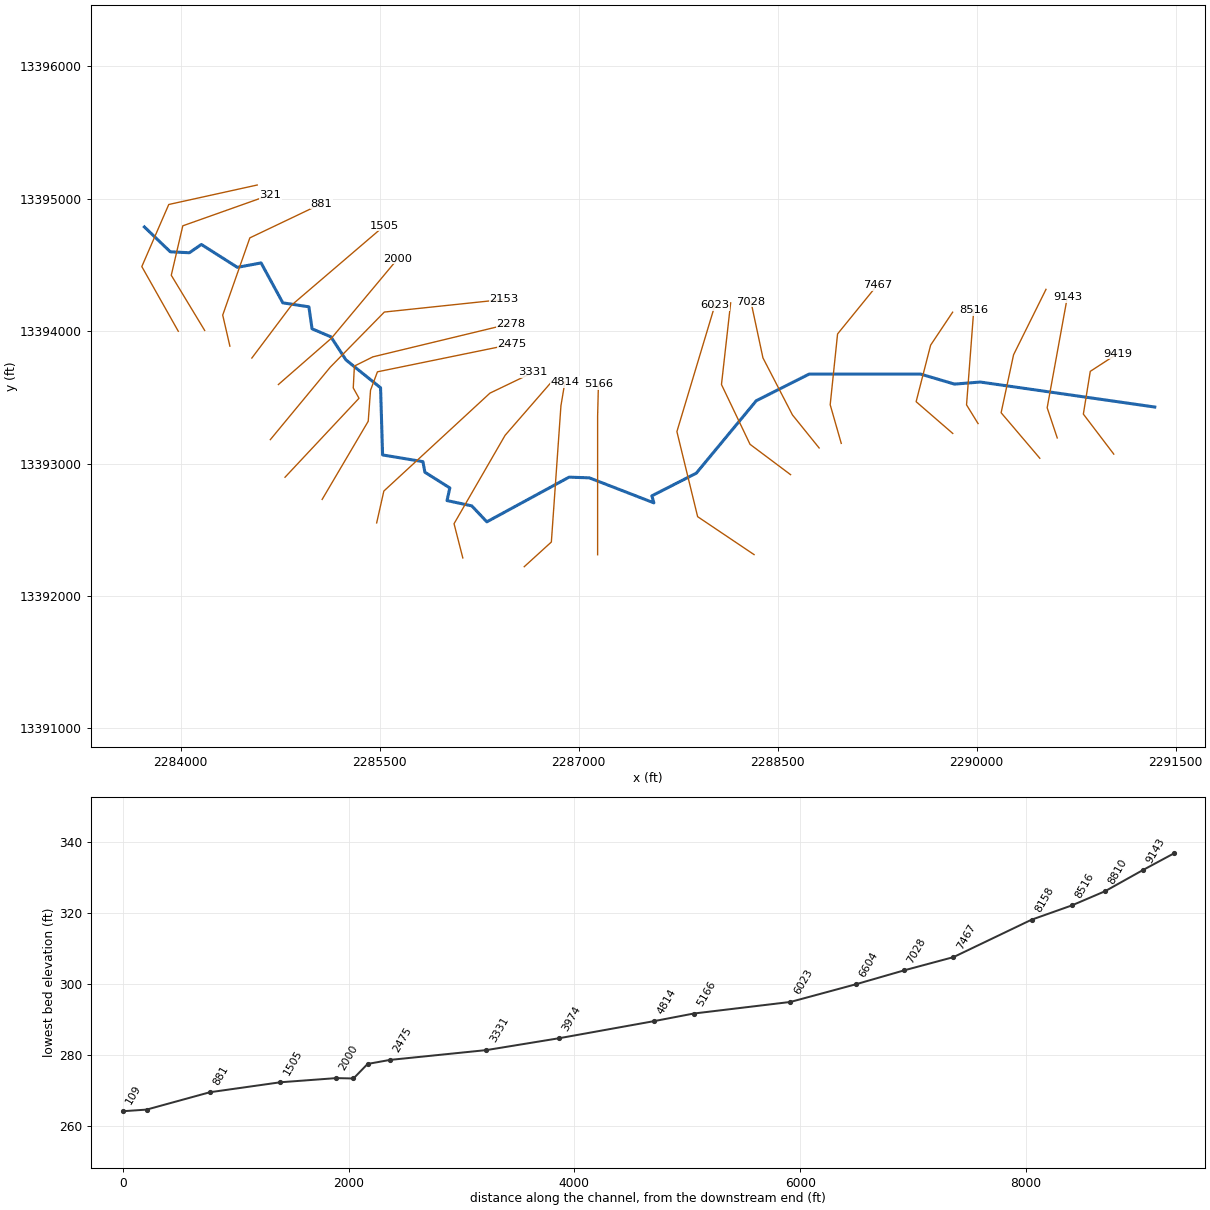
--- UNT063 IN SUCR.prj (project) ---

Proj Title=UNT063 IN SUCR Base Level Engineering
Current Plan=p01
Default Exp/Contr=0.3,0.1
English Units
Geom File=g01
Flow File=f01
Plan File=p01
Y Axis Title=Elevation
X Axis Title(PF)=Main Channel Distance
X Axis Title(XS)=Station
BEGIN DESCRIPTION:
UNT063 IN SUCR
END DESCRIPTION:
DSS Export Rating Curves= 0
DSS Export Rating Curve Sorted= 0
DSS Export Volume Flow Curves= 0
DXF OffsetX= 0
DXF OffsetY= 0
DXF ScaleX= 1
DXF ScaleY= 10

--- UNT063 IN SUCR.p01 (plan) ---

Plan Title=Multiple Run
Short Identifier=Multiple
Geom File=g01
Flow File=f01
Subcritical Flow
K Sum by GR= 0
Std Step Tol= 0.01
Critical Tol= 0.01
Num of Std Step Trials= 20
Max Error Tol= 0.3
Flow Tol Ratio= 0.001
Split Flow NTrial= 30
Split Flow Tol= 0.02
Split Flow Ratio= 0.02
Log Output Level= 0
Friction Slope Method= 1
Unsteady Friction Slope Method= 2
Unsteady Bridges Friction Slope Method= 1
Parabolic Critical Depth
Global Vel Dist=  1 , 1 , 1
Global Log Level= 0
CheckData=True
Encroach Param= -1, 0, 0, 0
BEGIN DESCRIPTION:
Multiple Run
END DESCRIPTION:

--- UNT063 IN SUCR.f01 (steady flow) ---

Flow Title=Multiple
Program Version=4.10
Number of Profiles= 7
Profile Names=10-year,25-year,50-year,1pct_min,100-year,1pct_plu,500-year
River Rch & RM=UNT063 IN SUCR,Reach-1         ,9419
     260     355     432     386     523     707     765
River Rch & RM=UNT063 IN SUCR,Reach-1         ,7467
     497     710     890     819    1107    1497    1720
River Rch & RM=UNT063 IN SUCR,Reach-1         ,5166
     623     905    1150    1070    1447    1957    2311
River Rch & RM=UNT063 IN SUCR,Reach-1         ,4814
     590     853    1080    1002    1355    1833    2154
Boundary for River Rch & Prof#=UNT063 IN SUCR,Reach-1         , 1
Up Type= 0
Dn Type= 3
Dn Slope=0.0017
Boundary for River Rch & Prof#=UNT063 IN SUCR,Reach-1         , 2
Up Type= 0
Dn Type= 3
Dn Slope=0.0017
Boundary for River Rch & Prof#=UNT063 IN SUCR,Reach-1         , 3
Up Type= 0
Dn Type= 3
Dn Slope=0.0017
Boundary for River Rch & Prof#=UNT063 IN SUCR,Reach-1         , 4
Up Type= 0
Dn Type= 3
Dn Slope=0.0017
Boundary for River Rch & Prof#=UNT063 IN SUCR,Reach-1         , 5
Up Type= 0
Dn Type= 3
Dn Slope=0.0017
Boundary for River Rch & Prof#=UNT063 IN SUCR,Reach-1         , 6
Up Type= 0
Dn Type= 3
Dn Slope=0.0017
Boundary for River Rch & Prof#=UNT063 IN SUCR,Reach-1         , 7
Up Type= 0
Dn Type= 3
Dn Slope=0.0017
DSS Import GetInterval= 0
DSS Import GetPeak= 0
DSS Import FillOption= 0

--- UNT063 IN SUCR.g01 (geometry) ---

Geom Title=Existing Conditions
Program Version=4.10

River Reach=UNT063 IN SUCR  ,Reach-1
Reach XY= 30
      2291342.72     13393426.86      2290027.57     13393615.69
      2289833.39     13393600.05       2289577.2     13393675.84
      2288738.19     13393675.74      2288339.44     13393474.61
      2287887.37      13392927.5      2287552.56     13392756.31
      2287567.65     13392703.31      2287081.32      13392892.2
      2286928.54     13392897.41      2286308.77     13392560.07
      2286194.94     13392680.62      2286008.63     13392720.62
      2286029.85     13392816.06      2285841.73     13392934.76
      2285827.21     13393014.52      2285523.19     13393065.07
      2285507.73     13393572.36      2285246.47     13393783.26
      2285133.62     13393956.87      2284991.47     13394017.63
       2284967.6     13394183.65      2284771.15     13394213.65
      2284607.34      13394515.1      2284428.67     13394481.58
      2284157.21     13394654.57      2284066.76      13394591.9
      2283923.18     13394599.12      2283727.72     13394786.85

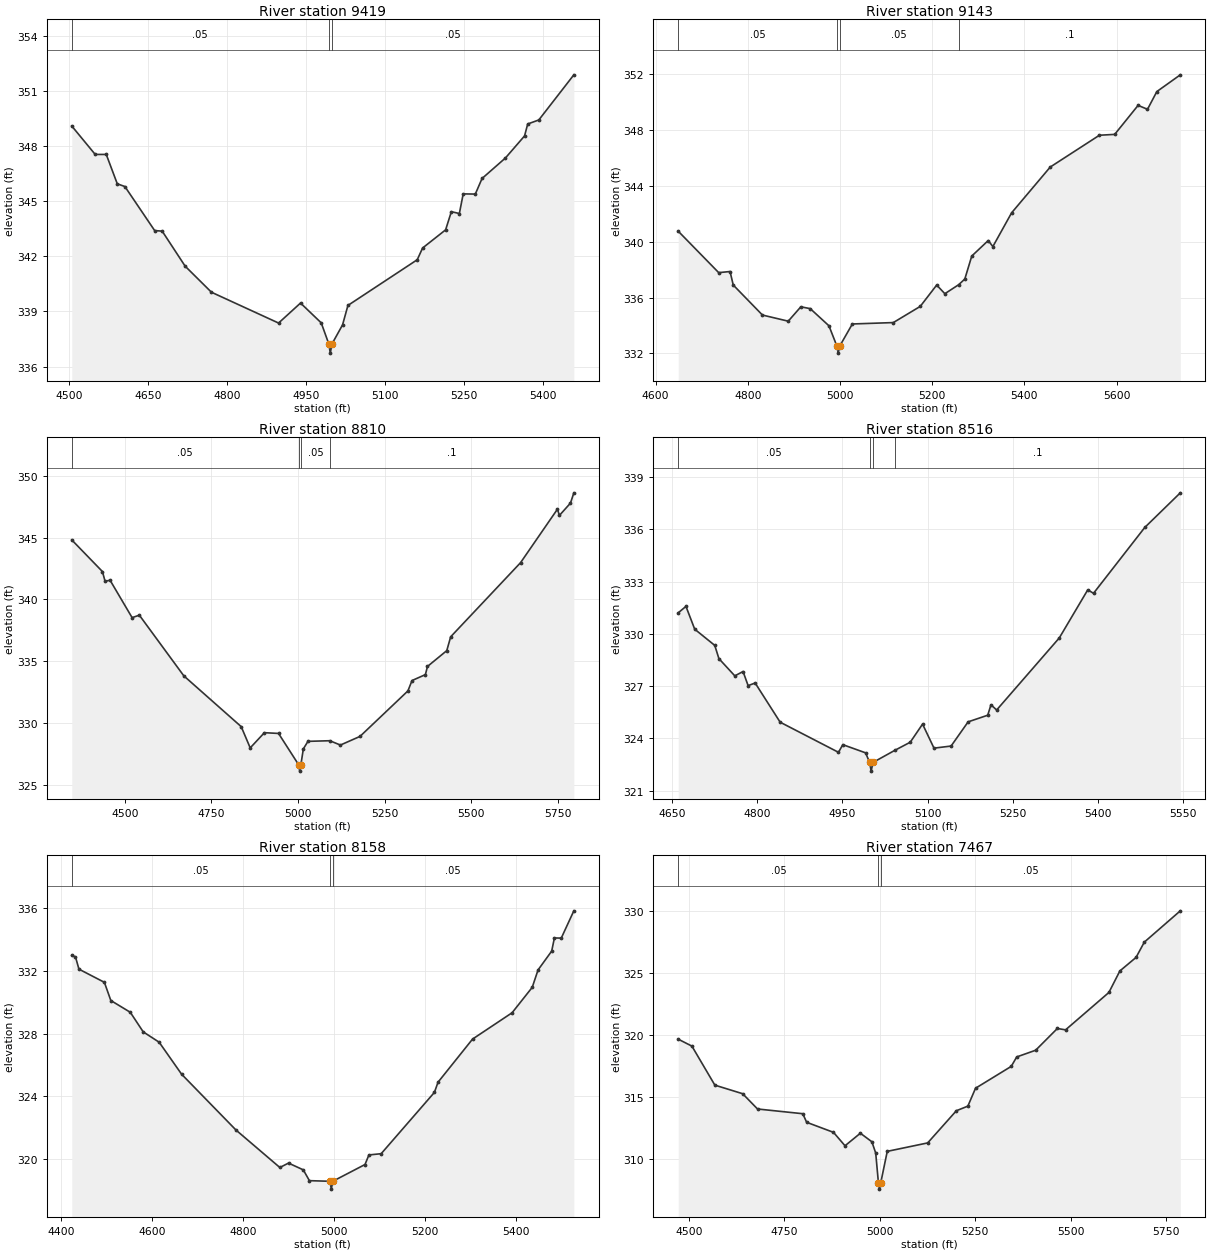
Type RM Length L Ch R = 1 ,9419    ,276,276,276
BEGIN DESCRIPTION:
UNT063 IN SUCR 15.0
END DESCRIPTION:
XS GIS Cut Line= 4
      2291033.67     13393071.42      2290804.53     13393373.47
      2290856.62     13393696.38      2291063.87      13393831.1
#Sta/Elev= 30
  4504.9  349.11  4549.4  347.56  4570.4  347.56  4591.3  345.96  4605.8  345.81
  4662.3  343.41  4676.6  343.38  4720.2  341.47  4770.1  340.05  4897.6  338.37
  4939.3  339.46  4978.6  338.38    4993  337.23  4995.8  336.73    4999  337.23
  5019.1  338.27  5029.3  339.33  5160.9  341.82  5171.1  342.46  5214.8  343.45
  5225.7  344.44  5240.9  344.34  5248.2  345.41  5271.2   345.4    5284  346.25
  5328.5  347.37  5364.7  348.57  5370.7  349.22  5391.8  349.44  5458.3   351.9
#Mann= 3 ,-1 , 0
  4504.9     .05       0    4993     .03       0    4999     .05       0
Bank Sta=4993,4999
XS Rating Curve= 0 ,0
Exp/Cntr=0.3,0.1

Type RM Length L Ch R = 1 ,9143    ,333,333,333
BEGIN DESCRIPTION:
Mapping XS 35f556bd
END DESCRIPTION:
XS GIS Cut Line= 3
      2290607.72     13393193.57      2290531.77     13393421.44
      2290683.68     13394256.95
#Sta/Elev= 30
    4649  340.76  4736.8  337.79  4761.4  337.87  4768.4   336.9  4831.7  334.75
  4887.7  334.31    4915  335.34  4935.4  335.21    4976  333.98  4993.3  332.52
  4996.1  332.02  4999.3  332.52  5026.8  334.11  5115.7  334.21  5174.1  335.37
  5209.8   336.9  5227.5  336.28  5257.3  336.92  5270.8  337.33  5285.9  338.98
  5321.6  340.09  5331.7  339.66  5372.4  342.08  5456.2  345.36  5562.9  347.64
    5596   347.7  5646.8  349.78  5667.2   349.5  5687.5  350.77  5738.4  351.97
#Mann= 4 ,-1 , 0
    4649     .05       0  4993.3     .03       0  4999.3     .05       0
  5257.3      .1       0
Bank Sta=4993.3,4999.3
XS Rating Curve= 0 ,0
Exp/Cntr=0.3,0.1

Type RM Length L Ch R = 1 ,8810    ,294,294,294
BEGIN DESCRIPTION:
Mapping XS c7c888f4
END DESCRIPTION:
XS GIS Cut Line= 4
      2290476.39     13393040.15      2290184.74     13393383.88
      2290278.49     13393821.38      2290522.99     13394315.59
#Sta/Elev= 30
  4346.6  344.82  4435.1  342.26  4442.8  341.47  4457.1  341.56  4520.8  338.53
  4541.7  338.73  4670.1  333.82  4835.8  329.71  4861.8  327.99  4902.7  329.22
  4943.6  329.16    5002  326.61  5004.7  326.11    5008  326.61  5015.2  327.91
  5028.5  328.52  5091.6  328.57  5122.2  328.22  5178.8  328.92  5317.1   332.6
    5329  333.44  5367.6  333.92  5373.6  334.58  5429.3  335.86  5440.6  336.98
  5642.4  342.98  5748.9  347.31  5754.5   346.8  5786.5   347.8  5796.2  348.63
#Mann= 4 ,-1 , 0
  4346.6     .05       0    5002     .03       0    5008     .05       0
  5091.6      .1       0
Bank Sta=5002,5008
XS Rating Curve= 0 ,0
Exp/Cntr=0.3,0.1

Type RM Length L Ch R = 1 ,8516    ,358,358,358
BEGIN DESCRIPTION:
Mapping XS 5a83ca25
END DESCRIPTION:
XS GIS Cut Line= 3
      2290010.94     13393302.07      2289924.13     13393443.14
      2289978.38     13394159.25
#Sta/Elev= 30
    4661  331.21  4674.6  331.58    4690  330.27  4725.3  329.34  4732.6  328.58
  4760.6  327.59  4775.1  327.84    4784  327.03  4796.4  327.18  4840.4  324.93
  4943.1   323.2  4950.7  323.64  4990.8  323.17  4997.9  322.62  5000.6  322.12
  5003.9  322.62  5042.6  323.32  5069.4  323.78  5091.1  324.82  5111.2  323.44
  5141.3  323.56  5171.3  324.95  5205.8  325.33  5211.5  325.93  5221.5  325.63
  5331.8  329.77  5381.9  332.53    5392  332.33  5482.2  336.11  5544.8   338.1
#Mann= 4 ,-1 , 0
    4661     .05       0  4997.9     .03       0  5003.9     .05       0
  5042.6      .1       0
Bank Sta=4997.9,5003.9
XS Rating Curve= 0 ,0
Exp/Cntr=0.3,0.1

Type RM Length L Ch R = 1 ,8158    ,691,691,691
BEGIN DESCRIPTION:
Mapping XS 70fb73ed
END DESCRIPTION:
XS GIS Cut Line= 4
      2289820.18     13393227.61      2289544.12     13393467.22
      2289653.49      13393894.3      2289819.34     13394143.07
#Sta/Elev= 30
  4422.8     333    4431   332.9  4438.6  332.12  4494.6  331.28  4508.8  330.12
  4551.6  329.37  4580.1  328.12  4615.2  327.46  4664.6  325.42  4784.3  321.86
  4880.9  319.47    4900  319.75  4932.5  319.32    4946  318.63  4991.4  318.59
  4994.2  318.09  4997.4  318.59  5068.4  319.66    5077  320.27    5104  320.35
  5221.2  324.26  5229.2  324.91  5305.2  327.66  5392.3  329.34  5436.6  330.96
  5449.4  332.07  5479.4  333.27  5485.4  334.11  5500.5   334.1  5528.2  335.84
#Mann= 3 ,-1 , 0
  4422.8     .05       0  4991.4     .03       0  4997.4     .05       0
Bank Sta=4991.4,4997.4
XS Rating Curve= 0 ,0
Exp/Cntr=0.3,0.1

Type RM Length L Ch R = 1 ,7467    ,439,439,439
BEGIN DESCRIPTION:
UNT063 IN SUCR 14.0
END DESCRIPTION:
XS GIS Cut Line= 4
      2288979.85     13393152.44      2288896.52     13393444.09
      2288952.08     13393978.81       2289250.7     13394346.89
#Sta/Elev= 30
  4472.6  319.65  4508.4  319.09  4568.5  315.95  4641.3  315.26  4680.3  314.03
  4798.8  313.65  4808.9  312.96  4879.2  312.15  4909.4  311.07  4949.6  312.08
  4979.8  311.39  4989.8  310.48  4996.9  308.08  4999.6  307.58  5002.9  308.08
    5020  310.62  5125.9   311.3    5201  313.89  5231.1  314.26  5251.2   315.7
  5344.7  317.46  5359.1  318.22  5408.7  318.76  5465.5  320.51    5487   320.4
  5600.5  323.41  5629.2  325.14  5671.6  326.23  5693.2  327.46  5787.5  329.98
#Mann= 3 ,-1 , 0
  4472.6     .05       0  4996.9    .035       0  5002.9     .05       0
Bank Sta=4996.9,5002.9
XS Rating Curve= 0 ,0
Exp/Cntr=0.3,0.1

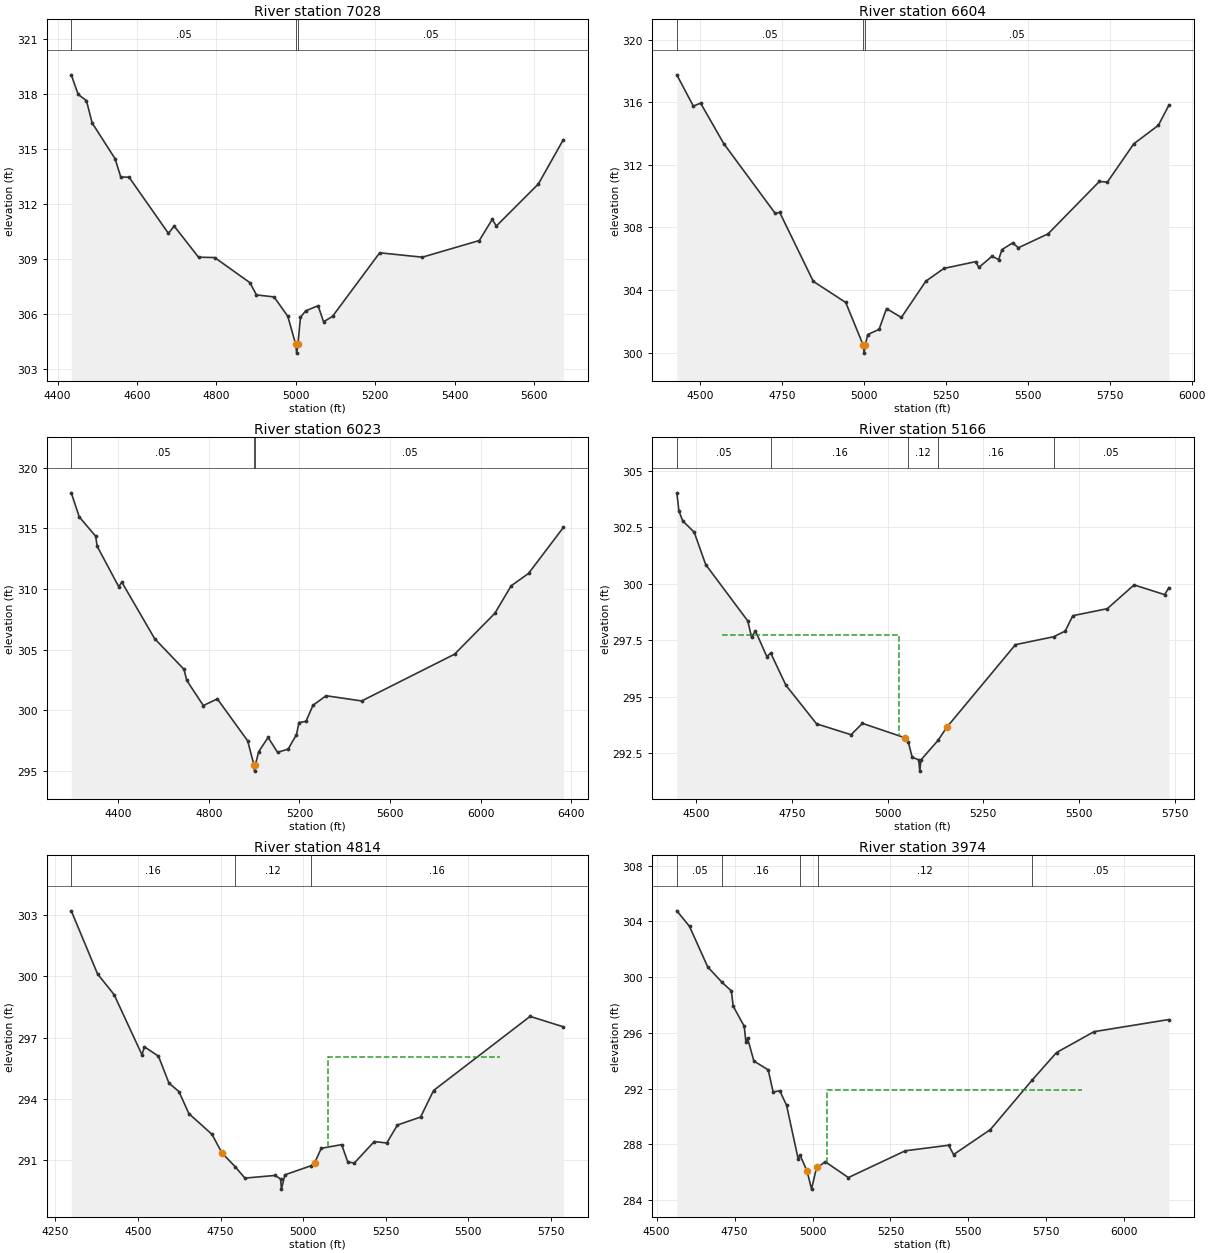
Type RM Length L Ch R = 1 ,7028    ,424,424,424
BEGIN DESCRIPTION:
UNT063 IN SUCR 13.0
END DESCRIPTION:
XS GIS Cut Line= 4
      2288813.17     13393117.72       2288611.8      13393367.7
      2288389.58     13393798.26      2288299.31     13394221.82
#Sta/Elev= 30
  4434.6  319.04    4452  317.97  4472.8  317.63  4487.2  316.41  4544.8  314.46
  4559.2  313.46    4580  313.45  4679.2  310.38  4693.6  310.78  4754.9  309.08
  4795.6  309.06  4884.2  307.69  4900.8  307.02  4945.1  306.91  4979.7  305.85
  4999.2  304.34    5002  303.84  5005.2  304.34  5011.5   305.8  5024.7  306.15
  5055.9  306.43  5069.7  305.55  5092.3  305.85  5210.9  309.32  5318.2  309.08
  5461.7  309.99  5494.3  311.15  5504.5  310.78  5610.4  313.08  5673.2   315.5
#Mann= 3 ,-1 , 0
  4434.6     .05       0  4999.2    .035       0  5005.2     .05       0
Bank Sta=4999.2,5005.2
XS Rating Curve= 0 ,0
Exp/Cntr=0.3,0.1

Type RM Length L Ch R = 1 ,6604    ,581,581,581
BEGIN DESCRIPTION:
UNT063 IN SUCR 12.0
END DESCRIPTION:
XS GIS Cut Line= 4
      2288597.92      13392916.3      2288292.35     13393145.48
      2288077.08     13393596.87      2288146.35     13394213.43
#Sta/Elev= 30
    4428  317.76  4478.3  315.76  4500.5  315.95  4571.3  313.36  4728.3   308.9
  4742.1  308.96  4844.7  304.55  4943.7   303.2  4997.2  300.46  4999.9  299.96
  5003.2  300.46  5010.9  301.15  5045.5  301.48  5068.2  302.81  5113.6  302.24
  5188.2  304.56  5243.6  305.38  5340.2  305.81  5350.3  305.44  5390.5  306.16
  5410.7  305.94  5420.7  306.58  5453.1  307.01    5471   306.7  5561.6  307.59
  5718.2  310.94  5742.7   310.9  5823.3  313.35  5898.3  314.53  5930.5  315.82
#Mann= 3 ,-1 , 0
    4428     .05       0  4997.2    .035       0  5003.2     .05       0
Bank Sta=4997.2,5003.2
XS Rating Curve= 0 ,0
Exp/Cntr=0.3,0.1

Type RM Length L Ch R = 1 ,6023    ,857,857,857
BEGIN DESCRIPTION:
UNT063 IN SUCR 11.0
END DESCRIPTION:
XS GIS Cut Line= 4
      2288322.78     13392312.58      2287897.42     13392599.05
      2287741.17     13393241.41      2288027.61     13394196.24
#Sta/Elev= 30
  4193.6  317.94    4229  315.95  4300.9  314.37  4308.2  313.52  4402.9   310.2
  4416.7  310.57  4561.4  305.91  4690.8  303.38  4703.2  302.46  4776.2  300.39
    4838  300.94  4971.8  297.48  4999.6  295.48  5002.4  294.98  5005.6  295.48
  5020.3  296.58    5062  297.76  5103.7  296.53  5150.6   296.8  5187.2     298
  5198.2  298.99    5229  299.08  5259.9  300.41  5317.6   301.2  5474.9  300.77
  5884.8  304.63  6062.3     308  6134.3  310.27  6210.9  311.29  6364.4  315.08
#Mann= 3 ,-1 , 0
  4193.6     .05       0  4999.6    .035       0  5005.6     .05       0
Bank Sta=4999.6,5005.6
XS Rating Curve= 0 ,0
Exp/Cntr=0.3,0.1

Type RM Length L Ch R = 1 ,5166    ,352,352,352
BEGIN DESCRIPTION:
UNT063 IN SUCR 10.0
END DESCRIPTION:
XS GIS Cut Line= 3
      2287143.68     13392311.41      2287143.68      13393357.5
      2287149.69     13393597.94
#Sta/Elev= 30
  4448.7  304.02  4454.1  303.22  4464.1  302.78  4494.1  302.28  4524.1  300.85
  4634.1  298.36  4644.1  297.64  4654.1  297.92  4684.1  296.78  4694.1  296.94
  4734.1  295.51  4814.1  293.81  4904.1  293.33  4934.1  293.83  5044.1   293.2
  5054.1  292.99  5064.1  292.33  5081.1  292.22  5083.9  291.72  5087.1  292.22
  5131.7  293.08  5154.1  293.65  5334.1  297.31  5434.1  297.66  5464.1  297.91
  5484.1  298.59  5574.2   298.9  5644.2  299.95  5724.2  299.52  5735.3  299.83
#Mann= 5 ,-1 , 0
  4448.7     .05       0  4694.1     .16       0  5054.1     .12       0
  5131.7     .16       0  5434.1     .05       0
#XS Ineff= 1 ,-1
 4567.84 5028.41 297.729
Permanent Ineff=
       T
Bank Sta=5044.1,5154.1
XS Rating Curve= 0 ,0
Exp/Cntr=0.3,0.1

Type RM Length L Ch R = 1 ,4814    ,840,840,840
BEGIN DESCRIPTION:
UNT063 IN SUCR 9.0
END DESCRIPTION:
XS GIS Cut Line= 4
      2286590.56     13392221.22      2286794.99     13392407.62
      2286867.14     13393435.66       2286897.2     13393616.05
#Sta/Elev= 30
  4297.8  303.21  4377.4  300.12  4427.4  299.11  4511.9  296.16  4519.3  296.55
  4561.9  296.09  4593.7  294.77  4623.8  294.36  4653.9  293.28  4724.1  292.26
  4754.1  291.35  4794.2  290.68  4823.5  290.12  4914.5  290.25  4931.6  290.08
  4934.3  289.58  4944.6  290.28  5024.8  290.73  5034.8  290.87  5054.9  291.58
  5116.7  291.76  5135.1  290.91  5155.1  290.86  5215.3  291.91  5253.3  291.84
  5285.4  292.72  5355.6  293.11  5394.9  294.41  5687.3  298.04  5787.9  297.53
#Mann= 3 ,-1 , 0
  4297.8     .16       0  4794.2     .12       0  5024.8     .16       0
#XS Ineff= 1 ,-1
 5074.55 5595.45296.0511
Permanent Ineff=
       T
Bank Sta=4754.1,5034.8
XS Rating Curve= 0 ,0
Exp/Cntr=0.3,0.1

Type RM Length L Ch R = 1 ,3974    ,643,643,643
BEGIN DESCRIPTION:
UNT063 IN SUCR 8.0
END DESCRIPTION:
XS GIS Cut Line= 4
      2286127.66     13392287.43      2286061.54      13392545.9
       2286446.3     13393213.22      2286800.92     13393621.93
#Sta/Elev= 30
  4564.8  304.75  4605.5  303.63  4663.9  300.72  4709.8  299.62  4739.7     299
  4745.5  297.91    4781  296.46  4786.3  295.34  4791.5  295.62  4811.9  293.97
  4857.8  293.34  4873.5  291.76  4895.1  291.83  4916.7   290.8    4954  286.94
  4959.8  287.23  4982.8  286.05  4996.8  284.78  5012.9  286.34  5018.7  286.37
  5040.5  286.75  5114.9  285.61  5297.3  287.53  5436.6  287.93  5452.4  287.26
  5570.2  289.05  5704.6  292.61  5782.5  294.58  5903.1  296.08    6143  296.95
#Mann= 5 ,-1 , 0
  4564.8     .05       0  4709.8     .16       0  4959.8     .12       0
  5018.7     .12       0  5704.6     .05       0
#XS Ineff= 1 ,-1
 5046.36 5865.57 291.862
Permanent Ineff=
       T
Bank Sta=4982.8,5012.9
XS Rating Curve= 0 ,0
Exp/Cntr=0.3,0.1

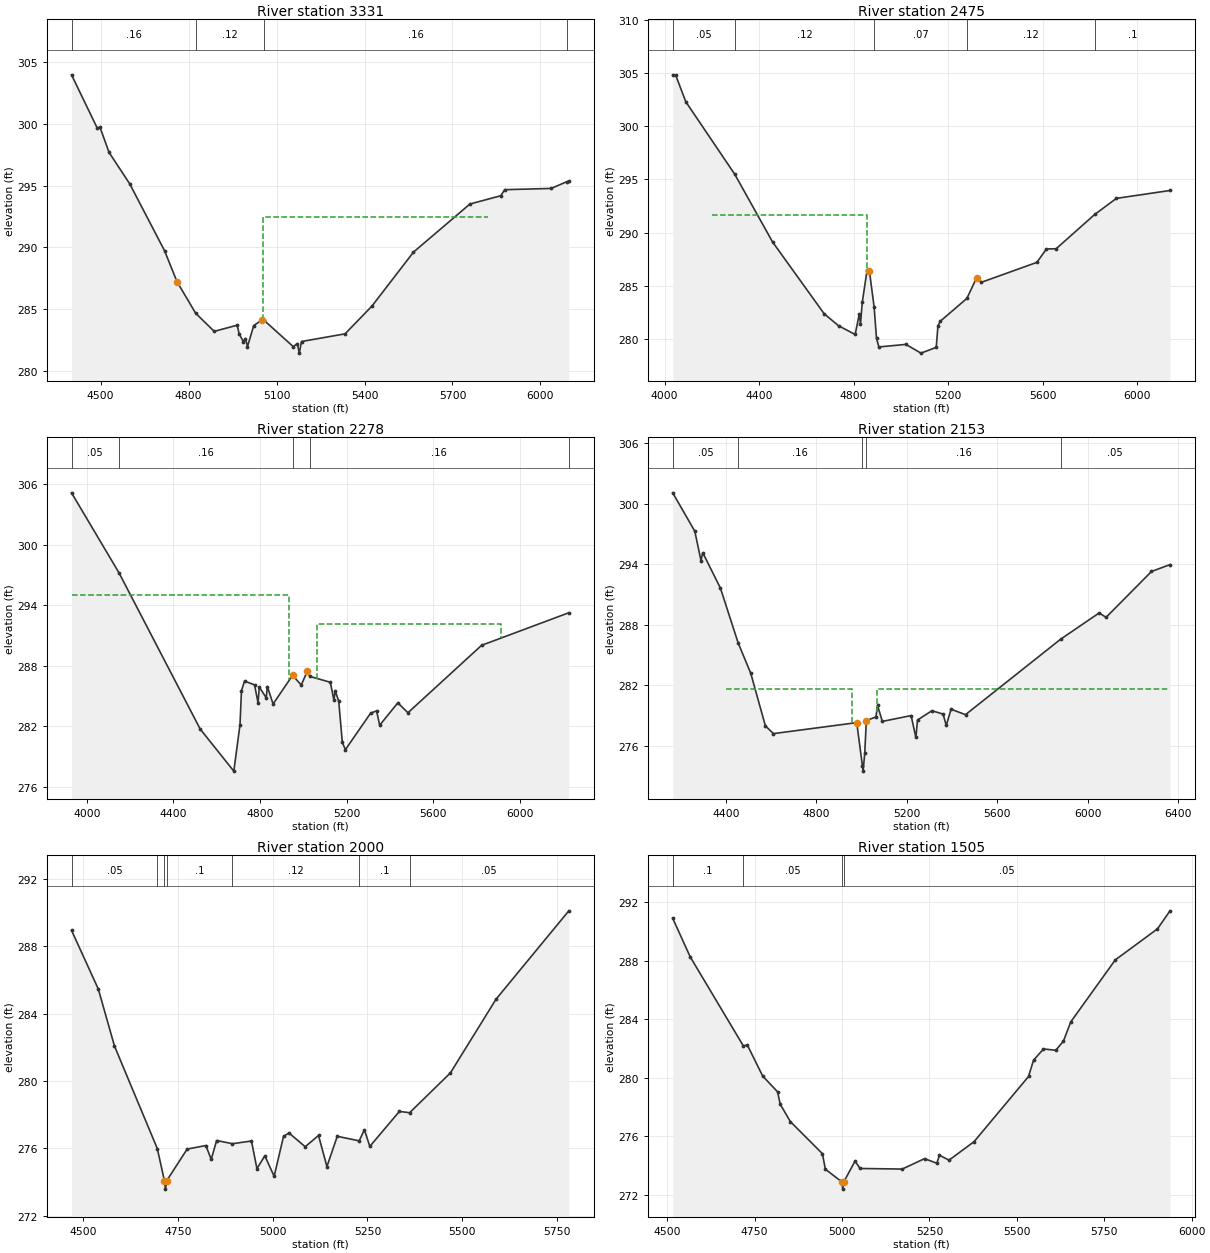
Type RM Length L Ch R = 1 ,3331    ,856,856,856
BEGIN DESCRIPTION:
UNT063 IN SUCR 7.0
END DESCRIPTION:
XS GIS Cut Line= 4
      2285478.39     13392551.91      2285532.49     13392792.38
      2286332.08     13393531.85      2286656.72     13393688.16
#Sta/Elev= 30
  4400.8  303.96  4487.9  299.68  4498.1   299.7  4528.9  297.68  4599.1  295.15
  4717.9  289.74  4760.5  287.23    4824  284.68  4887.5  283.21  4965.7  283.71
  4972.5     283  4986.7  282.39  4994.1  282.63  5000.9  281.98  5022.2  283.68
  5050.2  284.13  5057.6   284.1  5156.8  281.98    5171  282.22  5177.5  281.45
  5185.1  282.39  5333.7  283.01  5425.5  285.26    5567  289.62  5759.4  293.51
  5864.7  294.18  5878.1  294.67  6036.4  294.77  6089.4  295.31  6096.7  295.35
#Mann= 4 ,-1 , 0
  4400.8     .16       0    4824     .12       0  5057.6     .16       0
  6089.4      .1       0
#XS Ineff= 1 ,-1
 5054.55 5822.61  292.48
Permanent Ineff=
       T
Bank Sta=4760.5,5050.2
XS Rating Curve= 0 ,0
Exp/Cntr=0.3,0.1

Type RM Length L Ch R = 1 ,2475    ,197,197,197
BEGIN DESCRIPTION:
UNT063 IN SUCR 6.0
END DESCRIPTION:
XS GIS Cut Line= 5
      2285067.54     13392729.23      2285414.78     13393319.54
      2285432.14     13393553.91      2285484.22      13393692.8
      2286499.86     13393901.14
#Sta/Elev= 30
  4034.4  304.81  4046.8  304.79  4089.8  302.28  4296.9  295.48    4457  289.12
  4675.7  282.37  4736.6  281.25  4806.8  280.43  4824.3  282.37  4829.3   281.4
  4836.9  283.46    4857  286.45    4867   286.4    4887  283.01  4897.1  280.07
  4907.1  279.26  5021.5   279.5  5085.3  278.68  5149.9  279.22  5157.2  281.24
  5167.4  281.68  5279.7  283.82  5320.6  285.74    5341  285.33  5575.8   287.2
  5616.6  288.46  5657.4  288.48  5820.8   291.7  5912.6  293.21  6139.4  293.95
#Mann= 5 ,-1 , 0
  4034.4     .05       0  4296.9     .12       0    4887     .07       0
  5279.7     .12       0  5820.8      .1       0
#XS Ineff= 1 ,-1
 4200.28 4856.53291.6299
Permanent Ineff=
       T
Bank Sta=4867,5320.6
XS Rating Curve= 0 ,0
Exp/Cntr=0.3,0.1

Type RM Length L Ch R = 1 ,2278    ,125,125,125
BEGIN DESCRIPTION:
UNT063 IN SUCR 5.0
END DESCRIPTION:
XS GIS Cut Line= 6
      2284787.69     13392896.82      2285345.33     13393493.15
      2285301.93     13393571.28      2285310.61     13393736.21
       2285449.5     13393805.65      2286491.16     13394057.38
#Sta/Elev= 30
  3928.9  305.14    4148  297.22  4523.2  281.73  4678.8  277.55  4707.4  282.15
  4714.2  285.52  4728.4  286.48  4774.7   286.1  4790.8  284.32  4796.5  285.89
  4828.5  284.82  4833.9  285.93  4860.3  284.21  4950.5  287.05  4990.5  286.08
    5019  287.49  5029.7  286.94  5124.8  286.36  5141.5  284.58  5147.1  285.52
  5163.6  284.49  5180.3  280.39  5194.5  279.68    5311   283.3  5338.5  283.52
  5352.9   282.1  5436.6  284.32  5483.6  283.34  5823.7  290.02  6226.8  293.25
#Mann= 5 ,-1 , 0
  3928.9     .05       0    4148     .16       0  4950.5     .12       0
  5029.7     .16       0  6226.8      .1       0
#XS Ineff= 2 ,-1
 3931.25 4935.23295.0197 5064.77 5911.93292.1299
Permanent Ineff=
       T       T
Bank Sta=4950.5,5019
XS Rating Curve= 0 ,0
Exp/Cntr=0.3,0.1

Type RM Length L Ch R = 1 ,2153    ,153,153,153
BEGIN DESCRIPTION:
Mapping XS 663a6e08
END DESCRIPTION:
XS GIS Cut Line= 4
      2284676.96     13393180.68      2285128.32     13393727.53
       2285536.3     13394144.19      2286439.06     13394239.68
#Sta/Elev= 30
  4163.9  301.07  4261.7  297.26    4289  294.35  4296.9  295.13    4375  291.62
  4453.2   286.2  4509.2  283.17  4573.9  277.96  4609.5  277.19  4978.1  278.28
  5003.4  273.97  5006.2  273.47  5013.4  275.24  5020.6  278.49    5063  278.84
    5070  279.99  5091.3   278.4  5218.6  278.98  5239.7  276.81  5246.9  278.54
  5310.5  279.46    5360  279.13  5374.2     278  5395.3  279.61  5459.3  279.07
  5879.9  286.55  6050.8  289.16    6081  288.72  6282.1  293.27  6363.9  293.95
#Mann= 5 ,-1 , 0
  4163.9     .05       0  4453.2     .16       0  5003.4     .12       0
  5020.6     .16       0  5879.9     .05       0
#XS Ineff= 2 ,-1
  4399.4 4956.71  281.63 5066.21 6359.65281.6271
Permanent Ineff=
       T       T
Bank Sta=4978.1,5020.6
XS Rating Curve= 0 ,0
Exp/Cntr=0.3,0.1

Type RM Length L Ch R = 1 ,2000    ,495,495,495
BEGIN DESCRIPTION:
UNT063 IN SUCR 4.0
END DESCRIPTION:
XS GIS Cut Line= 3
      2284737.71     13393596.85      2285137.72     13393946.85
      2285637.69     13394546.82
#Sta/Elev= 30
  4469.1  288.95  4539.8  285.46  4582.5  282.07  4695.5  275.98  4714.3  274.07
  4717.1  273.57  4720.3  274.07  4774.3  275.95  4823.6  276.16  4837.8  275.34
  4852.1  276.46  4893.9  276.27  4944.1  276.43  4958.4  274.79  4979.3  275.55
  5003.9  274.33  5028.6   276.7  5042.9  276.91  5085.9  276.09    5121  276.76
  5143.2  274.91  5170.5  276.71  5228.4  276.44  5242.1   277.1  5256.4  276.11
  5334.5  278.19  5361.4  278.11  5469.2  280.48  5589.6  284.86  5781.6  290.11
#Mann= 7 ,-1 , 0
  4469.1     .05       0  4695.5      .1       0  4714.3     .07       0
  4720.3      .1       0  4893.9     .12       0  5228.4      .1       0
  5361.4     .05       0
Bank Sta=4714.3,4720.3
XS Rating Curve= 0 ,0
Exp/Cntr=0.3,0.1

Type RM Length L Ch R = 1 ,1505    ,624,624,624
BEGIN DESCRIPTION:
UNT063 IN SUCR 3.0
END DESCRIPTION:
XS GIS Cut Line= 3
      2284537.71     13393796.84      2284837.72     13394196.85
      2285537.74     13394796.87
#Sta/Elev= 30
    4516  290.89    4566  288.26  4717.7  282.19  4729.6  282.23  4773.3  280.12
    4816  279.04  4823.3   278.2  4852.5  277.01  4944.1  274.82  4952.5  273.76
  4999.5   272.9  5002.2   272.4  5005.5   272.9  5037.4  274.32  5051.7  273.81
  5172.4  273.77  5236.1  274.48  5271.2  274.17  5278.9  274.71  5306.3  274.38
  5377.7  275.64  5533.5  280.09  5547.8   281.2  5576.3  281.97  5611.4  281.88
  5633.4  282.51  5654.3  283.82  5781.6  288.05  5902.3  290.17    5938   291.4
#Mann= 4 ,-1 , 0
    4516      .1       0  4717.7     .05       0  4999.5    .035       0
  5005.5     .05       0
Bank Sta=4999.5,5005.5
XS Rating Curve= 0 ,0
Exp/Cntr=0.3,0.1

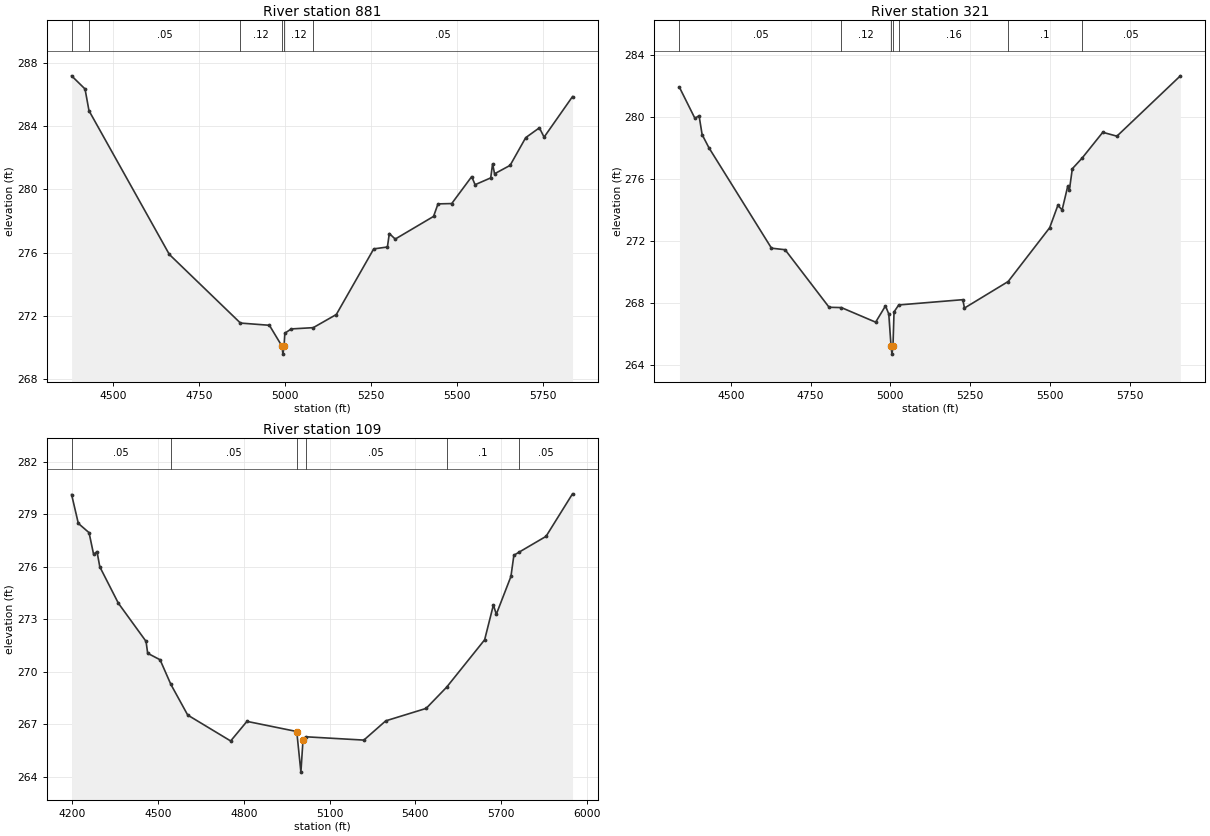
Type RM Length L Ch R = 1 ,881     ,560,560,560
BEGIN DESCRIPTION:
UNT063 IN SUCR 2.0
END DESCRIPTION:
XS GIS Cut Line= 4
      2284372.19     13393886.59      2284318.09     13394121.01
      2284522.49     13394704.17      2285062.32     13394962.08
#Sta/Elev= 30
  4378.2  287.16  4417.3  286.33  4428.8  284.96  4662.5  275.89  4869.3  271.56
  4953.5  271.42  4990.1   270.1  4992.8   269.6  4996.1   270.1  4998.4  270.92
    5017  271.19    5081  271.27  5148.1   272.1  5256.9  276.24  5296.7  276.36
  5302.2  277.21  5319.4  276.86  5430.9  278.29  5443.8  279.08  5483.7   279.1
  5541.8   280.8  5551.7  280.29  5597.1  280.72  5602.6  281.61  5608.3  280.98
  5653.5  281.51  5698.9  283.26  5738.7  283.88  5752.3  283.29    5835  285.85
#Mann= 6 ,-1 , 0
  4378.2      .1       0  4428.8     .05       0  4869.3     .12       0
  4990.1     .07       0  4996.1     .12       0    5081     .05       0
Bank Sta=4990.1,4996.1
XS Rating Curve= 0 ,0
Exp/Cntr=0.3,0.1

Type RM Length L Ch R = 1 ,321     ,212,212,212
BEGIN DESCRIPTION:
UNT063 IN SUCR 1.0
END DESCRIPTION:
XS GIS Cut Line= 4
      2284182.13     13394005.31       2283930.4     13394421.97
      2284017.21     13394795.23      2284676.89      13395029.6
#Sta/Elev= 30
  4339.2  281.92  4387.7  279.92  4400.7  280.09  4410.3  278.87  4431.7  278.02
  4627.7  271.55  4670.4  271.45  4808.3  267.74  4846.8  267.72  4954.2  266.78
    4985  267.83  4995.3  267.31  5002.5  265.22  5005.3  264.72  5008.5  265.22
  5011.8  267.44  5026.5  267.89  5227.3  268.23  5232.6  267.69  5369.5   269.4
  5499.7  272.87  5525.3  274.31  5538.7  274.02  5556.1  275.53  5561.4  275.29
  5570.6  276.67  5601.4  277.36  5666.1  279.02  5710.4  278.77  5909.3  282.66
#Mann= 7 ,-1 , 0
  4339.2     .05       0  4846.8     .12       0  5002.5     .07       0
  5008.5     .12       0  5026.5     .16       0  5369.5      .1       0
  5601.4     .05       0
Bank Sta=5002.5,5008.5
XS Rating Curve= 0 ,0
Exp/Cntr=0.3,0.1

Type RM Length L Ch R = 1 ,109     ,0,0,0
BEGIN DESCRIPTION:
UNT063 IN SUCR 1.0
END DESCRIPTION:
XS GIS Cut Line= 4
      2283983.15     13393999.27       2283708.4     13394487.56
      2283911.53     13394956.31      2284578.24     13395103.46
#Sta/Elev= 30
  4196.9  280.12  4220.5  278.47  4258.1  277.94    4274   276.7  4285.9  276.86
  4295.7  275.99  4360.7  273.91  4457.6  271.73  4463.3  271.05  4506.7  270.68
  4544.3  269.28  4603.5  267.52  4753.9  266.04  4810.9  267.16  4985.3  266.58
  4999.8  264.26  5007.1  266.08    5016  266.28  5220.2  266.09  5296.9  267.19
  5438.2   267.9  5509.9  269.11  5643.1  271.82  5673.8  273.81    5684  273.28
  5735.2  275.44  5745.5  276.65  5762.9  276.82  5858.1  277.73  5950.8  280.16
#Mann= 6 ,-1 , 0
  4196.9     .05       0  4544.3     .05       0  4985.3     .03       0
    5016     .05       0  5509.9      .1       0  5762.9     .05       0
Bank Sta=4985.3,5007.1
XS Rating Curve= 0 ,0
Exp/Cntr=0.3,0.1

Chan Stop Cuts=-1
Use User Specified Reach Order=0
Composite Channel Slope=5