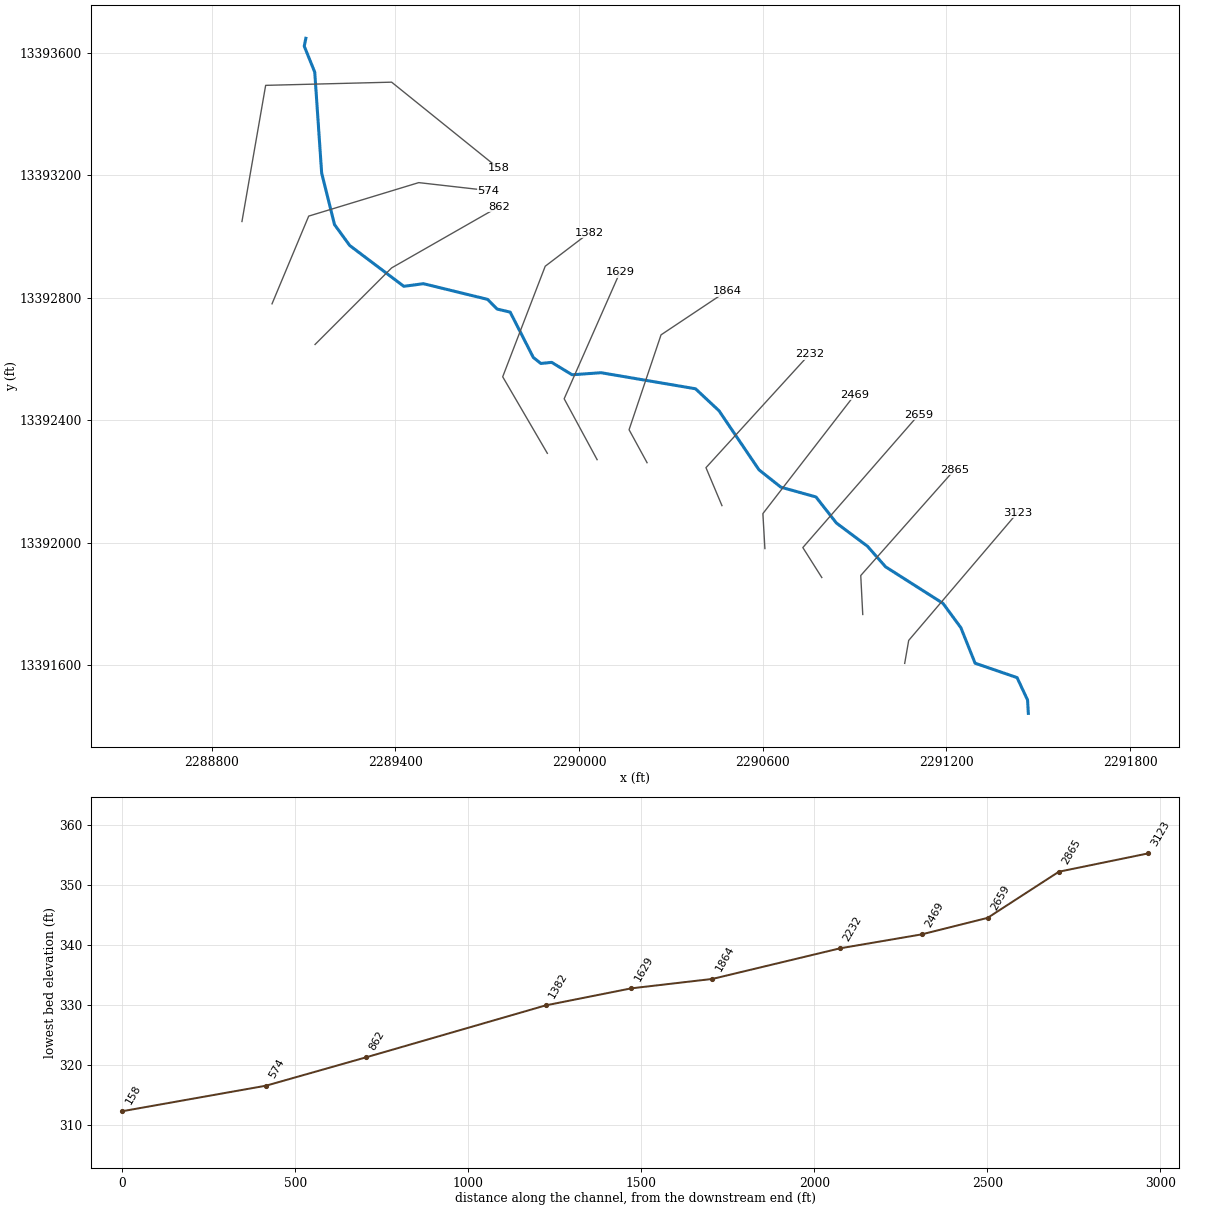
--- UNT064 IN SUCR.prj (project) ---

Proj Title=UNT064 IN SUCR Base Level Engineering
Current Plan=p01
Default Exp/Contr=0.3,0.1
English Units
Geom File=g01
Flow File=f01
Plan File=p01
Y Axis Title=Elevation
X Axis Title(PF)=Main Channel Distance
X Axis Title(XS)=Station
BEGIN DESCRIPTION:
UNT064 IN SUCR
END DESCRIPTION:
DSS Export Rating Curves= 0
DSS Export Rating Curve Sorted= 0
DSS Export Volume Flow Curves= 0
DXF OffsetX= 0
DXF OffsetY= 0
DXF ScaleX= 1
DXF ScaleY= 10

--- UNT064 IN SUCR.p01 (plan) ---

Plan Title=Multiple Run
Short Identifier=Multiple
Geom File=g01
Flow File=f01
Subcritical Flow
K Sum by GR= 0
Std Step Tol= 0.01
Critical Tol= 0.01
Num of Std Step Trials= 20
Max Error Tol= 0.3
Flow Tol Ratio= 0.001
Split Flow NTrial= 30
Split Flow Tol= 0.02
Split Flow Ratio= 0.02
Log Output Level= 0
Friction Slope Method= 1
Unsteady Friction Slope Method= 2
Unsteady Bridges Friction Slope Method= 1
Parabolic Critical Depth
Global Vel Dist=  1 , 1 , 1
Global Log Level= 0
CheckData=True
Encroach Param= -1, 0, 0, 0
BEGIN DESCRIPTION:
Multiple Run
END DESCRIPTION:

--- UNT064 IN SUCR.f01 (steady flow) ---

Flow Title=Multiple
Program Version=4.10
Number of Profiles= 7
Profile Names=10-year,25-year,50-year,1pct_min,100-year,1pct_plu,500-year
River Rch & RM=UNT064 IN SUCR,Reach-1         ,3123
     368     514     636     578     781    1057    1182
Boundary for River Rch & Prof#=UNT064 IN SUCR,Reach-1         , 1
Up Type= 0
Dn Type= 3
Dn Slope=0.0105
Boundary for River Rch & Prof#=UNT064 IN SUCR,Reach-1         , 2
Up Type= 0
Dn Type= 3
Dn Slope=0.0105
Boundary for River Rch & Prof#=UNT064 IN SUCR,Reach-1         , 3
Up Type= 0
Dn Type= 3
Dn Slope=0.0105
Boundary for River Rch & Prof#=UNT064 IN SUCR,Reach-1         , 4
Up Type= 0
Dn Type= 3
Dn Slope=0.0105
Boundary for River Rch & Prof#=UNT064 IN SUCR,Reach-1         , 5
Up Type= 0
Dn Type= 3
Dn Slope=0.0105
Boundary for River Rch & Prof#=UNT064 IN SUCR,Reach-1         , 6
Up Type= 0
Dn Type= 3
Dn Slope=0.0105
Boundary for River Rch & Prof#=UNT064 IN SUCR,Reach-1         , 7
Up Type= 0
Dn Type= 3
Dn Slope=0.0105
DSS Import GetInterval= 0
DSS Import GetPeak= 0
DSS Import FillOption= 0

--- UNT064 IN SUCR.g01 (geometry) ---

Geom Title=Existing Conditions
Program Version=4.10

River Reach=UNT064 IN SUCR  ,Reach-1
Reach XY= 30
      2291467.72     13391441.86      2291465.09     13391485.62
      2291430.91     13391558.66      2291293.76     13391605.77
       2291247.3     13391721.68       2291188.8     13391801.31
      2291001.33     13391920.63      2290942.08     13391987.93
      2290840.99     13392063.38      2290773.87     13392148.83
      2290659.32     13392180.73       2290587.8     13392237.43
      2290457.25     13392430.36      2290380.55     13392502.13
      2290071.97     13392554.63       2289977.5     13392547.84
      2289910.61     13392588.49      2289875.21     13392584.78
      2289850.66     13392604.49      2289775.14     13392752.56
       2289732.5     13392762.49      2289701.34     13392794.17
      2289491.97     13392845.38      2289427.72     13392836.85
      2289250.98     13392970.17      2289201.37     13393038.33
      2289159.33     13393206.93      2289136.75     13393536.46
      2289102.47     13393621.25      2289107.72     13393646.85

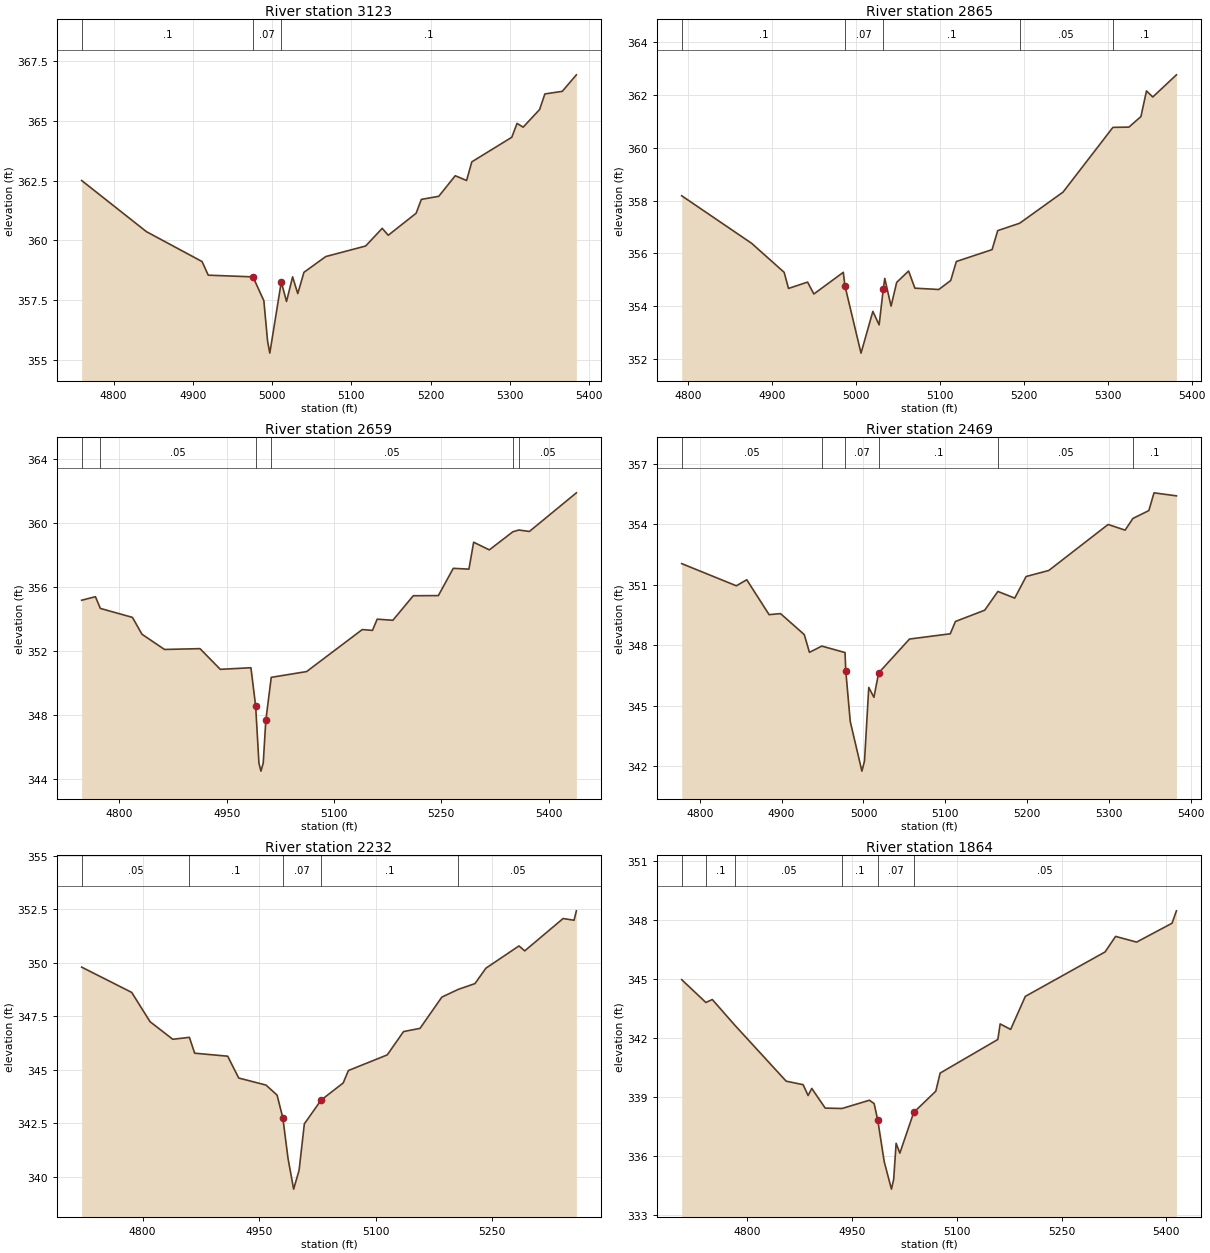
Type RM Length L Ch R = 1 ,3123    ,258,258,258
BEGIN DESCRIPTION:
UNT064 IN SUCR 7.0
END DESCRIPTION:
XS GIS Cut Line= 3
       2291063.8     13391605.13      2291076.84     13391680.13
      2291432.38     13392097.64
#Sta/Elev= 30
  4759.6   362.5  4841.4  360.36  4911.6  359.11  4919.4  358.54  4975.9  358.47
  4989.6  357.47  4994.3  355.78  4997.1  355.28  5011.6  358.26  5018.2  357.44
  5025.9  358.47  5032.4  357.77  5040.2  358.66  5067.8  359.32  5118.1  359.76
    5139   360.5  5146.6  360.21  5181.8  361.13  5188.4  361.71  5210.4  361.84
  5231.2   362.7  5245.5   362.5  5252.1  363.28  5302.6  364.31  5309.2  364.89
  5316.9  364.73  5337.7  365.47  5344.3  366.12  5366.3  366.23  5384.1  366.92
#Mann= 3 , 0 , 0
  4759.6      .1       0  4975.9     .07       0  5011.6      .1       0
Bank Sta=4975.9,5011.6
XS Rating Curve= 0 ,0
Exp/Cntr=0.3,0.1

Type RM Length L Ch R = 1 ,2865    ,206,206,206
BEGIN DESCRIPTION:
Mapping XS d360dae8
END DESCRIPTION:
XS GIS Cut Line= 3
      2290926.79     13391764.89      2290920.27     13391892.15
      2291226.91     13392237.94
#Sta/Elev= 30
  4792.3  358.18  4875.6  356.38  4914.4  355.28  4919.6  354.67  4942.3  354.91
  4949.8  354.46  4984.9  355.28 4986.76  354.78    5006  352.22  5020.1   353.8
  5027.6  353.29  5032.5  354.64  5034.3  355.05  5041.8     354  5048.5   354.9
  5062.7  355.33  5070.2  354.68  5098.7  354.63  5112.9  354.97  5119.6  355.69
  5162.2  356.14  5168.9  356.86  5195.1  357.14  5246.8  358.32  5306.2  360.77
  5325.3  360.78  5339.6  361.18  5346.2  362.15  5353.7  361.92  5381.9  362.76
#Mann= 5 ,-1 , 0
  4792.3      .1       0 4986.76     .07       0  5032.5      .1       0
  5195.1     .05       0  5306.2      .1       0
Bank Sta=4986.76,5032.5
XS Rating Curve= 0 ,0
Exp/Cntr=0.3,0.1

Type RM Length L Ch R = 1 ,2659    ,190,190,190
BEGIN DESCRIPTION:
UNT064 IN SUCR 6.0
END DESCRIPTION:
XS GIS Cut Line= 3
      2290793.05     13391885.63      2290731.08     13391983.48
      2291109.47     13392417.33
#Sta/Elev= 30
  4747.3  355.17  4766.6  355.39  4773.4  354.66  4818.3   354.1  4831.6  353.05
  4863.1   352.1  4912.7  352.15  4941.1  350.86  4983.9  350.96  4990.5  348.58
  4995.1  345.01  4997.9  344.51  5001.1  345.01  5004.7  347.67  5012.3  350.36
  5061.7  350.72  5139.5  353.34  5153.8  353.29  5160.4  353.99  5182.3  353.92
  5210.8  355.45  5245.9  355.46  5266.7  357.16  5288.6  357.11  5295.2  358.79
  5317.1  358.31    5350  359.44  5358.4  359.55  5373.1  359.46  5438.8  361.87
#Mann= 6 ,-1 , 0
  4747.3      .1       0  4773.4     .05       0  4990.5     .03       0
  5012.3     .05       0    5350      .1       0  5358.4     .05       0
Bank Sta=4990.5,5004.7
XS Rating Curve= 0 ,0
Exp/Cntr=0.3,0.1

Type RM Length L Ch R = 1 ,2469    ,237,237,237
BEGIN DESCRIPTION:
Mapping XS 5ece0233
END DESCRIPTION:
XS GIS Cut Line= 3
      2290607.13     13391980.19       2290600.6     13392094.39
      2290900.44     13392482.22
#Sta/Elev= 30
  4777.9  352.05  4844.7  350.95  4857.4  351.25  4884.7  349.52  4898.7  349.57
  4927.7  348.53    4934  347.65  4949.1  347.96  4977.5  347.64 4978.41  346.73
  4983.9  344.22  4998.1  341.76  5001.3  342.26  5006.5  345.91  5012.8  345.42
 5018.58  346.63  5056.3  348.31  5106.1  348.57  5112.4  349.18  5148.2  349.74
  5164.3  350.67  5184.9  350.34  5198.8  351.41  5226.5  351.71    5299  353.99
  5319.8  353.71  5329.3  354.29  5348.8  354.68  5355.1  355.56  5382.5  355.41
#Mann= 6 ,-1 , 0
  4777.9     .05       0  4949.1      .1       0  4977.5     .07       0
 5018.58      .1       0  5164.3     .05       0  5329.3      .1       0
Bank Sta=4978.41,5018.58
XS Rating Curve= 0 ,0
Exp/Cntr=0.3,0.1

Type RM Length L Ch R = 1 ,2232    ,368,368,368
BEGIN DESCRIPTION:
UNT064 IN SUCR 5.0
END DESCRIPTION:
XS GIS Cut Line= 3
      2290466.86     13392120.49      2290414.67     13392244.44
      2290753.28     13392615.61
#Sta/Elev= 30
  4721.5  349.79  4785.9  348.61  4809.6  347.24  4838.8  346.42  4860.2  346.51
    4867  345.77  4909.5  345.63  4923.7  344.61  4958.9  344.28  4973.1  343.81
  4980.5  342.75  4987.2  340.85  4994.4  339.42  5001.4   340.3  5008.2  342.47
  5029.8  343.58  5058.2  344.38  5064.9  344.96  5114.9  345.69  5135.9  346.78
  5157.1  346.93  5185.2  348.39  5206.3  348.75  5227.8  349.02  5241.9  349.74
  5284.5  350.78  5291.9  350.55  5341.3  352.06  5355.4  351.98  5358.4  352.42
#Mann= 5 ,-1 , 0
  4721.5     .05       0  4860.2      .1       0  4980.5     .07       0
  5029.8      .1       0  5206.3     .05       0
Bank Sta=4980.5,5029.8
XS Rating Curve= 0 ,0
Exp/Cntr=0.3,0.1

Type RM Length L Ch R = 1 ,1864    ,235,235,235
BEGIN DESCRIPTION:
UNT064 IN SUCR 4.0
END DESCRIPTION:
XS GIS Cut Line= 4
      2290222.23     13392260.73       2290163.5     13392368.39
      2290267.89     13392678.27      2290482.95     13392821.65
#Sta/Elev= 30
  4706.4  344.97    4741  343.81  4750.2  343.96  4782.3  342.66  4855.9  339.81
  4880.2  339.63  4887.3  339.08  4892.6  339.44  4911.8  338.44  4935.9  338.42
  4975.1  338.84  4981.8  338.67  4987.1  337.81  4996.3  335.71  5006.6  334.32
  5009.8  334.82  5013.3  336.65  5018.6  336.15  5038.5  338.22  5070.1   339.3
  5076.3  340.22  5158.9  341.93  5162.2  342.72  5177.2  342.44  5198.2  344.12
  5312.4  346.38  5327.4  347.17  5357.5  346.88  5408.2  347.84  5414.5  348.47
#Mann= 6 ,-1 , 0
  4706.4     .05       0    4741      .1       0  4782.3     .05       0
  4935.9      .1       0  4987.1     .07       0  5038.5     .05       0
Bank Sta=4987.1,5038.5
XS Rating Curve= 0 ,0
Exp/Cntr=0.3,0.1

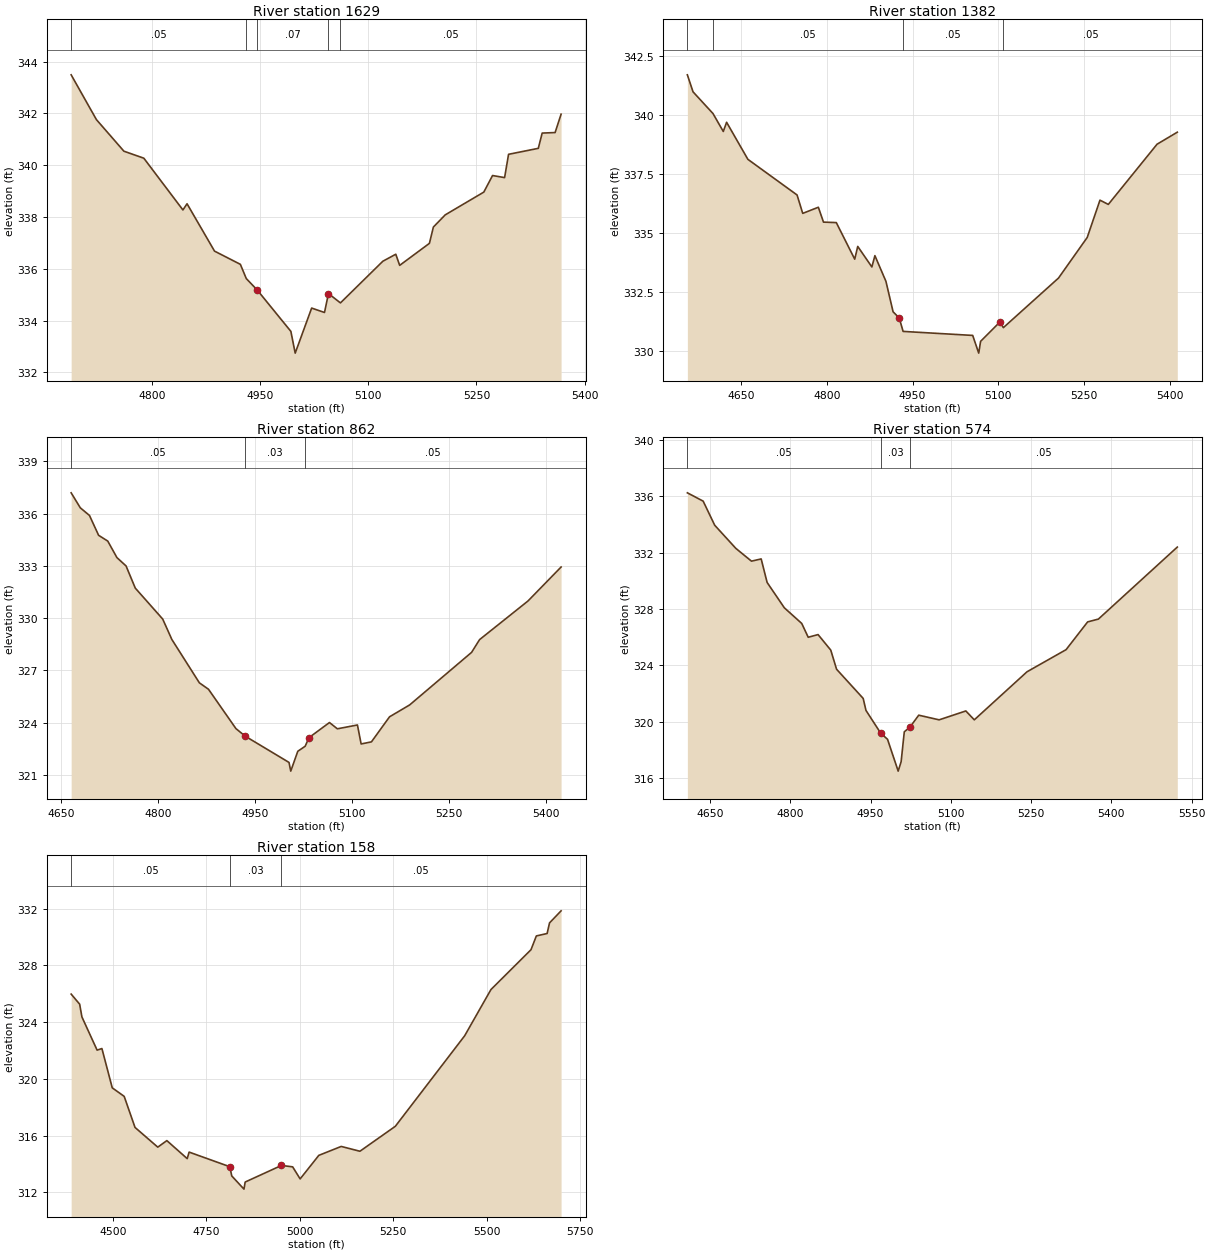
Type RM Length L Ch R = 1 ,1629    ,247,247,247
BEGIN DESCRIPTION:
Mapping XS 7005949d
END DESCRIPTION:
XS GIS Cut Line= 3
      2290059.13     13392270.53      2289951.48     13392469.51
      2290134.16     13392883.79
#Sta/Elev= 30
  4688.3  343.49  4723.3  341.76  4761.4  340.54    4789  340.27  4843.2  338.27
  4848.9  338.51    4887  336.68  4922.8  336.17    4931  335.62  4946.1  335.18
  4992.8  333.58  4998.8  332.74  5021.6  334.48  5039.4  334.31  5044.9  335.04
  5061.5  334.68  5120.3  336.29  5138.2  336.56  5143.6  336.13  5184.8  336.98
  5190.3  337.61  5206.7  338.08  5260.2  338.96  5272.3   339.6    5289  339.52
  5294.5  340.42  5335.7  340.65  5341.1  341.24    5359  341.26  5367.3  341.97
#Mann= 5 ,-1 , 0
  4688.3     .05       0    4931      .1       0  4946.1     .07       0
  5044.9      .1       0  5061.5     .05       0
Bank Sta=4946.1,5044.9
XS Rating Curve= 0 ,0
Exp/Cntr=0.3,0.1

Type RM Length L Ch R = 1 ,1382    ,520,520,520
BEGIN DESCRIPTION:
UNT064 IN SUCR 3.0
END DESCRIPTION:
XS GIS Cut Line= 4
      2289896.52     13392291.31      2289750.69     13392541.31
      2289889.58     13392902.42      2290032.97     13393011.68
#Sta/Elev= 30
  4556.3  341.69  4566.2  340.97  4601.1  340.05  4619.1  339.29  4624.9  339.68
  4662.1  338.11  4748.1   336.6    4758  335.82  4785.3  336.08  4794.3  335.45
  4816.7  335.43  4848.9  333.88  4854.2  334.42  4878.9  333.55  4884.2  334.03
  4903.5  332.94    4916  331.65  4926.7  331.39  4933.5  330.82  5055.2  330.65
  5065.7   329.9    5069   330.4  5102.8  331.22  5108.8  330.98  5205.2  333.08
  5255.4   334.8  5277.7  336.38  5292.3   336.2  5377.5  338.75  5412.9  339.26
#Mann= 4 ,-1 , 0
  4556.3      .1       0  4601.1     .05       0  4933.5     .05       0
  5108.8     .05       0
Bank Sta=4926.7,5102.8
XS Rating Curve= 0 ,0
Exp/Cntr=0.3,0.1

Type RM Length L Ch R = 1 ,862     ,288,288,288
BEGIN DESCRIPTION:
UNT064 IN SUCR 2.0
END DESCRIPTION:
XS GIS Cut Line= 3
      2289137.74     13392646.87      2289387.72     13392896.85
      2289737.68     13393096.83
#Sta/Elev= 30
  4666.1  337.19  4680.2  336.33  4694.4  335.89  4708.5  334.75  4722.6  334.42
  4736.8  333.47  4750.9  332.99  4765.1  331.72  4807.5  329.94  4821.6  328.77
  4864.1  326.28  4878.2  325.91  4920.6  323.65  4934.8  323.22  5002.5  321.71
  5005.2  321.21  5016.1  322.35  5027.5  322.64  5033.3  323.13    5065     324
  5077.2  323.64  5108.2  323.86  5113.9  322.77  5129.8  322.89  5157.8  324.33
  5188.8  325.01  5284.5  328.03  5296.8  328.76  5371.6  330.98  5422.7  332.93
#Mann= 3 ,-1 , 0
  4666.1     .05       0  4934.8     .03       0  5027.5     .05       0
Bank Sta=4934.8,5033.3
XS Rating Curve= 0 ,0
Exp/Cntr=0.3,0.1

Type RM Length L Ch R = 1 ,574     ,416,416,416
BEGIN DESCRIPTION:
Mapping XS c5417a65
END DESCRIPTION:
XS GIS Cut Line= 4
      2288997.22     13392779.67      2289117.03     13393066.18
      2289476.41     13393175.55      2289704.15     13393149.67
#Sta/Elev= 30
  4607.8  336.24  4637.3  335.65  4658.9  333.94  4698.3   332.3  4727.6  331.39
  4745.7  331.55  4756.8  329.88    4789  328.08  4821.5  326.97  4833.6  325.99
    4852  326.18  4875.7  325.08  4886.6  323.72  4936.3  321.65  4941.5   320.8
  4969.1  319.18  4981.8  318.75  5001.7  316.49  5007.2  317.16  5013.1  319.28
  5023.6  319.61  5040.1  320.46  5078.2  320.13  5128.1  320.76  5143.9  320.13
  5242.4  323.54  5315.4  325.11  5355.7  327.08  5375.8  327.28  5523.2  332.39
#Mann= 3 , 0 , 0
  4607.8     .05       0  4969.1     .03       0  5023.6     .05       0
Bank Sta=4969.1,5023.6
XS Rating Curve= 0 ,0
Exp/Cntr=0.3,0.1

Type RM Length L Ch R = 1 ,158     ,0,0,0
BEGIN DESCRIPTION:
UNT064 IN SUCR 1.0
END DESCRIPTION:
XS GIS Cut Line= 4
        2288899.     13393048.51      2288976.41     13393493.26
      2289387.87     13393503.68      2289736.82     13393222.43
#Sta/Elev= 30
  4387.8  325.97  4410.5  325.26  4416.6  324.36  4457.2  322.02  4470.1  322.13
  4497.8  319.36  4529.7  318.76  4558.7  316.57  4619.6  315.18  4643.9  315.64
  4698.4  314.37  4703.5  314.83  4812.4   313.8  4817.6  313.15  4850.3  312.22
  4853.5  312.72  4950.6  313.89  4980.6  313.79  5000.6  312.94  5050.6   314.6
  5110.6  315.23  5160.6  314.89  5255.4  316.65  5440.9  323.03  5511.3  326.29
  5618.5   329.1  5632.8  330.07  5661.6  330.24  5668.1  330.99    5699  331.84
#Mann= 3 , 0 , 0
  4387.8     .05       0  4812.4     .03       0  4950.6     .05       0
Bank Sta=4812.4,4950.6
XS Rating Curve= 0 ,0
Exp/Cntr=0.3,0.1

Chan Stop Cuts=-1
Use User Specified Reach Order=0
Composite Channel Slope=5