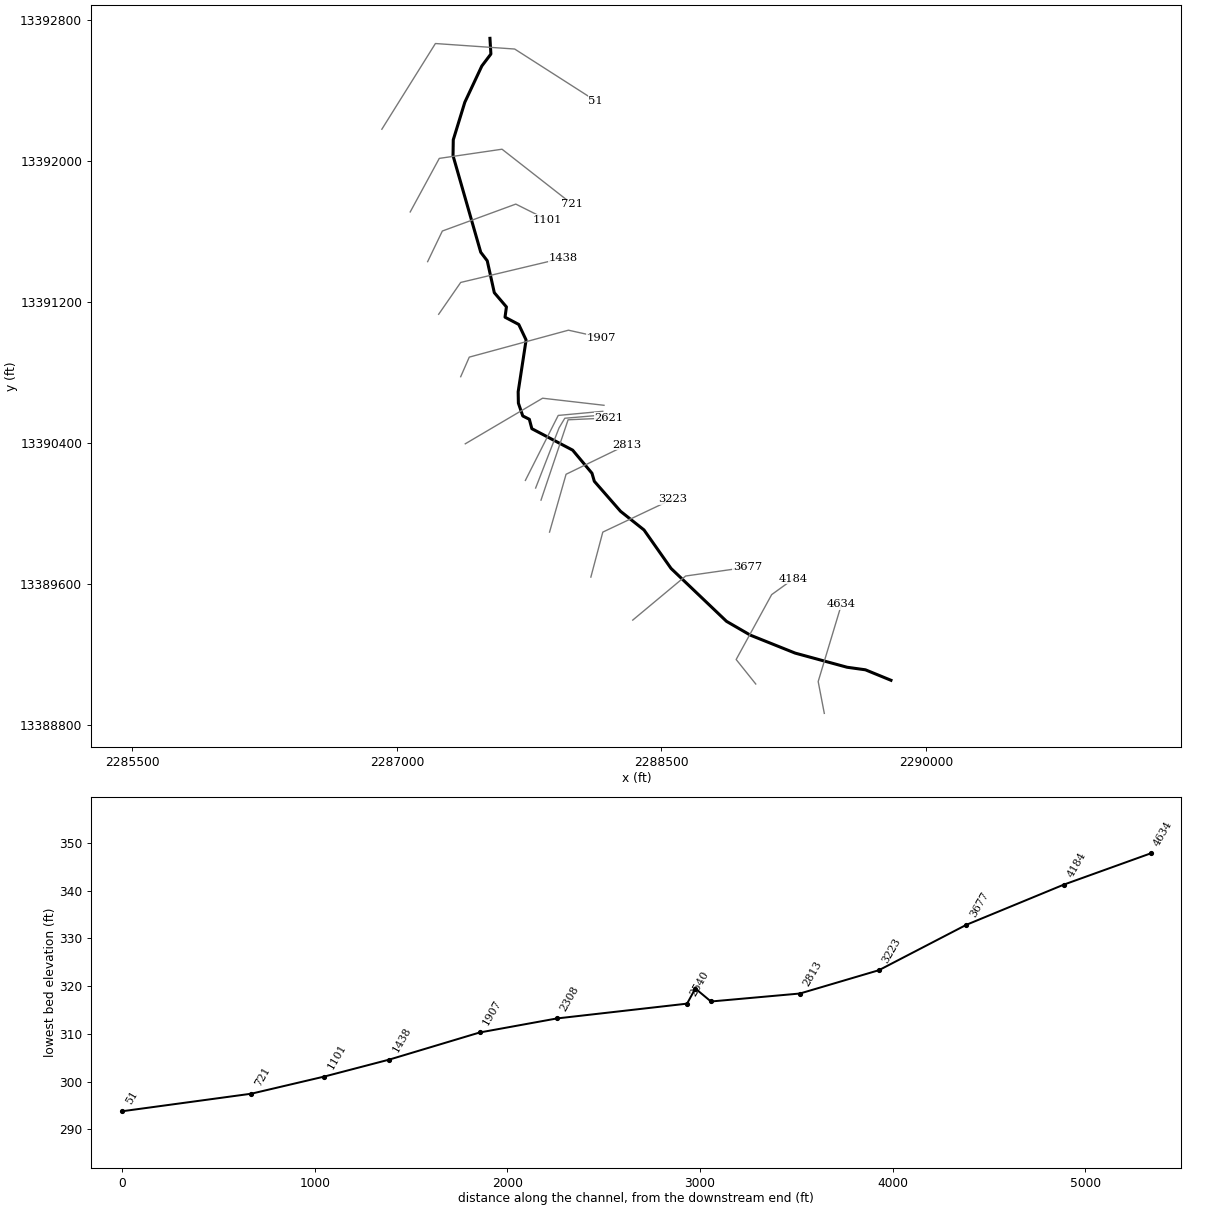
--- UNT065 IN SUCR.prj (project) ---

Proj Title=UNT065 IN SUCR Base Level Engineering
Current Plan=p01
Default Exp/Contr=0.3,0.1
English Units
Geom File=g01
Flow File=f01
Plan File=p01
Y Axis Title=Elevation
X Axis Title(PF)=Main Channel Distance
X Axis Title(XS)=Station
BEGIN DESCRIPTION:
UNT065 IN SUCR
END DESCRIPTION:
DSS Export Rating Curves= 0
DSS Export Rating Curve Sorted= 0
DSS Export Volume Flow Curves= 0
DXF OffsetX= 0
DXF OffsetY= 0
DXF ScaleX= 1
DXF ScaleY= 10

--- UNT065 IN SUCR.p01 (plan) ---

Plan Title=Multiple Run
Short Identifier=Multiple
Geom File=g01
Flow File=f01
Subcritical Flow
K Sum by GR= 0
Std Step Tol= 0.01
Critical Tol= 0.01
Num of Std Step Trials= 20
Max Error Tol= 0.3
Flow Tol Ratio= 0.001
Split Flow NTrial= 30
Split Flow Tol= 0.02
Split Flow Ratio= 0.02
Log Output Level= 0
Friction Slope Method= 1
Unsteady Friction Slope Method= 2
Unsteady Bridges Friction Slope Method= 1
Parabolic Critical Depth
Global Vel Dist=  1 , 1 , 1
Global Log Level= 0
CheckData=True
Encroach Param= -1, 0, 0, 0
BEGIN DESCRIPTION:
Multiple Run
END DESCRIPTION:

--- UNT065 IN SUCR.f01 (steady flow) ---

Flow Title=Multiple
Program Version=4.10
Number of Profiles= 7
Profile Names=10-year,25-year,50-year,1pct_min,100-year,1pct_plu,500-year
River Rch & RM=UNT065 IN SUCR,Reach-1         ,4634
     258     358     440     399     540     730     818
Boundary for River Rch & Prof#=UNT065 IN SUCR,Reach-1         , 1
Up Type= 0
Dn Type= 3
Dn Slope=0.01
Boundary for River Rch & Prof#=UNT065 IN SUCR,Reach-1         , 2
Up Type= 0
Dn Type= 3
Dn Slope=0.01
Boundary for River Rch & Prof#=UNT065 IN SUCR,Reach-1         , 3
Up Type= 0
Dn Type= 3
Dn Slope=0.01
Boundary for River Rch & Prof#=UNT065 IN SUCR,Reach-1         , 4
Up Type= 0
Dn Type= 3
Dn Slope=0.01
Boundary for River Rch & Prof#=UNT065 IN SUCR,Reach-1         , 5
Up Type= 0
Dn Type= 3
Dn Slope=0.01
Boundary for River Rch & Prof#=UNT065 IN SUCR,Reach-1         , 6
Up Type= 0
Dn Type= 3
Dn Slope=0.01
Boundary for River Rch & Prof#=UNT065 IN SUCR,Reach-1         , 7
Up Type= 0
Dn Type= 3
Dn Slope=0.01
DSS Import GetInterval= 0
DSS Import GetPeak= 0
DSS Import FillOption= 0

--- UNT065 IN SUCR.g01 (geometry) ---

Geom Title=Existing Conditions
Program Version=4.10

River Reach=UNT065 IN SUCR  ,Reach-1
Reach XY= 30
      2289802.51     13389055.45      2289657.51     13389114.86
      2289553.73     13389129.32      2289258.87     13389209.63
       2289004.9     13389311.42      2288869.55      13389389.8
      2288554.84     13389690.03      2288401.57     13389908.18
       2288268.4     13390014.02      2288119.72     13390184.32
      2288106.48     13390229.82      2287996.95     13390360.79
      2287765.31     13390482.59      2287751.16     13390535.96
      2287713.86     13390554.78      2287689.01     13390627.41
      2287687.74     13390691.82      2287732.77     13390985.86
      2287691.06     13391073.89      2287613.21     13391115.05
      2287621.14     13391173.33      2287552.41      13391254.1
      2287512.34     13391435.09      2287475.44     13391483.45
      2287318.26     13392031.48      2287319.65     13392121.25
      2287385.13     13392334.34      2287481.64     13392539.98
      2287533.04     13392607.83      2287527.72     13392696.85

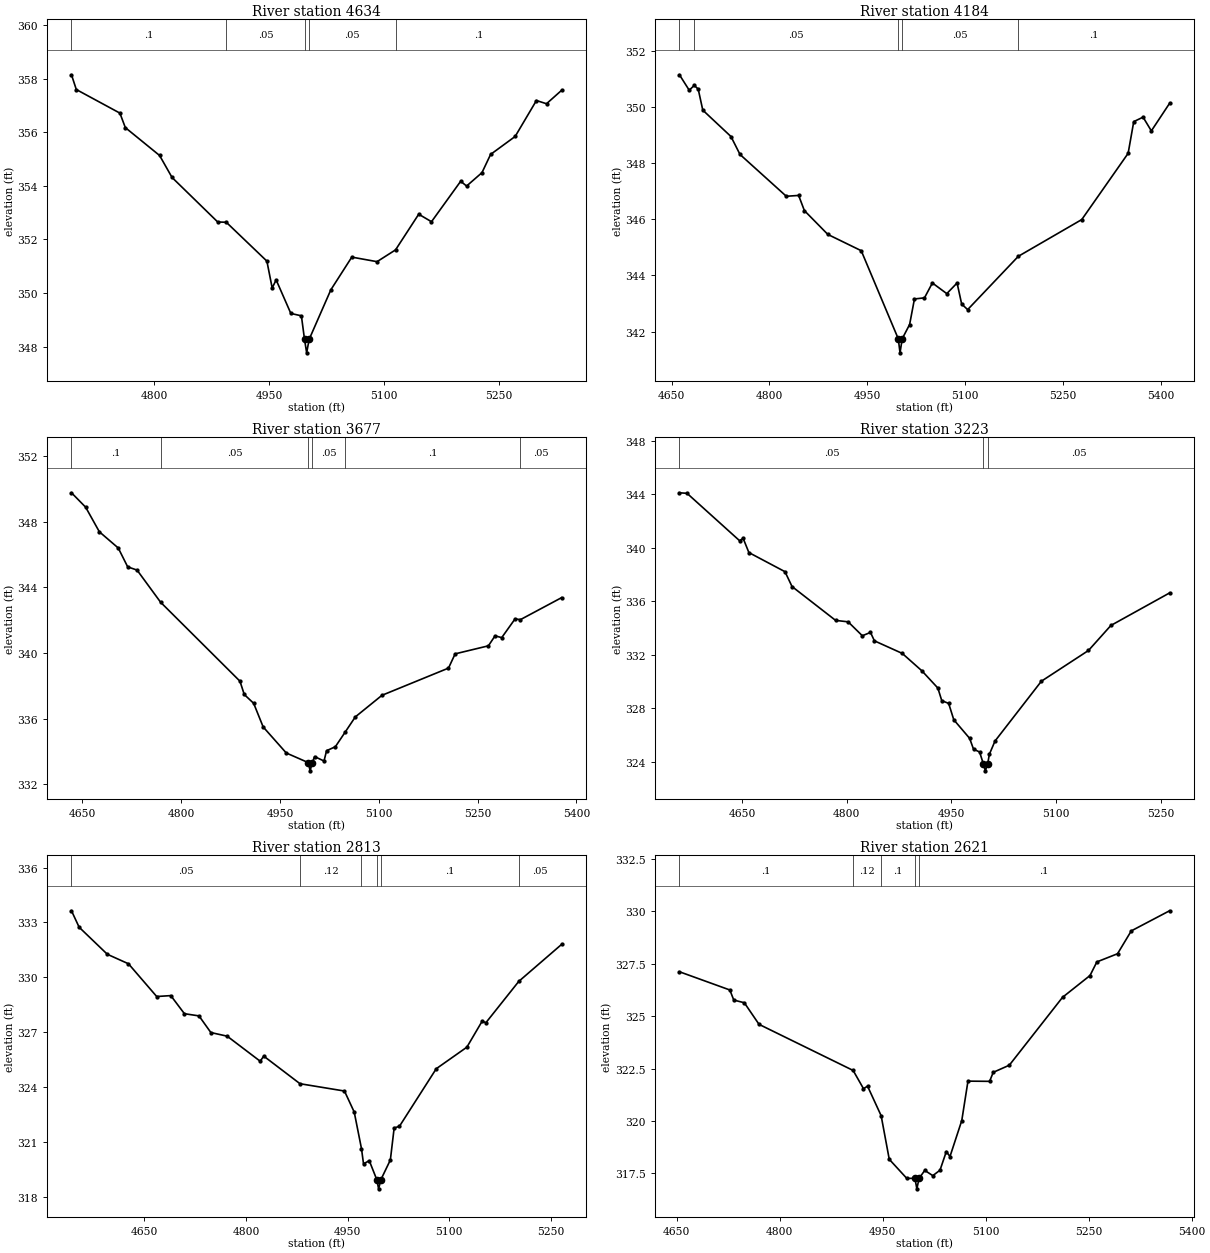
Type RM Length L Ch R = 1 ,4634    ,450,450,450
BEGIN DESCRIPTION:
UNT065 IN SUCR 10.0
END DESCRIPTION:
XS GIS Cut Line= 3
       2289424.3     13388867.71      2289389.58     13389048.26
      2289521.51     13389485.74
#Sta/Elev= 30
  4691.6  358.14  4697.9  357.59  4754.9  356.71    4762  356.17  4806.8  355.13
  4823.1  354.31  4882.8  352.65    4894  352.64  4947.1  351.19    4954  350.19
  4959.2  350.49  4978.4  349.24  4992.2  349.15  4996.3  348.27  4999.1  347.77
  5002.3  348.27  5030.7  350.12  5058.1  351.34  5091.1  351.17  5115.3  351.61
  5145.6  352.94  5162.3  352.66  5200.5  354.17  5208.2  353.99  5228.3  354.49
  5239.6  355.17  5271.7  355.84  5299.5  357.18  5312.7  357.06  5332.4  357.56
#Mann= 5 ,-1 , 0
  4691.6      .1       0    4894     .05       0  4996.3     .03       0
  5002.3     .05       0  5115.3      .1       0
Bank Sta=4996.3,5002.3
XS Rating Curve= 0 ,0
Exp/Cntr=0.3,0.1

Type RM Length L Ch R = 1 ,4184    ,507,507,507
BEGIN DESCRIPTION:
UNT065 IN SUCR 9.0
END DESCRIPTION:
XS GIS Cut Line= 4
      2289035.43     13389034.34       2288924.3     13389173.26
      2289125.69     13389541.31      2289250.66     13389631.57
#Sta/Elev= 30
  4662.1  351.15  4677.1   350.6  4684.8  350.77  4690.9  350.64  4697.9  349.89
  4741.1  348.95    4755  348.31    4826  346.82  4844.9  346.85  4853.7  346.31
  4889.7  345.46  4940.9  344.88  4997.7  341.74  5000.4  341.24  5003.7  341.74
  5015.1  342.25  5022.5  343.16  5037.9   343.2    5050  343.73  5072.1  343.35
  5087.9  343.73  5094.9  342.98  5104.1  342.78  5181.8  344.68  5279.1  345.99
  5350.2  348.35  5358.8  349.48  5373.1  349.64  5385.8  349.15  5413.7  350.13
#Mann= 5 ,-1 , 0
  4662.1      .1       0  4684.8     .05       0  4997.7     .03       0
  5003.7     .05       0  5181.8      .1       0
Bank Sta=4997.7,5003.7
XS Rating Curve= 0 ,0
Exp/Cntr=0.3,0.1

Type RM Length L Ch R = 1 ,3677    ,454,454,454
BEGIN DESCRIPTION:
UNT065 IN SUCR 8.0
END DESCRIPTION:
XS GIS Cut Line= 3
       2288337.7     13389396.84      2288637.72     13389646.85
      2288987.73     13389696.86
#Sta/Elev= 30
  4633.3  349.78  4654.8   348.9  4675.6   347.4  4704.3  346.41  4718.6  345.26
  4732.9  345.06  4768.6   343.1  4889.1  338.28  4895.6  337.47  4909.9  336.93
  4924.3  335.49  4959.4   333.9  4992.9  333.31  4995.6  332.81  4998.9  333.31
  5002.4  333.68  5016.7  333.41  5020.6  334.04  5033.9  334.28  5049.1  335.19
  5064.2   336.1  5104.7  337.42  5205.7  339.08  5215.8  339.95  5266.3  340.44
  5276.4  341.05  5286.5  340.94  5306.7  342.08    5315  342.04  5377.4  343.38
#Mann= 6 ,-1 , 0
  4633.3      .1       0  4768.6     .05       0  4992.9     .03       0
  4998.9     .05       0  5049.1      .1       0    5315     .05       0
Bank Sta=4992.9,4998.9
XS Rating Curve= 0 ,0
Exp/Cntr=0.3,0.1

Type RM Length L Ch R = 1 ,3223    ,410,410,410
BEGIN DESCRIPTION:
UNT065 IN SUCR 7.0
END DESCRIPTION:
XS GIS Cut Line= 3
       2288100.1     13389640.68      2288167.82     13389895.93
      2288563.67     13390083.44
#Sta/Elev= 30
  4560.5   344.1  4571.4  344.06  4646.6  340.52  4651.8  340.69    4660  339.63
  4711.7   338.2  4721.8  337.09  4784.2  334.56  4802.2  334.45  4822.5  333.41
  4834.2  333.66  4839.8  333.03  4879.7  332.09    4908  330.78  4930.7   329.5
  4936.3  328.56  4946.2  328.35  4953.5  327.13  4976.2  325.74  4981.8  324.93
  4990.5  324.72    4996  323.81  4998.7  323.31    5002  323.81  5004.5  324.55
  5012.6  325.54    5079  330.01  5146.5  332.31  5178.6  334.18  5262.6  336.61
#Mann= 3 ,-1 , 0
  4560.5     .05       0    4996     .03       0    5002     .05       0
Bank Sta=4996,5002
XS Rating Curve= 0 ,0
Exp/Cntr=0.3,0.1

Type RM Length L Ch R = 1 ,2813    ,462,462,462
BEGIN DESCRIPTION:
UNT065 IN SUCR 6.0
END DESCRIPTION:
XS GIS Cut Line= 3
      2287865.74     13389895.95      2287959.48     13390224.05
        2288303.     13390390.61
#Sta/Elev= 30
  4542.6  333.64  4553.9  332.74  4595.5  331.26  4626.7  330.74  4668.3  328.95
  4689.1     329  4709.2  328.01  4730.7  327.89  4748.2  326.98  4772.3  326.78
    4821  325.41  4826.2  325.69  4879.7  324.18  4945.3  323.78  4959.7  322.63
  4970.4  320.63  4973.4   319.8  4981.9  319.97    4993  318.93  4995.7  318.43
    4999  318.93    5013  320.01  5018.6  321.76  5026.4  321.85  5080.7     325
  5125.9  326.18  5148.4   327.6    5154  327.52  5202.5  329.78  5265.6   331.8
#Mann= 6 ,-1 , 0
  4542.6     .05       0  4879.7     .12       0  4970.4      .1       0
    4993     .07       0    4999      .1       0  5202.5     .05       0
Bank Sta=4993,4999
XS Rating Curve= 0 ,0
Exp/Cntr=0.3,0.1

Type RM Length L Ch R = 1 ,2621    ,81,81,81
BEGIN DESCRIPTION:
UNT065 IN SUCR 5.2
END DESCRIPTION:
XS GIS Cut Line= 3
       2287817.3     13390077.33      2287970.95     13390533.06
      2288203.37     13390543.45
#Sta/Elev= 30
  4654.1  327.12  4727.5  326.25  4733.2  325.77  4748.6  325.64    4770  324.61
    4907  322.41  4922.1  321.54    4928  321.66  4947.8  320.25  4959.6  318.17
  4985.1  317.26    4997  317.26  4999.8  316.76    5003  317.26  5011.3  317.64
    5023  317.39  5033.5  317.65  5042.7  318.54    5048   318.3  5065.2  320.02
  5074.2   321.9  5105.7  321.89    5111  322.32  5134.4  322.66  5211.9   325.9
  5251.9  326.94  5261.9  327.59    5292  327.98    5312  329.07  5367.7  330.03
#Mann= 5 ,-1 , 0
  4654.1      .1       0    4907     .12       0  4947.8      .1       0
    4997     .07       0    5003      .1       0
Bank Sta=4997,5003
XS Rating Curve= 0 ,0
Exp/Cntr=0.3,0.1

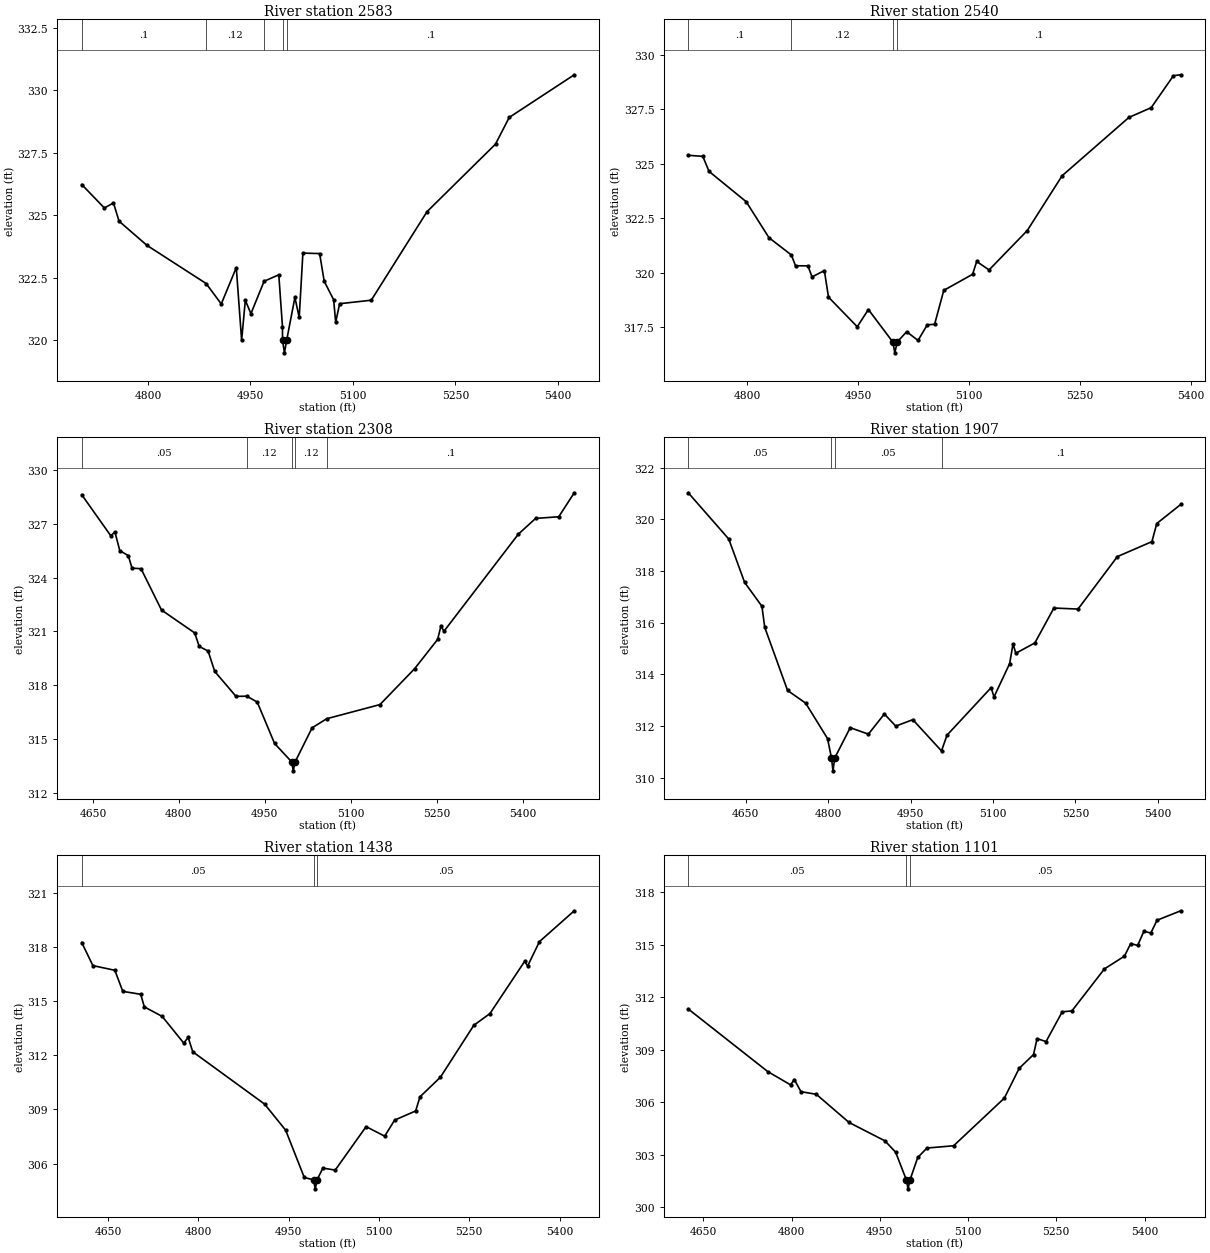
Type RM Length L Ch R = 1 ,2583    ,43,43,43
BEGIN DESCRIPTION:
UNT065 IN SUCR 5.1
END DESCRIPTION:
XS GIS Cut Line= 4
      2287786.87     13390145.99      2287919.66      13390487.1
      2287952.22     13390541.79      2288242.57     13390566.53
#Sta/Elev= 30
    4703  326.23  4736.1  325.29  4749.5  325.49  4757.6  324.76  4798.5  323.79
  4885.1  322.26  4907.3  321.44  4929.3   322.9  4937.1  319.98  4942.5  321.59
  4950.7  321.05    4970  322.35  4991.5  322.61  4996.9  320.53    4997  319.98
  4999.8  319.48    5003  319.98  5015.1   321.7  5021.4   320.9  5026.8  323.48
  5051.3  323.46    5058  322.35  5071.8  321.61  5074.8  320.71  5080.6  321.45
  5126.9  321.59  5208.5  325.14  5308.8  327.85  5328.9  328.92  5424.1  330.63
#Mann= 5 ,-1 , 0
    4703      .1       0  4885.1     .12       0    4970      .1       0
    4997     .07       0    5003      .1       0
Bank Sta=4997,5003
XS Rating Curve= 0 ,0
Exp/Cntr=0.3,0.1

Type RM Length L Ch R = 1 ,2540    ,676,676,676
BEGIN DESCRIPTION:
UNT065 IN SUCR 5.1
END DESCRIPTION:
XS GIS Cut Line= 3
      2287728.75     13390189.29      2287914.96      13390557.8
      2288167.59     13390581.24
#Sta/Elev= 30
  4720.2  325.39  4739.9  325.34  4748.3  324.65  4798.5  323.26  4829.5   321.6
  4859.7  320.81  4865.4  320.31  4882.1  320.31  4887.7   319.8  4904.4  320.09
    4910  318.87  4948.9  317.51    4964   318.3    4997  316.81  4999.8  316.31
    5003  316.81  5015.8  317.28  5031.2  316.88  5043.7   317.6  5053.6  317.62
    5066  319.18    5105  319.92  5110.6  320.51  5127.3  320.12    5179  321.93
  5226.2  324.45  5316.6  327.13  5346.8  327.58  5376.9  329.05  5386.8  329.09
#Mann= 4 ,-1 , 0
  4720.2      .1       0  4859.7     .12       0    4997     .07       0
    5003      .1       0
Bank Sta=4997,5003
XS Rating Curve= 0 ,0
Exp/Cntr=0.3,0.1

Type RM Length L Ch R = 1 ,2308    ,401,401,401
BEGIN DESCRIPTION:
UNT065 IN SUCR 5.0
END DESCRIPTION:
XS GIS Cut Line= 3
      2287387.71     13390396.85      2287826.42     13390655.46
      2288174.66     13390615.33
#Sta/Elev= 30
  4630.5  328.63  4681.2  326.34  4688.5  326.55  4696.9  325.51  4711.8  325.23
  4718.3  324.53    4734   324.5  4769.8  322.19  4827.8  320.91  4835.5  320.16
  4851.1   319.9  4862.7  318.76  4899.8  317.37  4918.7  317.38  4936.9  317.05
  4967.1  314.74    4997  313.71  4999.8  313.21    5003  313.71  5032.6  315.61
  5058.1  316.12  5151.1  316.91  5211.5  318.91  5251.8  320.55  5257.7  321.32
  5262.7     321  5392.7  326.43  5422.9  327.31  5463.2   327.4  5490.3  328.74
#Mann= 5 ,-1 , 0
  4630.5     .05       0  4918.7     .12       0    4997     .07       0
    5003     .12       0  5058.1      .1       0
Bank Sta=4997,5003
XS Rating Curve= 0 ,0
Exp/Cntr=0.3,0.1

Type RM Length L Ch R = 1 ,1907    ,469,469,469
BEGIN DESCRIPTION:
UNT065 IN SUCR 4.0
END DESCRIPTION:
XS GIS Cut Line= 4
      2287361.79     13390777.41      2287410.41     13390888.53
      2287972.91     13391041.31      2288160.37     13390999.65
#Sta/Elev= 30
  4545.5  321.03  4619.2  319.24  4648.1  317.56  4679.5  316.64  4684.7  315.82
  4726.2  313.38  4759.1  312.89  4798.9  311.52  4806.1  310.77  4808.8  310.27
  4812.1  310.77  4840.2  311.94  4873.3  311.69  4902.3  312.47  4923.1     312
  4954.1  312.25  5006.3  311.04  5016.3  311.65  5096.6  313.49  5101.8  313.13
  5130.3  314.42  5136.4  315.18  5141.6  314.82  5176.2  315.22  5210.8  316.57
  5254.7  316.53  5326.3  318.56  5389.2  319.14    5398  319.84  5441.7  320.58
#Mann= 4 ,-1 , 0
  4545.5     .05       0  4806.1     .03       0  4812.1     .05       0
  5006.3      .1       0
Bank Sta=4806.1,4812.1
XS Rating Curve= 0 ,0
Exp/Cntr=0.3,0.1

Type RM Length L Ch R = 1 ,1438    ,337,337,337
BEGIN DESCRIPTION:
UNT065 IN SUCR 3.0
END DESCRIPTION:
XS GIS Cut Line= 3
      2287236.81     13391131.61       2287361.8     13391312.15
      2287943.94     13391450.75
#Sta/Elev= 30
  4606.4  318.26  4624.9  316.98  4661.4  316.72  4674.6  315.55  4704.3  315.39
  4710.4  314.69  4740.1  314.16  4775.9  312.68  4783.1     313  4790.8   312.2
  4910.1   309.3  4945.1  307.85    4976  305.23  4991.4   305.1  4994.2   304.6
  4997.4   305.1  5006.8  305.75  5027.4  305.64  5078.7  308.05  5109.6  307.52
    5126  308.41    5161  308.92  5168.1   309.7  5202.1  310.79  5257.6  313.67
  5284.4  314.32  5341.9  317.21    5347  316.96  5366.6  318.31  5424.4  320.02
#Mann= 3 ,-1 , 0
  4606.4     .05       0  4991.4     .03       0  4997.4     .05       0
Bank Sta=4991.4,4997.4
XS Rating Curve= 0 ,0
Exp/Cntr=0.3,0.1

Type RM Length L Ch R = 1 ,1101    ,380,380,380
BEGIN DESCRIPTION:
UNT065 IN SUCR 2.0
END DESCRIPTION:
XS GIS Cut Line= 4
      2287174.29     13391430.18      2287257.63     13391603.81
       2287674.3     13391756.59      2287853.81     13391666.83
#Sta/Elev= 30
  4624.5  311.32  4759.5  307.75  4798.3  306.99  4804.8  307.29    4816   306.6
  4842.1  306.45  4897.8  304.84  4958.8  303.79    4977  303.14  4995.3  301.55
    4998  301.05  5001.3  301.55  5014.5  302.84  5030.2  303.38  5075.5  303.51
  5161.7  306.23  5186.9  307.93  5211.3  308.72  5217.4  309.63  5232.6  309.46
  5260.1  311.16  5276.5  311.21  5331.8  313.61  5365.9  314.34  5376.5  315.06
  5388.3  314.95  5398.9  315.76  5410.7  315.66  5421.2  316.39  5461.6  316.93
#Mann= 3 ,-1 , 0
  4624.5     .05       0  4995.3     .03       0  5001.3     .05       0
Bank Sta=4995.3,5001.3
XS Rating Curve= 0 ,0
Exp/Cntr=0.3,0.1

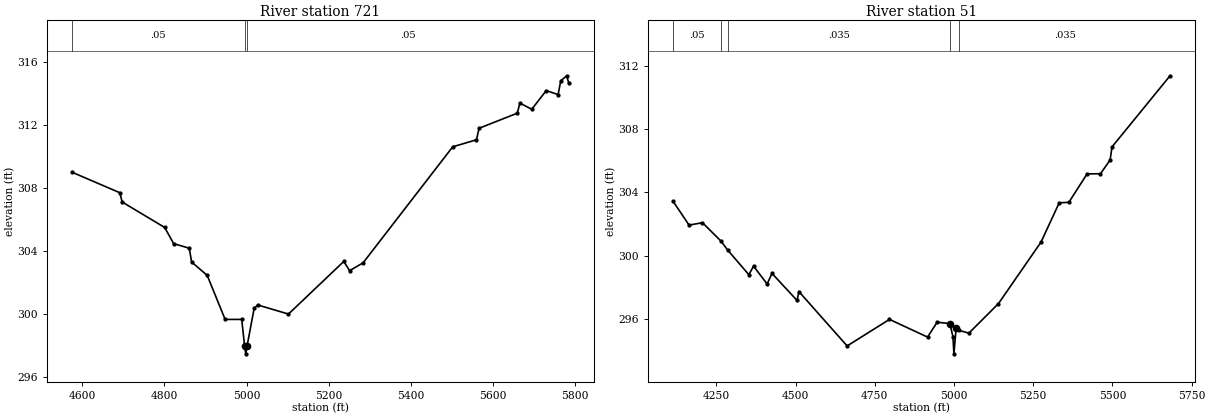
Type RM Length L Ch R = 1 ,721     ,670,670,670
BEGIN DESCRIPTION:
Mapping XS daec0c97
END DESCRIPTION:
XS GIS Cut Line= 4
      2287075.38     13391712.03       2287240.3     13392015.83
       2287596.2     13392067.91      2287994.15     13391756.47
#Sta/Elev= 30
  4574.4  309.01  4691.3   307.7    4697  307.11  4800.6  305.49  4822.4  304.46
  4860.5  304.17  4866.2  303.29  4904.2  302.44  4947.8  299.64  4988.2  299.64
  4995.3  297.95  4998.1  297.45  5001.3  297.95  5018.5  300.34  5027.2  300.56
  5102.1  299.98  5236.9  303.33    5251  302.74  5283.9  303.24  5502.2  310.62
  5560.1  311.07  5566.4   311.8  5659.5  312.76  5665.9   313.4  5694.8  313.01
  5730.1   314.2    5759  313.94  5765.4  314.82  5779.8  315.14  5785.1  314.66
#Mann= 3 ,-1 , 0
  4574.4     .05       0  4995.3    .035       0  5001.3     .05       0
Bank Sta=4995.3,5001.3
XS Rating Curve= 0 ,0
Exp/Cntr=0.3,0.1

Type RM Length L Ch R = 1 ,51      ,0,0,0
BEGIN DESCRIPTION:
UNT065 IN SUCR 1.0
END DESCRIPTION:
XS GIS Cut Line= 4
      2286914.54     13392181.34      2287218.34     13392667.42
      2287667.99     13392636.17      2288126.37     13392342.74
#Sta/Elev= 30
  4113.6  303.44  4164.1  301.93  4206.5  302.08  4264.2  300.93  4285.5  300.36
  4352.8  298.79  4367.7  299.33  4410.5   298.2  4425.9  298.87  4504.9  297.16
  4510.8  297.72  4662.9  294.28  4796.5  295.96  4916.7  294.84  4946.8  295.78
  4986.9   295.7  4996.9  294.86  4999.8  293.78    5007  295.43    5017  295.26
  5047.1  295.09  5140.4  296.96  5274.6  300.85  5332.1  303.34  5362.5  303.37
    5420  305.17  5462.3  305.18  5492.7  306.05  5498.7  306.88  5681.8  311.38
#Mann= 5 ,-1 , 0
  4113.6     .05       0  4264.2     .08       0  4285.5    .035       0
  4986.9     .03       0    5017    .035       0
Bank Sta=4986.9,5007
XS Rating Curve= 0 ,0
Exp/Cntr=0.3,0.1

Chan Stop Cuts=-1
Use User Specified Reach Order=0
Composite Channel Slope=5