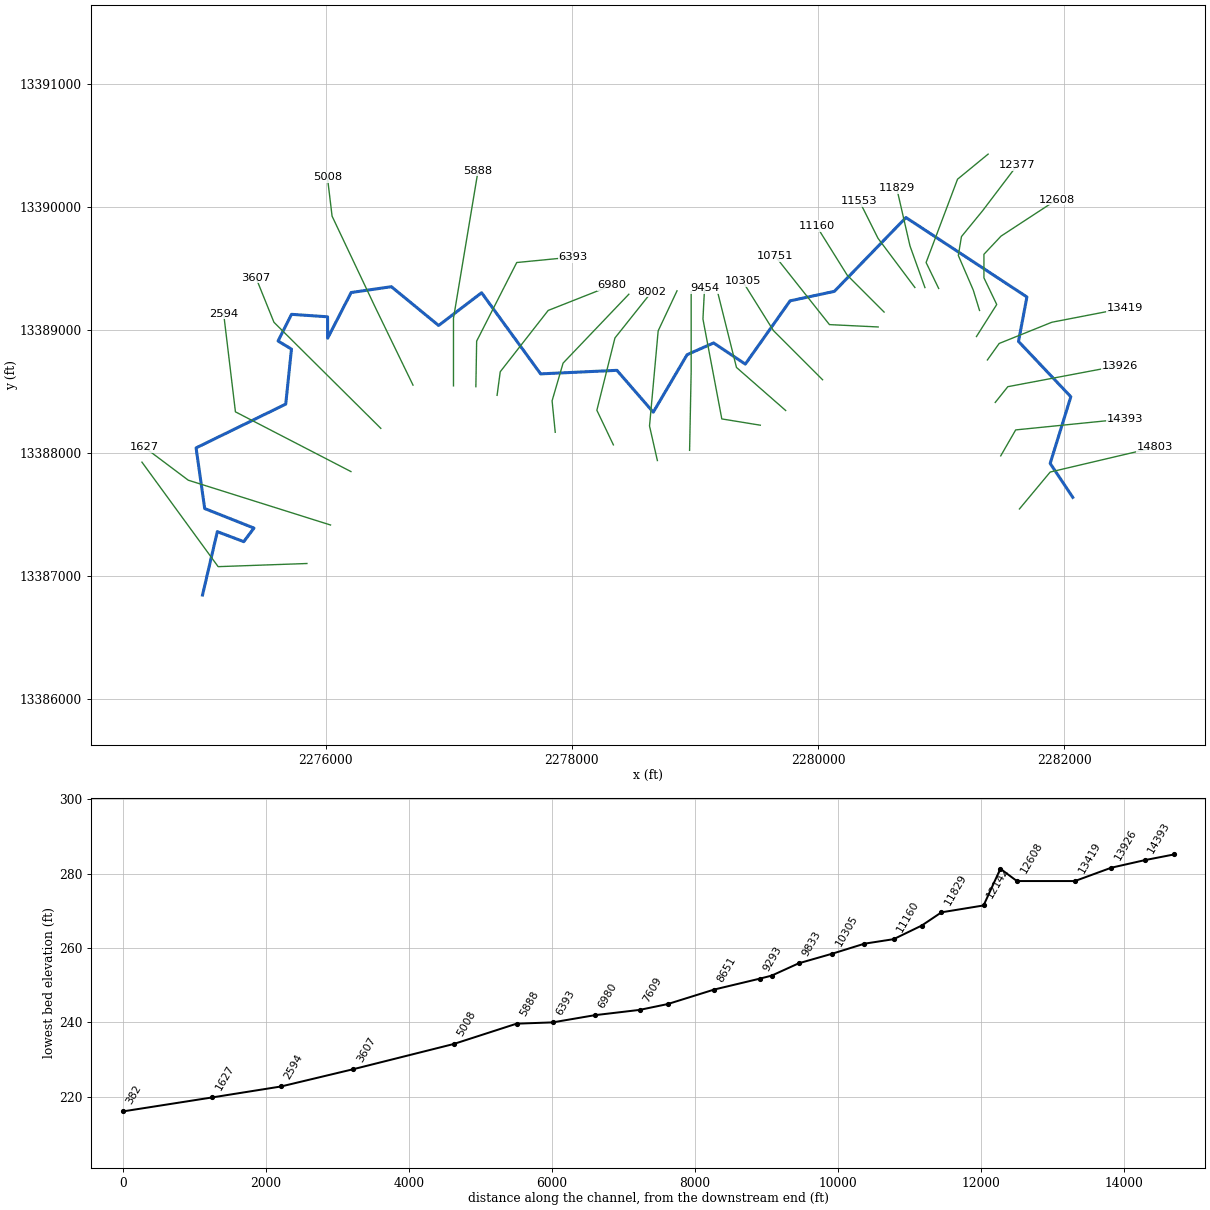
--- UNT066 IN SUCR.prj (project) ---

Proj Title=UNT066 IN SUCR Base Level Engineering
Current Plan=p01
Default Exp/Contr=0.3,0.1
English Units
Geom File=g01
Flow File=f01
Plan File=p01
Y Axis Title=Elevation
X Axis Title(PF)=Main Channel Distance
X Axis Title(XS)=Station
BEGIN DESCRIPTION:
UNT066 IN SUCR
END DESCRIPTION:
DSS Export Rating Curves= 0
DSS Export Rating Curve Sorted= 0
DSS Export Volume Flow Curves= 0
DXF OffsetX= 0
DXF OffsetY= 0
DXF ScaleX= 1
DXF ScaleY= 10

--- UNT066 IN SUCR.p01 (plan) ---

Plan Title=Multiple Run
Short Identifier=Multiple
Geom File=g01
Flow File=f01
Subcritical Flow
K Sum by GR= 0
Std Step Tol= 0.01
Critical Tol= 0.01
Num of Std Step Trials= 20
Max Error Tol= 0.3
Flow Tol Ratio= 0.001
Split Flow NTrial= 30
Split Flow Tol= 0.02
Split Flow Ratio= 0.02
Log Output Level= 0
Friction Slope Method= 1
Unsteady Friction Slope Method= 2
Unsteady Bridges Friction Slope Method= 1
Parabolic Critical Depth
Global Vel Dist=  1 , 1 , 1
Global Log Level= 0
CheckData=True
Encroach Param= -1, 0, 0, 0
BEGIN DESCRIPTION:
Multiple Run
END DESCRIPTION:

--- UNT066 IN SUCR.f01 (steady flow) ---

Flow Title=Multiple
Number of Profiles=7
Profile Names=10-year,25-year,50-year,1pct_min,100-year,1pct_plu,500-year
River Rch & RM= UNT066 IN SUCR,Reach-1,14803
     200     274     334     300     406     549     609
River Rch & RM= UNT066 IN SUCR,Reach-1,12608
     308     430     532     485     656     887    1009
River Rch & RM= UNT066 IN SUCR,Reach-1,5888
     404     572     715     657     888    1201    1391
River Rch & RM= UNT066 IN SUCR,Reach-1,2594
     409     579     723     664     898    1214    1404
Boundary for River Rch & Prof#=UNT066 IN SUCR,Reach-1,1
Up Type=0
Dn Type=3
Dn Slope=0.005
Boundary for River Rch & Prof#=UNT066 IN SUCR,Reach-1,2
Up Type=0
Dn Type=3
Dn Slope=0.005
Boundary for River Rch & Prof#=UNT066 IN SUCR,Reach-1,3
Up Type=0
Dn Type=3
Dn Slope=0.005
Boundary for River Rch & Prof#=UNT066 IN SUCR,Reach-1,4
Up Type=0
Dn Type=3
Dn Slope=0.005
Boundary for River Rch & Prof#=UNT066 IN SUCR,Reach-1,5
Up Type=0
Dn Type=3
Dn Slope=0.005
Boundary for River Rch & Prof#=UNT066 IN SUCR,Reach-1,6
Up Type=0
Dn Type=3
Dn Slope=0.005
Boundary for River Rch & Prof#=UNT066 IN SUCR,Reach-1,7
Up Type=0
Dn Type=3
Dn Slope=0.005

--- UNT066 IN SUCR.g01 (geometry) ---

Geom Title=Existing Conditions
Program Version=4.10

River Reach=UNT066 IN SUCR  ,Reach-1
Reach XY= 30
       2282071.1     13387641.07      2281887.46     13387916.79
      2282055.39     13388458.69        2281630.     13388908.39
       2281698.4      13389269.5      2280715.24     13389915.08
      2280133.36     13389315.11      2279773.31     13389237.99
      2279409.79       13388724.      2279152.09     13388895.77
      2278936.71     13388800.77      2278661.43     13388332.99
      2278366.03     13388673.42       2277745.9     13388644.46
      2277266.09     13389303.87      2276916.99     13389037.91
      2276532.88     13389353.07       2276205.8     13389305.53
       2276014.7      13388934.3      2276014.26     13389108.38
       2275721.2     13389128.49      2275611.87     13388911.47
      2275720.78     13388845.95      2275674.19     13388398.85
      2274945.74     13388043.02      2275015.38     13387550.25
      2275415.74     13387391.51      2275332.94     13387280.95
      2275118.23     13387362.49      2274997.72     13386846.86

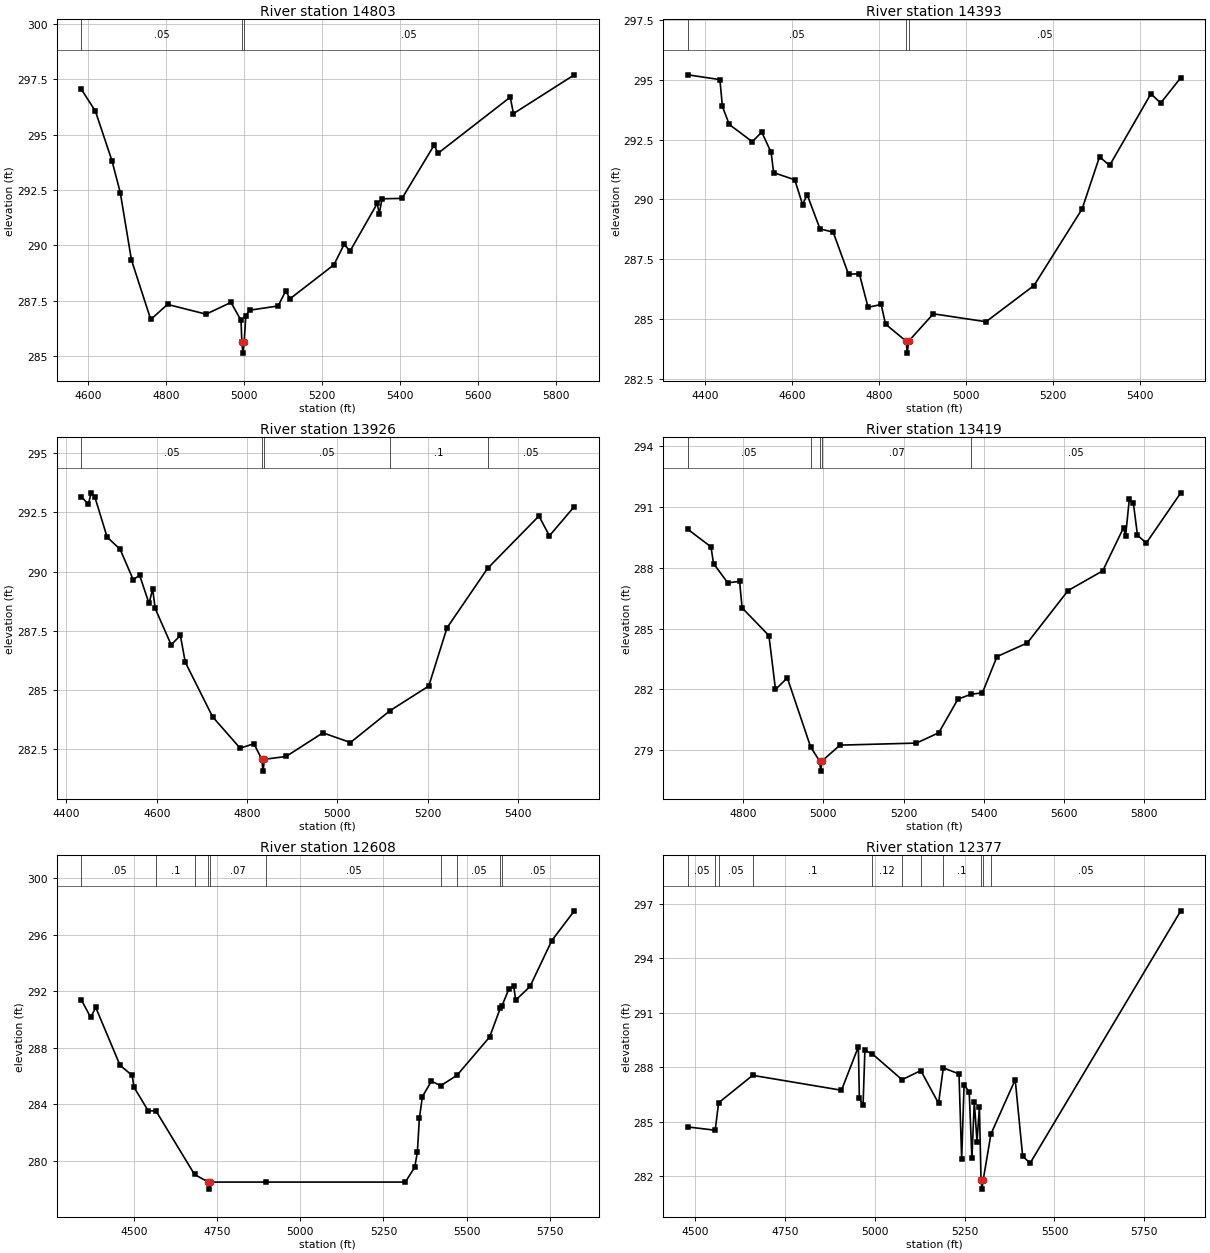
Type RM Length L Ch R = 1 ,14803   ,410,410,410
BEGIN DESCRIPTION:
UNT066 IN SUCR 23.0
END DESCRIPTION:
XS GIS Cut Line= 3
      2281637.71     13387546.84      2281887.72     13387846.85
      2282737.67     13388046.84
#Sta/Elev= 30
  4582.9  297.04  4618.7  296.06    4661  293.83  4682.5  292.38  4711.1  289.34
  4760.6  286.65  4803.6  287.33  4902.5  286.89  4966.3  287.42  4992.1  286.61
  4994.2  285.63  4996.9  285.13  5000.2  285.63  5004.3  286.82  5014.5  287.07
  5087.1  287.26    5107  287.95  5117.3  287.58  5230.3  289.12  5256.6  290.05
  5271.4  289.73  5341.3  291.89  5346.5  291.41  5353.5   292.1  5404.9  292.12
  5487.1  294.52  5497.4  294.16  5682.3  296.69  5690.6  295.95  5846.6   297.7
#Mann= 3 ,-1 , 0
  4582.9     .05       0  4994.2     .03       0  5000.2     .05       0
Bank Sta=4994.2,5000.2
XS Rating Curve= 0 ,0
Exp/Cntr=0.3,0.1

Type RM Length L Ch R = 1 ,14393   ,467,467,467
BEGIN DESCRIPTION:
UNT066 IN SUCR 22.0
END DESCRIPTION:
XS GIS Cut Line= 3
      2281485.74     13387978.39       2281607.1     13388189.16
       2282493.8     13388278.47
#Sta/Elev= 30
  4360.4   295.2  4434.1     295  4439.8  293.88  4455.6  293.13  4508.6  292.41
  4530.3  292.81  4551.9  291.97  4557.7  291.12  4606.4  290.82  4624.3  289.79
  4634.9   290.2  4664.5  288.77  4694.7  288.64  4730.1  286.88    4755   286.9
  4775.1   285.5  4805.2  285.62  4815.3   284.8  4862.6  284.09  4865.3  283.59
  4868.6  284.09  4925.3  285.23  5046.5   284.9    5157  286.41  5267.6   289.6
  5307.8  291.78    5331  291.42  5426.1  294.41  5448.5  294.02  5494.8  295.08
#Mann= 3 ,-1 , 0
  4360.4     .05       0  4862.6     .03       0  4868.6     .05       0
Bank Sta=4862.6,4868.6
XS Rating Curve= 0 ,0
Exp/Cntr=0.3,0.1

Type RM Length L Ch R = 1 ,13926   ,507,507,507
BEGIN DESCRIPTION:
UNT066 IN SUCR 21.0
END DESCRIPTION:
XS GIS Cut Line= 3
      2281441.04     13388412.68      2281543.23     13388540.42
      2282454.65      13388712.5
#Sta/Elev= 30
  4433.4  293.17  4448.6  292.84    4455  293.33    4463  293.16  4490.2  291.46
  4519.1  290.94  4547.9  289.66  4562.3  289.84  4583.1  288.65  4591.1  289.26
  4596.6  288.44  4632.1   286.9  4652.4   287.3  4663.2  286.17  4723.7  283.86
  4784.7  282.53  4815.3  282.72  4832.6  282.06  4835.4  281.56  4838.6  282.06
  4886.5  282.18  4967.9  283.18    5029  282.77  5116.8  284.12  5202.3  285.16
  5242.7  287.62  5332.4  290.13  5446.2  292.35  5469.4  291.51  5524.5  292.75
#Mann= 5 ,-1 , 0
  4433.4     .05       0  4832.6     .03       0  4838.6     .05       0
  5116.8      .1       0  5332.4     .05       0
Bank Sta=4832.6,4838.6
XS Rating Curve= 0 ,0
Exp/Cntr=0.3,0.1

Type RM Length L Ch R = 1 ,13419   ,811,811,811
BEGIN DESCRIPTION:
UNT066 IN SUCR 20.0
END DESCRIPTION:
XS GIS Cut Line= 4
      2281377.21     13388757.59      2281472.98     13388891.67
      2281900.87      13389064.1      2282493.77     13389178.86
#Sta/Elev= 30
  4661.9  289.88  4719.6  289.02  4725.8   288.2  4761.4  287.25  4790.9  287.32
  4797.1  286.02  4864.1  284.65  4880.5     282    4910  282.57  4968.2  279.17
  4990.5  278.48  4993.2  277.98  4996.5  278.48  5041.6  279.26  5232.3  279.36
    5288  279.87  5335.7  281.52  5369.3  281.77  5396.8  281.83  5433.3  283.62
  5508.9  284.29  5610.7  286.87  5697.2  287.84    5749  289.96  5754.1  289.54
  5763.5  291.37  5773.7  291.16  5783.9  289.59  5805.9  289.21  5891.9  291.68
#Mann= 5 ,-1 , 0
  4661.9     .05       0  4968.2     .07       0  4990.5     .07       0
  4996.5     .07       0  5369.3     .05       0
Bank Sta=4990.5,4996.5
XS Rating Curve= 0 ,0
Exp/Cntr=0.3,0.1

Type RM Length L Ch R = 1 ,12608   ,231,231,231
BEGIN DESCRIPTION:
UNT066 IN SUCR 19.0
END DESCRIPTION:
XS GIS Cut Line= 6
      2281288.18     13388947.86      2281453.12     13389208.28
      2281348.95      13389425.3      2281348.95     13389616.27
      2281487.84     13389763.84      2281939.21     13390058.97
#Sta/Elev= 30
  4341.9  291.38  4369.7  290.15    4385  290.85  4457.8  286.76  4494.3  286.04
  4500.2  285.19  4542.6  283.53  4566.1  283.52  4681.9  279.02  4723.2  278.48
    4726  277.98  4729.2  278.48  4897.2  278.48  5315.8  278.48  5344.1  279.54
    5352  280.61    5358  283.01  5367.1  284.54  5394.2  285.63  5422.2  285.31
  5470.8  286.04  5569.2  288.76  5600.9  290.78  5606.8  290.99  5626.5  292.13
  5641.6  292.37  5647.6  291.37  5690.6  292.34  5756.1  295.59  5823.8   297.7
#Mann= 10 ,-1 , 0
  4341.9     .05       0  4566.1      .1       0  4681.9     .07       0
  4723.2    .033       0  4729.2     .07       0  4897.2     .05       0
  5422.2     .08       0  5470.8     .05       0  5600.9     .08       0
  5606.8     .05       0
Bank Sta=4723.2,4729.2
XS Rating Curve= 0 ,0
Exp/Cntr=0.3,0.1

Type RM Length L Ch R = 1 ,12377   ,235,235,235
BEGIN DESCRIPTION:
UNT066 IN SUCR 18.0
END DESCRIPTION:
XS GIS Cut Line= 6
      2281313.34     13389159.85      2281262.23     13389325.94
      2281140.89     13389606.95      2281166.44     13389760.22
      2281338.87     13389970.97      2281619.88      13390341.4
#Sta/Elev= 30
  4478.9  284.71  4554.9  284.53  4564.4  286.04  4659.3  287.55  4906.7  286.73
  4953.7  289.12  4956.5  286.28  4966.8  285.91  4971.9  288.92    4992  288.74
  5075.4  287.31  5127.7  287.81  5177.1  286.01  5190.3  287.96    5234  287.63
  5241.5  282.94  5248.2  287.03  5262.5  286.63    5270     283  5276.7   286.1
  5284.2   283.9  5290.9  285.81  5295.4  281.79  5298.1  281.29  5301.4  281.79
    5323  284.32  5390.6  287.31  5411.4   283.1  5432.2  282.72  5851.8   296.6
#Mann= 11 ,-1 , 0
  4478.9     .05       0  4554.9      .1       0  4564.4     .05       0
  4659.3      .1       0    4992     .12       0  5075.4      .1       0
  5127.7     .12       0  5190.3      .1       0  5295.4     .07       0
  5301.4      .1       0    5323     .05       0
Bank Sta=5295.4,5301.4
XS Rating Curve= 0 ,0
Exp/Cntr=0.3,0.1

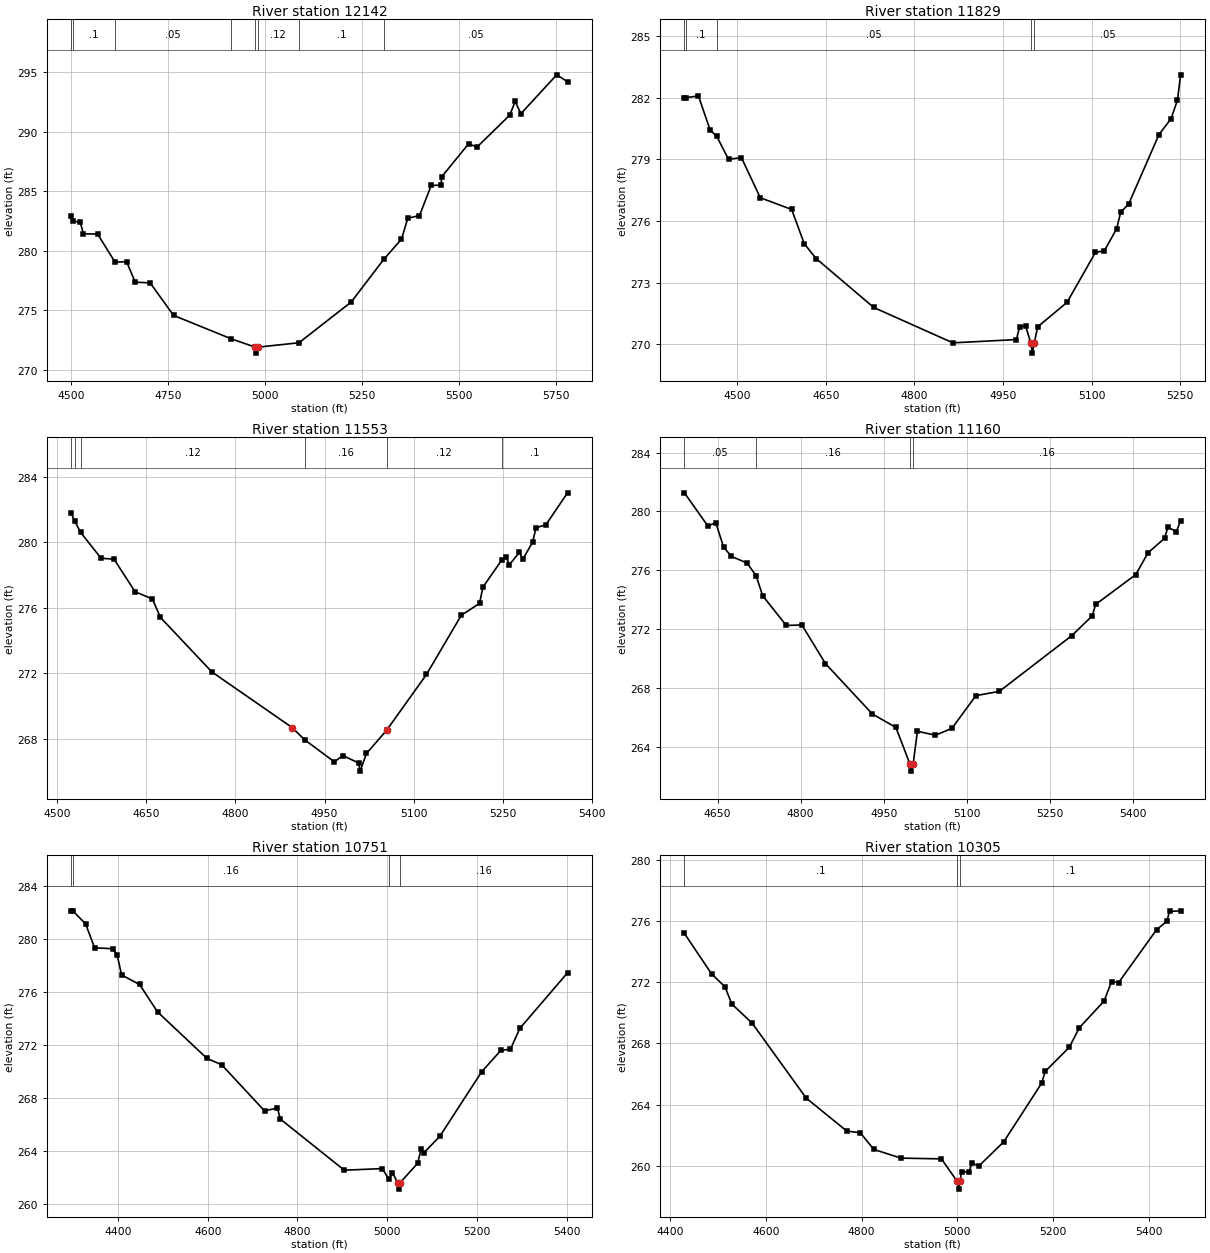
Type RM Length L Ch R = 1 ,12142   ,589,589,589
BEGIN DESCRIPTION:
UNT066 IN SUCR 17.0
END DESCRIPTION:
XS GIS Cut Line= 4
      2280981.22     13389338.73      2280879.05     13389549.47
       2281134.5     13390226.43      2281383.16     13390430.45
#Sta/Elev= 30
  4500.3  282.95  4505.5  282.48  4522.9  282.44  4531.6  281.44    4568  281.42
  4612.9  279.06  4642.7   279.1  4664.9  277.38  4703.5  277.32  4763.8  274.59
  4911.9  272.63  4974.5  271.92  4977.3  271.42  4980.5  271.92  5087.3  272.29
  5222.2  275.72    5306   279.3  5351.6  280.99  5367.8  282.75    5398  282.97
  5428.2   285.5  5453.1  285.53  5455.6  286.24    5525  289.01  5545.9  288.71
  5630.6   291.4  5644.9  292.56  5659.3  291.52  5751.8  294.79  5779.7  294.21
#Mann= 8 ,-1 , 0
  4500.3     .05       0  4505.5      .1       0  4612.9     .05       0
  4911.9     .12       0  4974.5     .07       0  4980.5     .12       0
  5087.3      .1       0    5306     .05       0
Bank Sta=4974.5,4980.5
XS Rating Curve= 0 ,0
Exp/Cntr=0.3,0.1

Type RM Length L Ch R = 1 ,11829   ,276,276,276
BEGIN DESCRIPTION:
UNT066 IN SUCR 16.1
END DESCRIPTION:
XS GIS Cut Line= 3
      2280869.51     13389346.03      2280747.97      13389684.6
      2280640.51     13390152.59
#Sta/Elev= 30
  4410.8     282  4412.7     282  4434.6  282.08  4454.2  280.43  4465.5  280.12
  4485.4     279  4507.3  279.08  4539.2  277.13  4592.3  276.56  4613.7  274.89
  4633.8  274.17  4731.3  271.79  4865.2  270.07  4972.8  270.23    4978  270.84
  4988.3  270.89    4997  270.07  4999.8  269.57    5003  270.07  5008.8  270.85
  5058.5  272.04  5106.5  274.47  5121.7  274.55  5142.2  275.61  5149.4  276.43
  5162.7  276.82    5214   280.2  5234.6  280.98  5245.4  281.88  5250.7  283.11
#Mann= 5 ,-1 , 0
  4410.8     .05       0  4412.7      .1       0  4465.5     .05       0
    4997    .035       0    5003     .05       0
Bank Sta=4997,5003
XS Rating Curve= 0 ,0
Exp/Cntr=0.3,0.1

Type RM Length L Ch R = 1 ,11553   ,393,393,393
BEGIN DESCRIPTION:
UNT066 IN SUCR 16.0
END DESCRIPTION:
XS GIS Cut Line= 3
      2280787.74     13389346.83      2280487.72     13389746.85
      2280337.74     13390046.82
#Sta/Elev= 30
  4523.7  281.77  4529.2  281.31  4539.3  280.61  4573.7  279.03  4595.6  278.97
    4631  276.98  4660.2  276.54  4673.7  275.41  4760.2  272.08  4895.6  268.67
  4916.4  267.93  4966.4  266.58    4981  266.96  5007.2  266.51  5009.9  266.01
  5020.6  267.09  5054.5  268.51  5121.6  271.92  5180.2  275.54    5211  276.27
  5216.6  277.26    5248   278.9  5255.7  279.12  5261.3  278.63  5278.1   279.4
  5283.7  278.96  5300.4  280.02    5306  280.89  5322.8  281.08  5359.1  283.03
#Mann= 6 ,-1 , 0
  4523.7     .05       0  4529.2      .1       0  4539.3     .12       0
  4916.4     .16       0  5054.5     .12       0    5248      .1       0
Bank Sta=4895.6,5054.5
XS Rating Curve= 0 ,0
Exp/Cntr=0.3,0.1

Type RM Length L Ch R = 1 ,11160   ,409,409,409
BEGIN DESCRIPTION:
UNT066 IN SUCR 15.0
END DESCRIPTION:
XS GIS Cut Line= 3
      2280537.72     13389146.85      2280237.72     13389446.85
       2279987.7     13389846.88
#Sta/Elev= 30
  4590.2  281.26  4632.6     279  4646.8  279.24  4660.9  277.57  4675.1  276.94
  4703.3  276.49  4719.6  275.63  4731.6  274.26  4774.1  272.25  4802.3  272.28
  4844.8  269.66  4929.6  266.23    4972  265.32  4997.3  262.85  5000.1  262.35
  5003.3  262.85  5010.9  265.06  5043.4  264.79  5073.4  265.26  5116.5  267.48
  5158.9  267.77  5289.8  271.56  5326.4  272.89  5332.9  273.68  5405.4  275.71
  5427.2  277.18  5457.3  278.17  5463.2  278.93  5478.5  278.62  5486.2  279.37
#Mann= 4 ,-1 , 0
  4590.2     .05       0  4719.6     .16       0  4997.3     .12       0
  5003.3     .16       0
Bank Sta=4997.3,5003.3
XS Rating Curve= 0 ,0
Exp/Cntr=0.3,0.1

Type RM Length L Ch R = 1 ,10751   ,446,446,446
BEGIN DESCRIPTION:
UNT066 IN SUCR 14.0
END DESCRIPTION:
XS GIS Cut Line= 3
       2280489.5     13389025.78      2280093.52     13389044.94
      2279652.86     13389600.56
#Sta/Elev= 30
  4296.2  282.14  4299.4  282.14    4328  281.15    4348  279.35  4388.1  279.28
  4398.1  278.84  4408.1   277.3  4448.2  276.58  4488.2  274.51  4598.3     271
  4631.1  270.52  4726.6  267.04  4755.4  267.25  4761.8  266.42  4904.4  262.56
  4989.3  262.68  5003.7  261.86  5011.8  262.36  5023.2  261.63    5026  261.13
  5029.2  261.63  5067.8  263.08  5075.9  264.18  5082.3  263.89  5117.5  265.13
  5210.5  269.99  5253.7  271.62  5274.5  271.68  5295.4  273.26  5401.8  277.46
#Mann= 4 ,-1 , 0
  4296.2     .05       0  4299.4     .16       0  5003.7     .12       0
  5029.2     .16       0
Bank Sta=5023.2,5029.2
XS Rating Curve= 0 ,0
Exp/Cntr=0.3,0.1

Type RM Length L Ch R = 1 ,10305   ,472,472,472
BEGIN DESCRIPTION:
UNT066 IN SUCR 13.0
END DESCRIPTION:
XS GIS Cut Line= 3
      2280037.75     13388596.83      2279637.72     13388996.85
      2279387.73     13389396.83
#Sta/Elev= 30
  4429.6   275.2  4486.2  272.56  4514.5   271.7  4528.6  270.58  4571.1  269.33
  4684.2  264.42  4769.1  262.26  4797.3  262.15  4825.6  261.06  4882.2  260.49
    4967  260.44    5000  258.96  5002.7  258.46    5006  258.96  5008.9  259.59
  5024.2  259.59  5030.7  260.15  5045.4  259.98  5097.3  261.56  5176.3  265.39
    5184  266.17  5234.1  267.74  5255.4  269.03  5307.2  270.78  5322.6  272.05
  5337.3  271.98  5416.9  275.45  5438.1  275.99    5444  276.64    5467  276.68
#Mann= 3 ,-1 , 0
  4429.6      .1       0    5000     .07       0    5006      .1       0
Bank Sta=5000,5006
XS Rating Curve= 0 ,0
Exp/Cntr=0.3,0.1

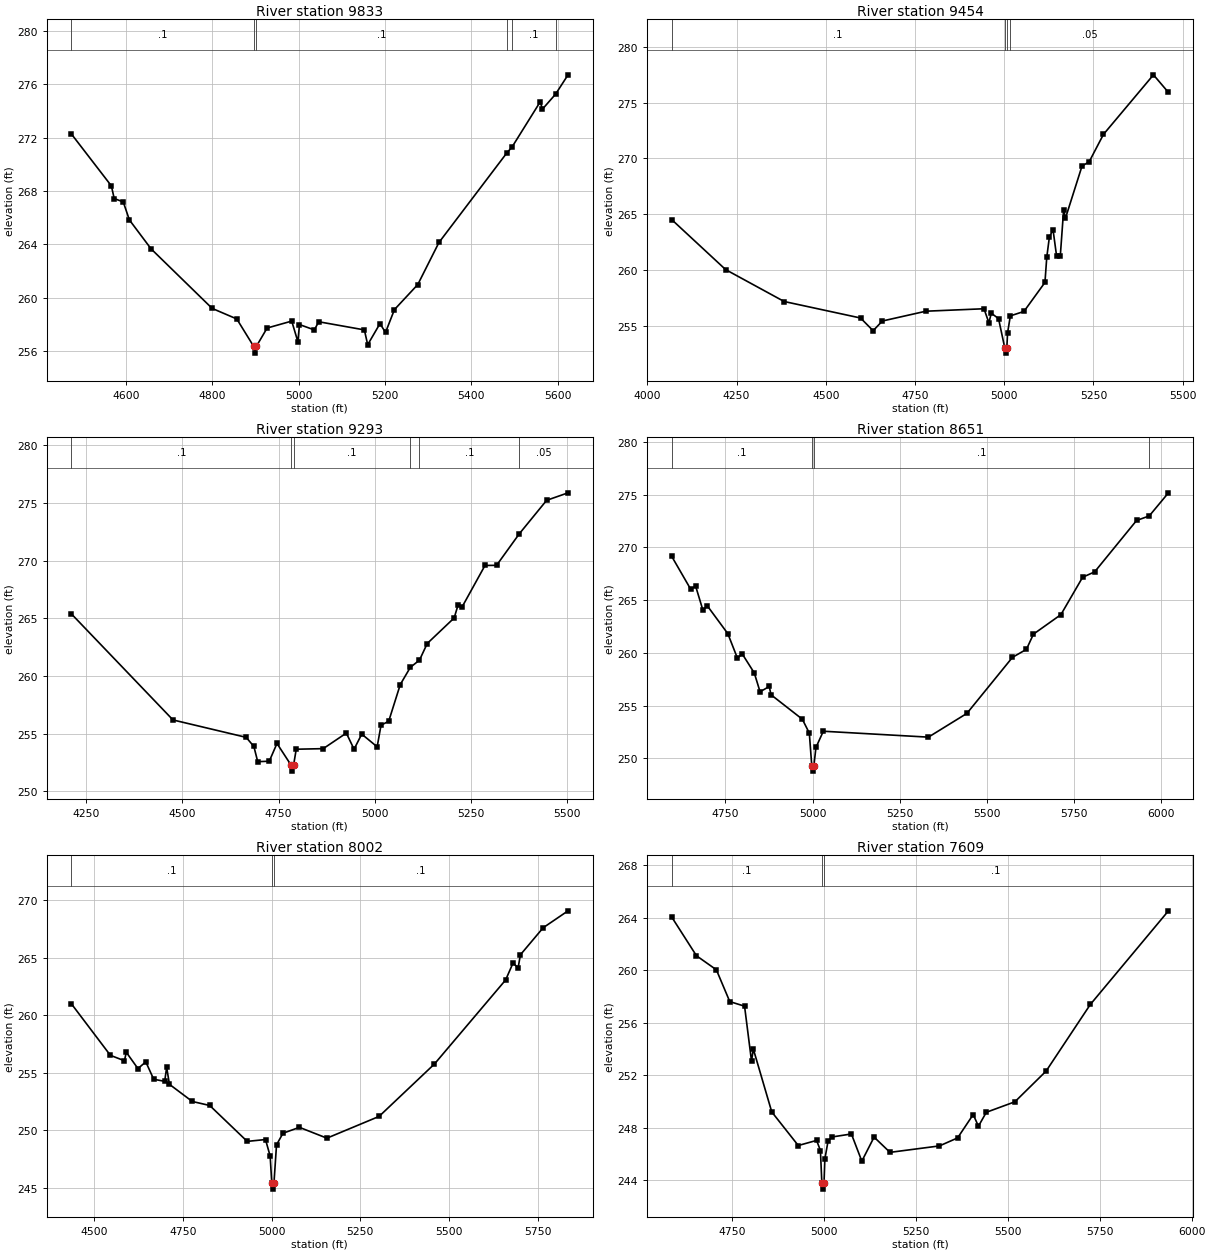
Type RM Length L Ch R = 1 ,9833    ,379,379,379
BEGIN DESCRIPTION:
UNT066 IN SUCR 12.0
END DESCRIPTION:
XS GIS Cut Line= 3
      2279737.74     13388346.84      2279337.72     13388696.85
      2279187.72     13389296.86
#Sta/Elev= 30
  4474.1  272.28  4566.7  268.39  4573.3  267.44  4594.2  267.19  4608.4  265.84
  4658.7  263.67  4800.1  259.21  4857.1  258.42  4896.3  256.36  4899.1  255.86
  4902.3  256.36  4927.3  257.74  4984.3  258.26  4998.5  256.72  5002.3     258
  5036.6   257.6  5046.9  258.21  5152.5   257.6  5160.2  256.49  5188.6  258.07
  5201.5  257.41  5222.1  259.12  5276.2     261  5325.2  264.15  5483.1  270.89
  5494.2  271.29  5559.7  274.69  5564.8  274.14  5595.2  275.26  5624.1  276.71
#Mann= 6 ,-1 , 0
  4474.1      .1       0  4896.3     .07       0  4902.3      .1       0
  5483.1     .05       0  5494.2      .1       0  5595.2     .05       0
Bank Sta=4896.3,4902.3
XS Rating Curve= 0 ,0
Exp/Cntr=0.3,0.1

Type RM Length L Ch R = 1 ,9454    ,161,161,161
BEGIN DESCRIPTION:
UNT066 IN SUCR 11.0
END DESCRIPTION:
XS GIS Cut Line= 4
      2279531.48     13388227.49      2279218.58     13388278.57
      2279065.31     13389089.65      2279078.08     13389338.75
#Sta/Elev= 30
  4068.3  264.51  4219.3  260.03  4383.2  257.17  4597.3  255.69  4632.6  254.55
  4658.4  255.42  4780.5   256.3  4943.3  256.52    4957  255.26  4963.7  256.12
    4984  255.64  5001.3  253.04    5004  252.54  5007.3  253.04  5009.4  254.36
  5017.1  255.88  5055.3  256.28  5114.1  258.88  5119.2  261.14  5126.5  262.94
  5136.7  263.62  5146.9  261.21    5157  261.21  5166.5  265.41  5171.6  264.64
    5218  269.32    5238   269.7  5278.1  272.16  5418.2   277.5  5460.2  275.92
#Mann= 4 ,-1 , 0
  4068.3      .1       0  5001.3     .07       0  5007.3      .1       0
  5017.1     .05       0
Bank Sta=5001.3,5007.3
XS Rating Curve= 0 ,0
Exp/Cntr=0.3,0.1

Type RM Length L Ch R = 1 ,9293    ,642,642,642
BEGIN DESCRIPTION:
Mapping XS 0cd7ab71
END DESCRIPTION:
XS GIS Cut Line= 3
      2278956.74     13388023.13      2278969.51     13388661.76
      2278969.51      13389312.5
#Sta/Elev= 30
  4212.2  265.39    4476  256.19    4666  254.68    4686  253.89    4696  252.57
    4726  252.61    4746  254.15    4783  252.25  4785.8  251.75    4789  252.25
    4796  253.65  4866.1   253.7  4926.1  255.05  4946.1  253.65  4966.1  254.96
  5006.1  253.86  5016.1  255.73  5036.1  256.08  5066.1  259.26  5092.2  260.75
    5116  261.38  5136.1  262.82  5206.1  265.04  5216.1  266.16  5226.1  265.96
  5286.1  269.59  5316.1   269.6  5375.2  272.34  5446.1  275.24  5501.7  275.89
#Mann= 6 ,-1 , 0
  4212.2      .1       0    4783     .07       0    4789      .1       0
  5092.2     .05       0    5116      .1       0  5375.2     .05       0
Bank Sta=4783,4789
XS Rating Curve= 0 ,0
Exp/Cntr=0.3,0.1

Type RM Length L Ch R = 1 ,8651    ,649,649,649
BEGIN DESCRIPTION:
UNT066 IN SUCR 10.0
END DESCRIPTION:
XS GIS Cut Line= 4
       2278694.9     13387940.08      2278631.03     13388221.09
      2278701.28     13388993.85      2278854.56     13389319.56
#Sta/Elev= 30
  4596.1  269.14  4650.1  266.05  4664.6  266.32  4685.1  264.08  4698.3  264.45
  4756.9  261.82  4784.5  259.49  4797.9  259.92  4832.7   258.1  4849.2  256.32
  4875.7  256.82  4880.5  256.04  4970.4  253.72  4990.5   252.4  4997.5   249.3
  5000.3   248.8  5003.5   249.3  5009.5  251.04  5030.6  252.58  5331.9  252.02
  5442.3  254.27  5572.9  259.58    5613  260.34  5633.1  261.78  5711.9  263.63
  5774.1  267.17  5808.6  267.68  5928.8  272.55  5965.1  272.98  6020.2  275.17
#Mann= 4 ,-1 , 0
  4596.1      .1       0  4997.5     .07       0  5003.5      .1       0
  5965.1     .05       0
Bank Sta=4997.5,5003.5
XS Rating Curve= 0 ,0
Exp/Cntr=0.3,0.1

Type RM Length L Ch R = 1 ,8002    ,393,393,393
BEGIN DESCRIPTION:
UNT066 IN SUCR 9.0
END DESCRIPTION:
XS GIS Cut Line= 4
      2278337.27     13388067.79      2278203.14     13388348.82
      2278350.03     13388936.37      2278649.65     13389312.49
#Sta/Elev= 30
  4436.7  261.01  4546.5  256.53  4585.9  256.06  4591.4  256.79    4624  255.38
  4646.2  255.96  4668.4  254.45  4699.3  254.27  4704.9  255.48  4712.7  254.01
    4777  252.52  4826.1  252.17  4931.6  249.05  4983.1  249.21  4996.2  247.77
  5000.8   245.4  5003.5   244.9  5006.8   245.4  5014.1  248.75  5032.3  249.76
  5078.6  250.27  5155.9  249.33  5302.7  251.22  5458.7  255.78  5658.9  263.08
  5679.7  264.55  5694.1  264.14  5700.5  265.27  5764.6  267.62  5834.6  269.09
#Mann= 3 ,-1 , 0
  4436.7      .1       0  5000.8     .07       0  5006.8      .1       0
Bank Sta=5000.8,5006.8
XS Rating Curve= 0 ,0
Exp/Cntr=0.3,0.1

Type RM Length L Ch R = 1 ,7609    ,629,629,629
BEGIN DESCRIPTION:
UNT066 IN SUCR 8.0
END DESCRIPTION:
XS GIS Cut Line= 4
      2277864.66     13388170.04      2277839.12     13388425.46
      2277928.53     13388732.01      2278462.81     13389291.73
#Sta/Elev= 30
  4587.1  264.04  4654.2   261.1  4708.3  260.03  4744.7  257.61  4784.9  257.26
  4803.8  253.08  4808.8  253.99  4858.8  249.21  4930.9  246.65  4980.7  247.04
  4991.1  246.27  4994.9  243.83  4997.6  243.33  5000.9  243.83  5003.1  245.62
  5011.9     247  5022.3   247.3  5075.3  247.53  5103.6  245.46  5136.9  247.29
  5180.2  246.13  5314.5  246.62  5363.9  247.23  5406.3  249.01  5420.5  248.12
  5441.9  249.18  5519.6  249.98  5604.5  252.32  5724.6  257.39  5936.9  264.52
#Mann= 3 ,-1 , 0
  4587.1      .1       0  4994.9     .07       0  5000.9      .1       0
Bank Sta=4994.9,5000.9
XS Rating Curve= 0 ,0
Exp/Cntr=0.3,0.1

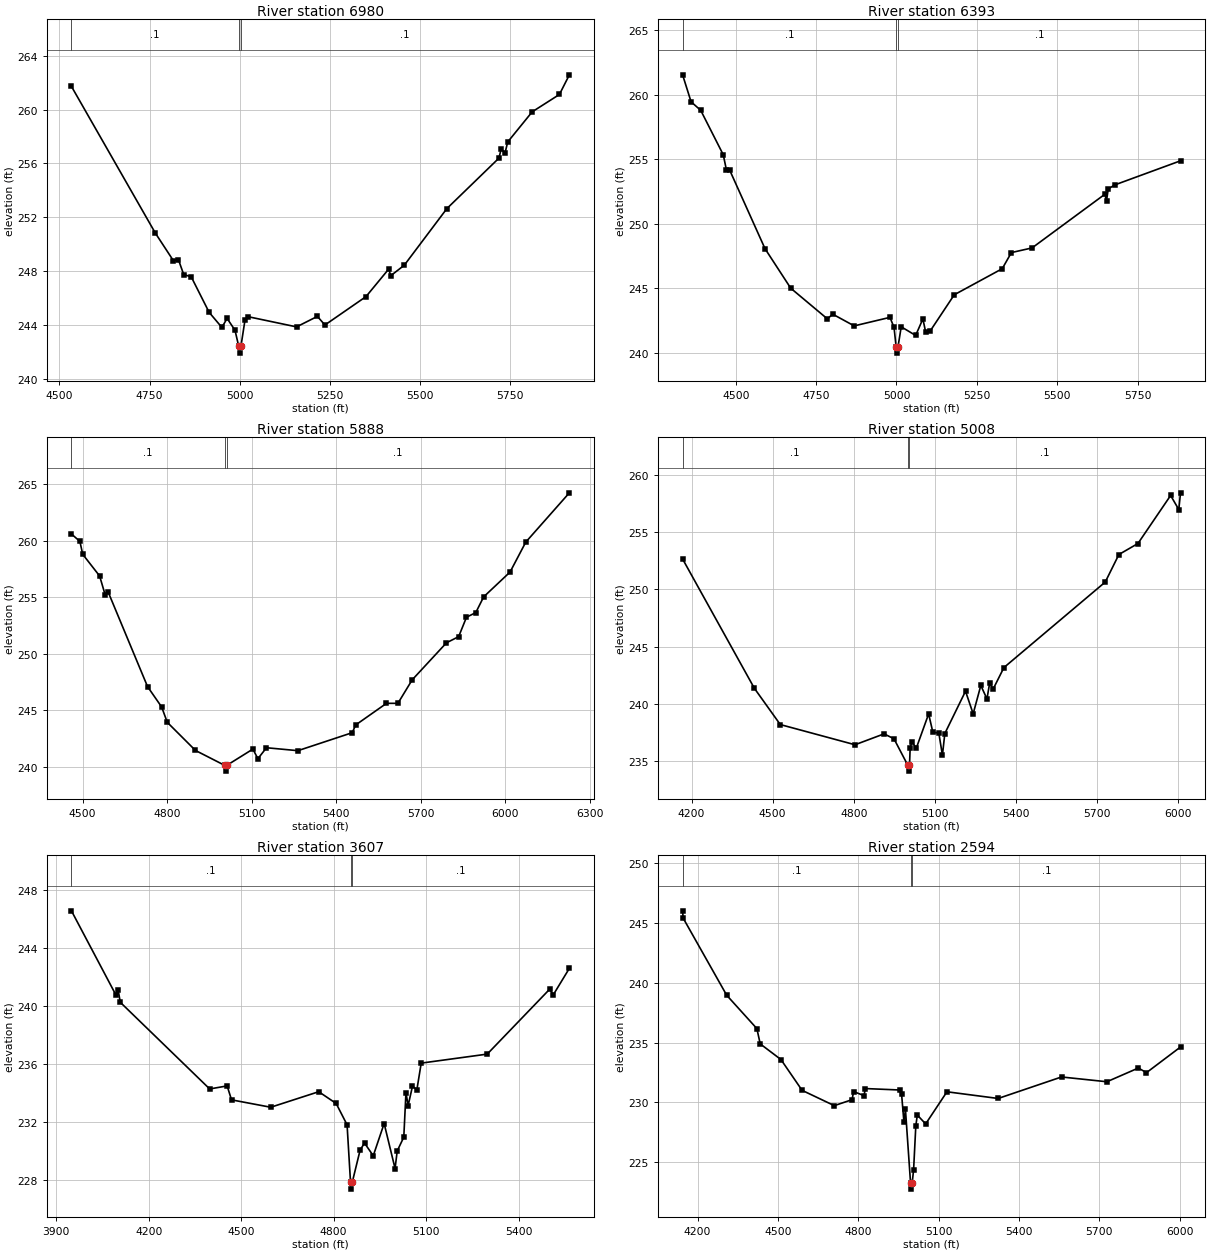
Type RM Length L Ch R = 1 ,6980    ,587,587,587
BEGIN DESCRIPTION:
UNT066 IN SUCR 7.0
END DESCRIPTION:
XS GIS Cut Line= 4
      2277392.07     13388470.21      2277417.61     13388661.76
      2277807.18      13389159.9      2278323.62     13389363.92
#Sta/Elev= 30
  4533.2  261.72  4765.9  250.82  4815.7  248.78  4830.1  248.83  4844.6  247.74
  4865.4  247.57  4915.1  244.93  4950.4  243.81  4964.9  244.48  4986.8   243.6
  4997.2   242.4  4999.9   241.9  5003.2   242.4  5014.6  244.37  5022.7  244.61
  5157.5  243.85  5215.3  244.63  5236.2  243.99  5350.1   246.1  5413.2  248.15
  5418.6  247.65  5456.2  248.43  5574.4  252.64  5718.8  256.39    5725  257.08
  5735.7  256.77  5743.1  257.59    5811  259.83  5886.5  261.12  5914.1  262.58
#Mann= 3 ,-1 , 0
  4533.2      .1       0  4997.2     .07       0  5003.2      .1       0
Bank Sta=4997.2,5003.2
XS Rating Curve= 0 ,0
Exp/Cntr=0.3,0.1

Type RM Length L Ch R = 1 ,6393    ,505,505,505
BEGIN DESCRIPTION:
UNT066 IN SUCR 6.0
END DESCRIPTION:
XS GIS Cut Line= 4
      2277219.64     13388540.42      2277226.02     13388910.83
      2277551.73     13389549.47       2278011.6     13389594.18
#Sta/Elev= 30
  4334.4  261.53  4360.8  259.44  4390.8  258.78  4460.9  255.34  4470.9  254.15
  4480.9  254.15  4590.9  248.06  4670.9     245  4785.1  242.62  4801.4  242.99
  4868.4  242.08  4979.6  242.74  4992.3  241.97  4998.8  240.47  5001.6  239.97
  5004.8  240.47  5014.7  242.01  5059.6  241.34  5082.1  242.62  5090.7  241.61
  5104.5  241.67  5179.7  244.49    5329  246.51  5357.5  247.76  5421.8  248.12
  5648.5  252.28  5653.5  251.77  5658.9  252.69    5679     253  5883.8  254.87
#Mann= 3 ,-1 , 0
  4334.4      .1       0  4998.8     .07       0  5004.8      .1       0
Bank Sta=4998.8,5004.8
XS Rating Curve= 0 ,0
Exp/Cntr=0.3,0.1

Type RM Length L Ch R = 1 ,5888    ,880,880,880
BEGIN DESCRIPTION:
UNT066 IN SUCR 5.0
END DESCRIPTION:
XS GIS Cut Line= 3
      2277037.72      13388546.9      2277037.72     13389096.85
      2277237.72     13390296.85
#Sta/Elev= 30
  4460.7  260.61  4490.7  259.95  4500.7  258.81  4560.7  256.89  4580.7  255.19
  4590.7  255.49  4730.7   247.1  4780.7   245.3  4800.7  243.94  4900.7  241.45
  5005.2  240.12  5007.9  239.62  5011.2  240.12  5104.4  241.57  5122.2  240.72
  5152.6  241.69  5264.1  241.43  5456.7  243.02  5469.4  243.71  5578.4  245.62
  5618.9  245.62  5669.6   247.7  5791.3  250.98  5834.4  251.52  5862.2  253.24
  5895.2  253.65  5923.1  255.04  6016.8  257.24  6072.6  259.89  6227.2  264.25
#Mann= 3 ,-1 , 0
  4460.7      .1       0  5005.2     .07       0  5011.2      .1       0
Bank Sta=5005.2,5011.2
XS Rating Curve= 0 ,0
Exp/Cntr=0.3,0.1

Type RM Length L Ch R = 1 ,5008    ,1401,1401,1401
BEGIN DESCRIPTION:
Mapping XS fb5c3ada
END DESCRIPTION:
XS GIS Cut Line= 4
      2276708.74     13388553.15      2276395.79     13389198.22
      2276050.92     13389926.27      2276012.89     13390243.22
#Sta/Elev= 30
  4166.8  252.65  4432.4  241.37  4528.2  238.21  4804.6  236.45  4912.1   237.4
  4948.7  236.97  5000.1  234.65  5002.8  234.15  5006.1  234.65  5008.6   236.2
    5015  236.69  5031.4  236.16  5076.9  239.14  5092.5  237.54  5114.6  237.47
  5127.9  235.54  5136.8  237.43  5213.3  241.12  5241.6  239.15  5269.9  241.62
  5292.6  240.45  5302.7  241.83  5315.4   241.3  5355.3  243.18  5730.2  250.64
  5780.6  253.04  5851.1     254    5972  258.19  6002.2  256.96  6008.6  258.42
#Mann= 3 ,-1 , 0
  4166.8      .1       0  5000.1     .07       0  5006.1      .1       0
Bank Sta=5000.1,5006.1
XS Rating Curve= 0 ,0
Exp/Cntr=0.3,0.1

Type RM Length L Ch R = 1 ,3607    ,1013,1013,1013
BEGIN DESCRIPTION:
UNT066 IN SUCR 4.0
END DESCRIPTION:
XS GIS Cut Line= 3
      2276446.85     13388201.96      2275578.33      13389064.1
      2275432.08     13389426.54
#Sta/Elev= 30
  3949.7  246.56    4094  240.76  4101.1  241.11  4108.1  240.26    4398  234.29
  4454.6   234.5  4468.8  233.54    4596  233.03  4751.6   234.1  4808.1  233.29
  4843.5  231.82  4854.6  227.89  4857.4  227.39  4860.6  227.89  4885.9  230.09
  4900.1  230.56  4928.4  229.69  4963.7  231.91  4999.1  228.81  5006.1  230.02
  5027.4  230.97  5034.4  234.03  5041.5  233.15  5055.6  234.48  5069.8  234.23
  5083.9  236.07  5297.9  236.69  5499.9  241.15  5512.6  240.79  5564.3   242.6
#Mann= 3 ,-1 , 0
  3949.7      .1       0  4854.6     .07       0  4860.6      .1       0
Bank Sta=4854.6,4860.6
XS Rating Curve= 0 ,0
Exp/Cntr=0.3,0.1

Type RM Length L Ch R = 1 ,2594    ,967,967,967
BEGIN DESCRIPTION:
UNT066 IN SUCR 3.0
END DESCRIPTION:
XS GIS Cut Line= 3
      2276204.16      13387850.7      2275265.39     13388336.05
      2275169.74     13389133.13
#Sta/Elev= 30
  4144.1  246.03  4146.2  245.42  4308.9  238.96  4421.5  236.17    4434  234.89
  4511.4  233.58  4590.4     231  4710.7  229.72  4777.1  230.22  4782.7   230.9
  4821.4  230.56    4827  231.15  4954.3  231.03  4961.9   230.7  4970.8  228.33
  4976.4   229.4  4995.5  223.23  4998.3  222.73  5001.5  223.23  5006.9  224.37
  5015.1  228.03  5020.7  228.93  5051.9  228.19  5131.4  230.88  5322.6  230.32
  5559.2  232.12  5728.7  231.72  5846.3  232.87  5876.5  232.48  6003.7  234.63
#Mann= 3 ,-1 , 0
  4144.1      .1       0  4995.5     .07       0  5001.5      .1       0
Bank Sta=4995.5,5001.5
XS Rating Curve= 0 ,0
Exp/Cntr=0.3,0.1

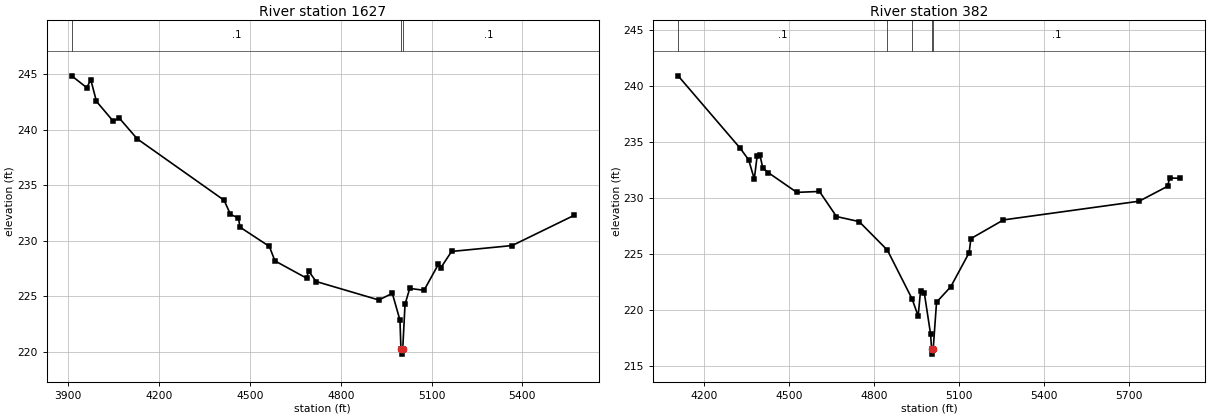
Type RM Length L Ch R = 1 ,1627    ,1245,1245,1245
BEGIN DESCRIPTION:
UNT066 IN SUCR 2.0
END DESCRIPTION:
XS GIS Cut Line= 3
      2276038.19      13387416.4      2274882.21     13387780.43
      2274524.56     13388048.67
#Sta/Elev= 30
  3910.9  244.84  3960.5  243.78  3974.3  244.47  3992.8  242.54  4047.7  240.77
  4068.6  241.02  4127.6  239.16  4414.6  233.63  4435.6  232.35  4461.8  232.04
    4467  231.21  4564.1  229.47  4582.4  228.17  4687.2  226.61  4693.6  227.25
  4718.7  226.31  4925.5  224.65  4970.3  225.24  4995.5  222.83  4998.7  220.27
  5001.5  219.77  5004.7  220.27  5012.2  224.26  5027.8  225.69  5075.1  225.52
  5122.6  227.87    5130  227.53    5166  229.02    5366  229.55  5569.9  232.26
#Mann= 3 ,-1 , 0
  3910.9      .1       0  4998.7     .07       0  5004.7      .1       0
Bank Sta=4998.7,5004.7
XS Rating Curve= 0 ,0
Exp/Cntr=0.3,0.1

Type RM Length L Ch R = 1 ,382     ,0,0,0
BEGIN DESCRIPTION:
UNT066 IN SUCR 1.0
END DESCRIPTION:
XS GIS Cut Line= 3
      2275846.58     13387103.47      2275124.89     13387077.93
      2274505.43     13387927.29
#Sta/Elev= 30
  4108.3  240.88  4327.3  234.42  4357.3  233.38  4377.3  231.66  4387.3  233.71
  4397.3   233.8  4407.3  232.65  4427.4  232.22  4527.4  230.47  4607.5  230.55
  4667.5  228.31  4747.6  227.86  4847.3  225.31  4934.2  220.97    4956  219.43
  4964.5   221.7  4977.6   221.5    5000  217.78  5003.2  216.52    5006  216.02
  5009.2  216.52  5020.9  220.66  5071.1  222.04    5136  225.08  5142.2  226.34
  5257.3  228.01  5736.2  229.68  5836.6  231.01    5844  231.75  5881.7  231.73
#Mann= 5 ,-1 , 0
  4108.3      .1       0  4847.3     .12       0  4934.2      .1       0
  5003.2     .07       0  5009.2      .1       0
Bank Sta=5003.2,5009.2
XS Rating Curve= 0 ,0
Exp/Cntr=0.3,0.1

Chan Stop Cuts=-1
Use User Specified Reach Order=0
Composite Channel Slope=5