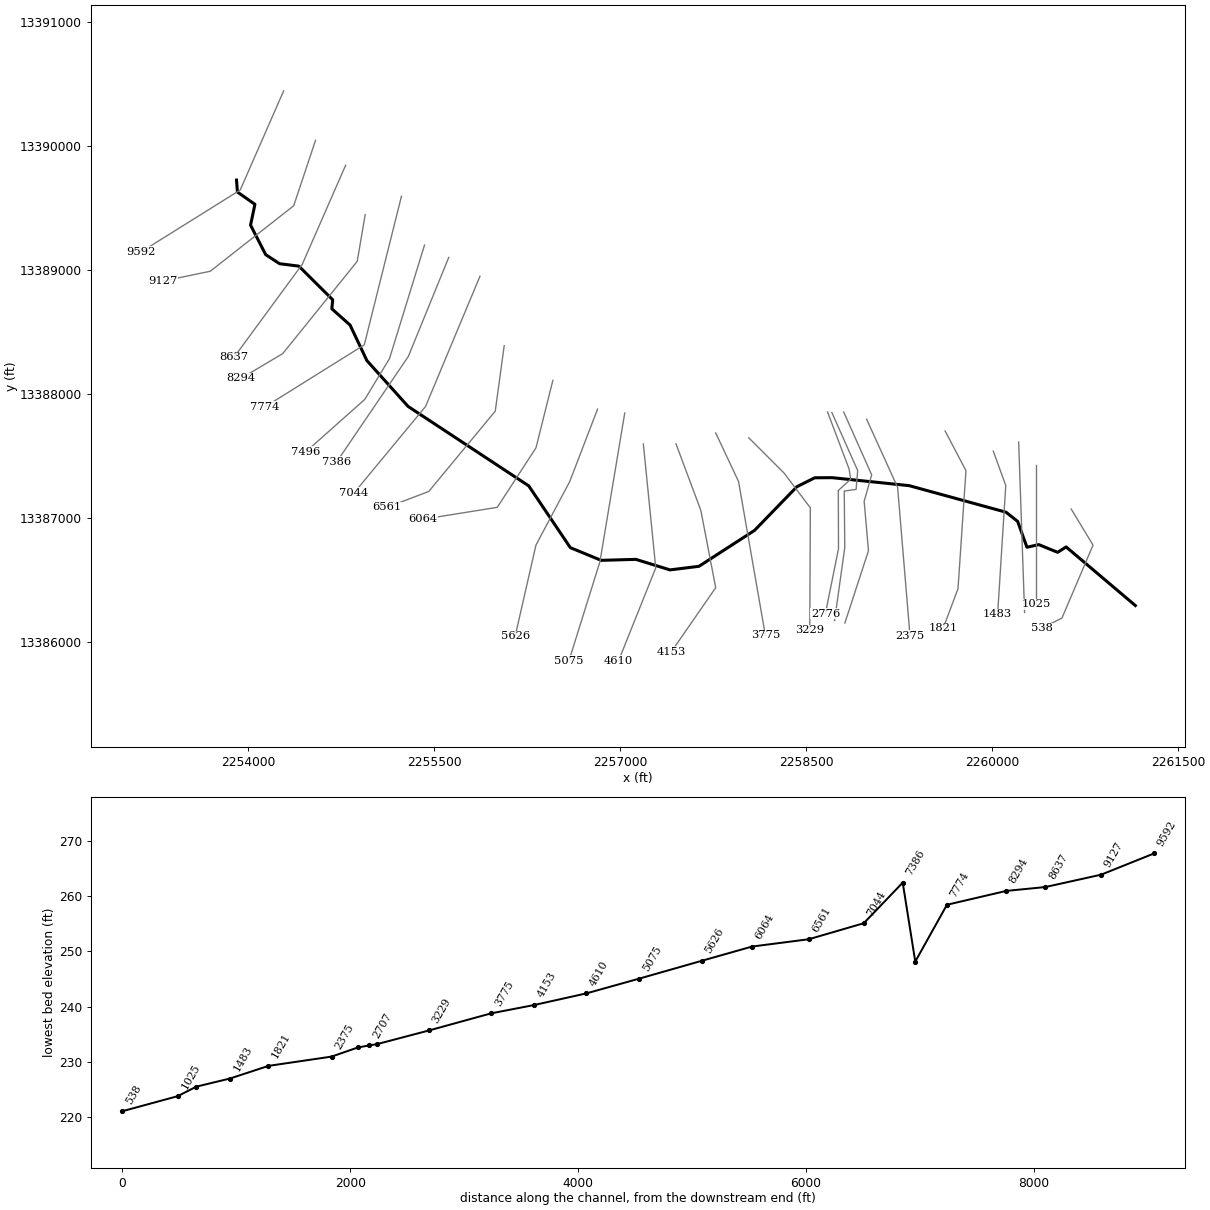
--- UNT068 IN SUCR.prj (project) ---

Proj Title=UNT068 IN SUCR Base Level Engineering
Current Plan=p01
Default Exp/Contr=0.3,0.1
English Units
Geom File=g01
Flow File=f01
Plan File=p01
BEGIN DESCRIPTION:
UNT068 IN SUCR
END DESCRIPTION:

--- UNT068 IN SUCR.p01 (plan) ---

Plan Title=Multiple Run
Short Identifier=Multiple
Geom File=g01
Flow File=f01
Subcritical Flow
K Sum by GR= 0
Std Step Tol= 0.01
Critical Tol= 0.01
Num of Std Step Trials= 20
Max Error Tol= 0.3
Flow Tol Ratio= 0.001
Split Flow NTrial= 30
Split Flow Tol= 0.02
Split Flow Ratio= 0.02
Log Output Level= 0
Friction Slope Method= 1
Unsteady Friction Slope Method= 2
Unsteady Bridges Friction Slope Method= 1
Parabolic Critical Depth
Global Vel Dist=  1 , 1 , 1
Global Log Level= 0
CheckData=True
Encroach Param= -1, 0, 0, 0
BEGIN DESCRIPTION:
Multiple Run
END DESCRIPTION:

--- UNT068 IN SUCR.f01 (steady flow) ---

Flow Title=Multiple
Number of Profiles=7
Profile Names=10-year,25-year,50-year,1pct_min,100-year,1pct_plu,500-year
River Rch & RM= UNT068 IN SUCR,Reach-1,9592
     236     325     398     359     485     656     733
River Rch & RM= UNT068 IN SUCR,Reach-1,5075
     329     461     572     521     705     953    1087
River Rch & RM= UNT068 IN SUCR,Reach-1,1025
     385     544     677     620     839    1134    1305
Boundary for River Rch & Prof#=UNT068 IN SUCR,Reach-1,1
Up Type=0
Dn Type=3
Dn Slope=0.005
Boundary for River Rch & Prof#=UNT068 IN SUCR,Reach-1,2
Up Type=0
Dn Type=3
Dn Slope=0.005
Boundary for River Rch & Prof#=UNT068 IN SUCR,Reach-1,3
Up Type=0
Dn Type=3
Dn Slope=0.005
Boundary for River Rch & Prof#=UNT068 IN SUCR,Reach-1,4
Up Type=0
Dn Type=3
Dn Slope=0.005
Boundary for River Rch & Prof#=UNT068 IN SUCR,Reach-1,5
Up Type=0
Dn Type=3
Dn Slope=0.005
Boundary for River Rch & Prof#=UNT068 IN SUCR,Reach-1,6
Up Type=0
Dn Type=3
Dn Slope=0.005
Boundary for River Rch & Prof#=UNT068 IN SUCR,Reach-1,7
Up Type=0
Dn Type=3
Dn Slope=0.005

--- UNT068 IN SUCR.g01 (geometry) ---

Geom Title=Existing Conditions

River Reach=UNT068 IN SUCR,Reach-1
Reach XY= 30
      2253907.72     13389726.85      2253914.96     13389630.32
      2254056.16     13389531.19      2254020.91     13389363.24
      2254142.97     13389125.13      2254254.74     13389051.92
      2254410.47     13389032.33      2254683.19     13388760.76
      2254676.31     13388687.98      2254823.45     13388556.47
      2254958.87     13388270.01      2255290.90     13387900.22
      2256263.64     13387258.99      2256599.15     13386760.27
      2256847.71     13386657.96      2257127.16     13386665.88
      2257402.68     13386580.83      2257636.45     13386609.94
      2258084.47     13386899.94      2258425.15     13387251.79
      2258568.92     13387324.16      2258708.67     13387325.20
      2259330.31     13387260.88      2260111.56     13387046.47
      2260205.31     13386972.68      2260280.23     13386763.64
      2260375.54     13386784.99      2260527.85     13386722.71
      2260596.37     13386766.24      2261154.62     13386292.98

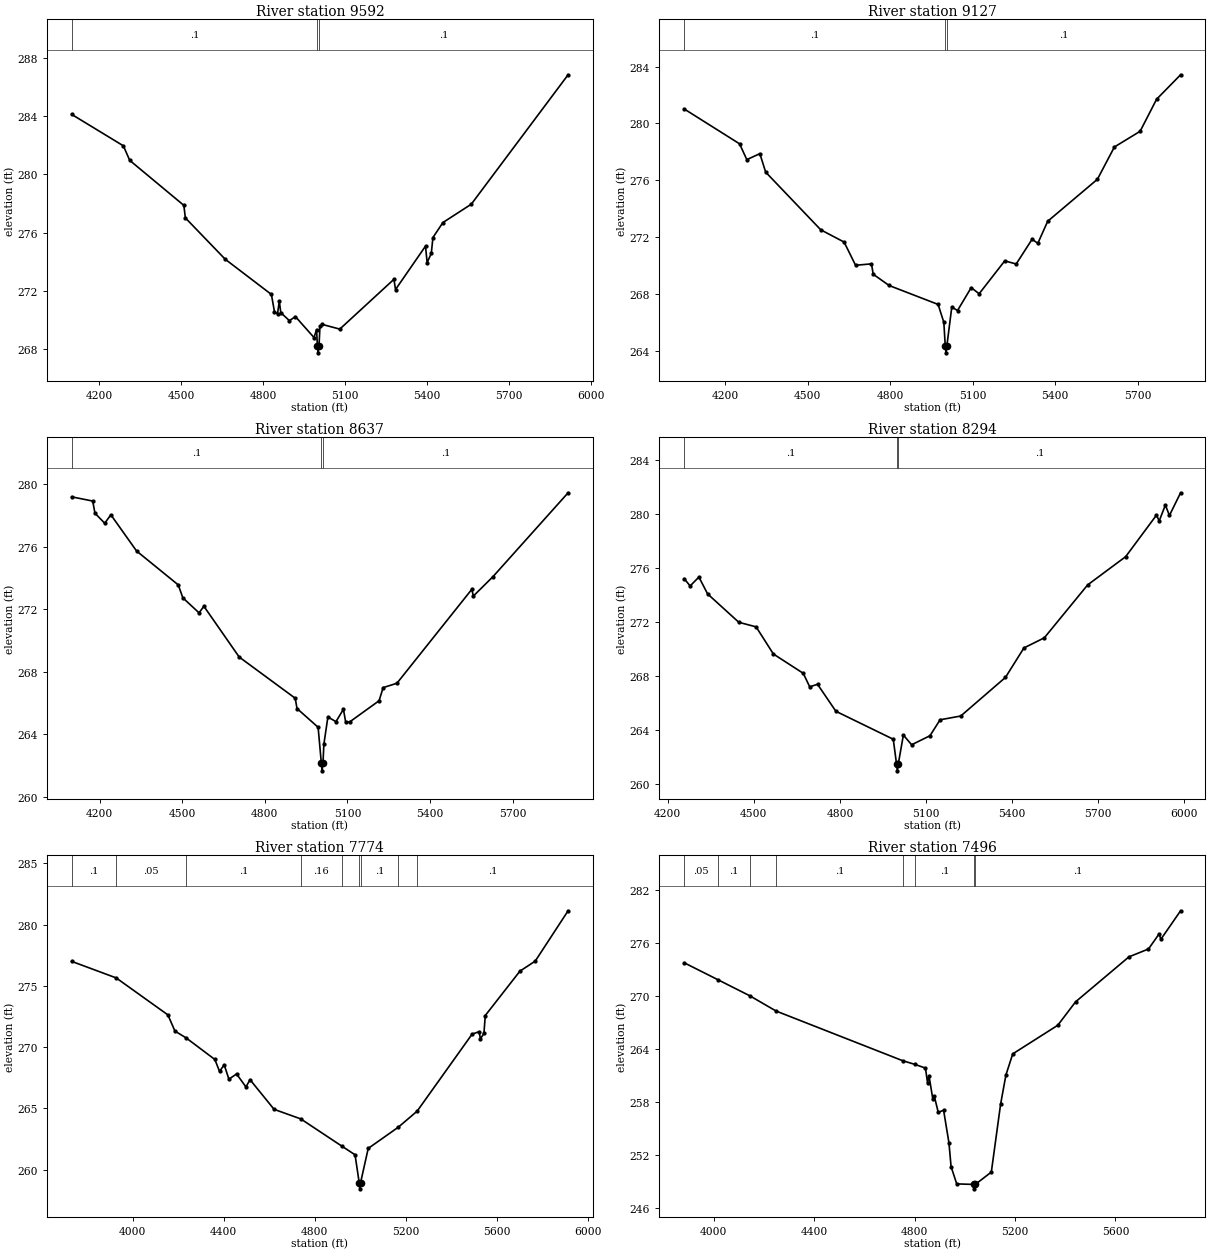
Type RM Length L Ch R = 1,9592,465,465,465
BEGIN DESCRIPTION:
UNT068 IN SUCR 18.0
END DESCRIPTION:
XS GIS Cut Line= 3
      2254287.73     13390446.87      2253937.72     13389646.85
      2253137.75     13389146.87
#Sta/Elev= 30
  4098.8  284.12  4287.9  281.96  4311.3  280.96  4509.3  277.87  4514.8  277.01
  4660.6  274.17  4829.7  271.75  4841.0  270.55  4852.0  270.42  4858.6  271.29
  4864.0  270.50  4895.6  269.95  4917.5  270.23  4985.6  268.79  4995.0  269.34
  4997.9  268.24  5000.7  267.74  5003.9  268.24  5007.4  269.56  5016.3  269.69
  5079.9  269.37  5278.0  272.79  5283.9  272.09  5393.6  275.07  5399.5  273.94
  5414.8  274.57  5420.7  275.66  5457.3  276.69  5561.1  277.95  5915.4  286.84
#Mann=3,-1,0
  4098.8     0.1       0  4997.9    0.07       0  5003.9     0.1       0
Bank Sta=4997.9,5003.9
Exp/Cntr=0.3,0.1

Type RM Length L Ch R = 1,9127,490,490,490
BEGIN DESCRIPTION:
UNT068 IN SUCR 17.0
END DESCRIPTION:
XS GIS Cut Line= 4
      2254544.76     13390047.86      2254368.63     13389519.47
      2253696.13     13388991.07      2253312.29     13388911.11
#Sta/Elev= 30
  4051.4  281.02  4252.8  278.57  4279.1  277.46  4326.5  277.88  4347.7  276.58
  4547.9  272.53  4632.7  271.67  4674.4  270.04  4732.2  270.14  4738.5  269.41
  4796.3  268.62  4974.4  267.29  4995.2  266.03  5000.3  264.39  5003.0  263.89
  5006.3  264.39  5024.1  267.11  5044.9  266.86  5094.6  268.47  5123.5  268.04
  5216.6  270.35  5258.2  270.13  5316.0  271.87  5336.8  271.58  5372.6  273.13
  5553.3  276.08  5615.2  278.35  5708.6  279.45  5768.4  281.70  5855.7  283.42
#Mann=3,-1,0
  4051.4     0.1       0  5000.3    0.07       0  5006.3     0.1       0
Bank Sta=5000.3,5006.3
Exp/Cntr=0.3,0.1

Type RM Length L Ch R = 1,8637,343,343,343
BEGIN DESCRIPTION:
UNT068 IN SUCR 16.0
END DESCRIPTION:
XS GIS Cut Line= 3
      2254787.72     13389846.86      2254437.72     13389046.85
      2253887.70     13388296.83
#Sta/Elev= 30
  4098.5  279.20  4174.9  278.93  4183.1  278.15  4218.6  277.51  4240.8  278.05
  4334.3  275.73  4485.6  273.56  4502.4  272.73  4561.2  271.77  4578.8  272.19
  4707.0  268.94  4910.5  266.30  4917.1  265.64  4993.7  264.44  5005.4  262.15
  5008.1  261.65  5011.4  262.15  5014.6  263.35  5029.2  265.10  5058.5  264.80
  5085.6  265.59  5094.0  264.76  5108.1  264.78  5215.2  266.14  5229.9  266.98
  5280.0  267.26  5551.7  273.27  5557.9  272.85  5629.0  274.09  5901.8  279.46
#Mann=3,-1,0
  4098.5     0.1       0  5005.4    0.07       0  5011.4     0.1       0
Bank Sta=5005.4,5011.4
Exp/Cntr=0.3,0.1

Type RM Length L Ch R = 1,8294,520,520,520
BEGIN DESCRIPTION:
UNT068 IN SUCR 15.0
END DESCRIPTION:
XS GIS Cut Line= 4
      2254945.05     13389447.38      2254881.01     13389071.13
      2254280.56     13388326.58      2253944.29     13388126.42
#Sta/Elev= 30
  4257.2  275.18  4278.0  274.64  4308.5  275.30  4338.9  274.05  4447.6  271.95
  4507.9  271.61  4568.1  269.60  4672.2  268.17  4694.6  267.17  4721.8  267.36
  4785.8  265.36  4985.7  263.29  4997.1  261.45  4999.8  260.95  5003.1  261.45
  5020.9  263.60  5049.7  262.88  5113.6  263.55  5148.8  264.73  5220.8  265.01
  5376.6  267.87  5440.9  270.05  5511.9  270.80  5663.0  274.72  5795.4  276.81
  5902.5  279.88  5912.2  279.46  5933.7  280.63  5947.8  279.86  5986.7  281.54
#Mann=3,-1,0
  4257.2     0.1       0  4997.1    0.07       0  5003.1     0.1       0
Bank Sta=4997.1,5003.1
Exp/Cntr=0.3,0.1

Type RM Length L Ch R = 1,7774,278,278,278
BEGIN DESCRIPTION:
UNT068 IN SUCR 14.0
END DESCRIPTION:
XS GIS Cut Line= 3
      2255237.72     13389596.84      2254937.72     13388396.85
      2254137.74     13387896.86
#Sta/Elev= 30
  3732.5  277.01  3927.9  275.66  4155.1  272.64  4186.0  271.32  4235.3  270.76
  4361.3  269.00  4381.9  268.03  4402.5  268.56  4423.1  267.39  4456.6  267.82
  4497.8  266.76  4515.9  267.35  4621.5  264.93  4738.6  264.15  4917.9  261.94
  4977.1  261.22  4995.3  258.94  4998.1  258.44  5001.3  258.94  5034.9  261.74
  5166.9  263.47  5249.7  264.78  5491.2  271.07  5521.9  271.27  5527.8  270.68
  5543.1  271.13  5549.0  272.59  5701.1  276.21  5768.4  277.03  5912.8  281.14
#Mann=9,-1,0
  3732.5     0.1       0  3927.9    0.05       0  4235.3     0.1       0
  4738.6    0.16       0  4917.9     0.1       0  4995.3    0.07       0
  5001.3     0.1       0  5166.9    0.16       0  5249.7     0.1       0
Bank Sta=4995.3,5001.3
Exp/Cntr=0.3,0.1

Type RM Length L Ch R = 1,7496,110,110,110
BEGIN DESCRIPTION:
Mapping XS 63fc8df0
END DESCRIPTION:
XS GIS Cut Line= 4
      2255423.39     13389202.31      2255141.27     13388286.48
      2254941.61     13387956.62      2254468.50     13387535.59
#Sta/Elev= 30
  3882.3  273.77  4016.7  271.85  4144.3  270.02  4248.5  268.30  4753.1  262.67
  4801.1  262.26  4843.3  261.84  4851.6  260.18  4857.4  260.97  4872.9  258.29
  4878.7  258.64  4894.2  256.83  4915.6  257.06  4936.9  253.37  4945.4  250.67
  4967.9  248.72  5035.9  248.66  5038.6  248.16  5041.9  248.66  5105.7  250.06
  5142.5  257.73  5163.9  261.07  5191.0  263.45  5370.3  266.69  5441.4  269.35
  5653.8  274.44  5731.6  275.33  5774.2  277.05  5780.9  276.43  5859.5  279.66
#Mann=8,-1,0
  3882.3    0.05       0  4016.7     0.1       0  4144.3    0.05       0
  4248.5     0.1       0  4753.1    0.16       0  4801.1     0.1       0
  5035.9    0.07       0  5041.9     0.1       0
Bank Sta=5035.9,5041.9
Exp/Cntr=0.3,0.1

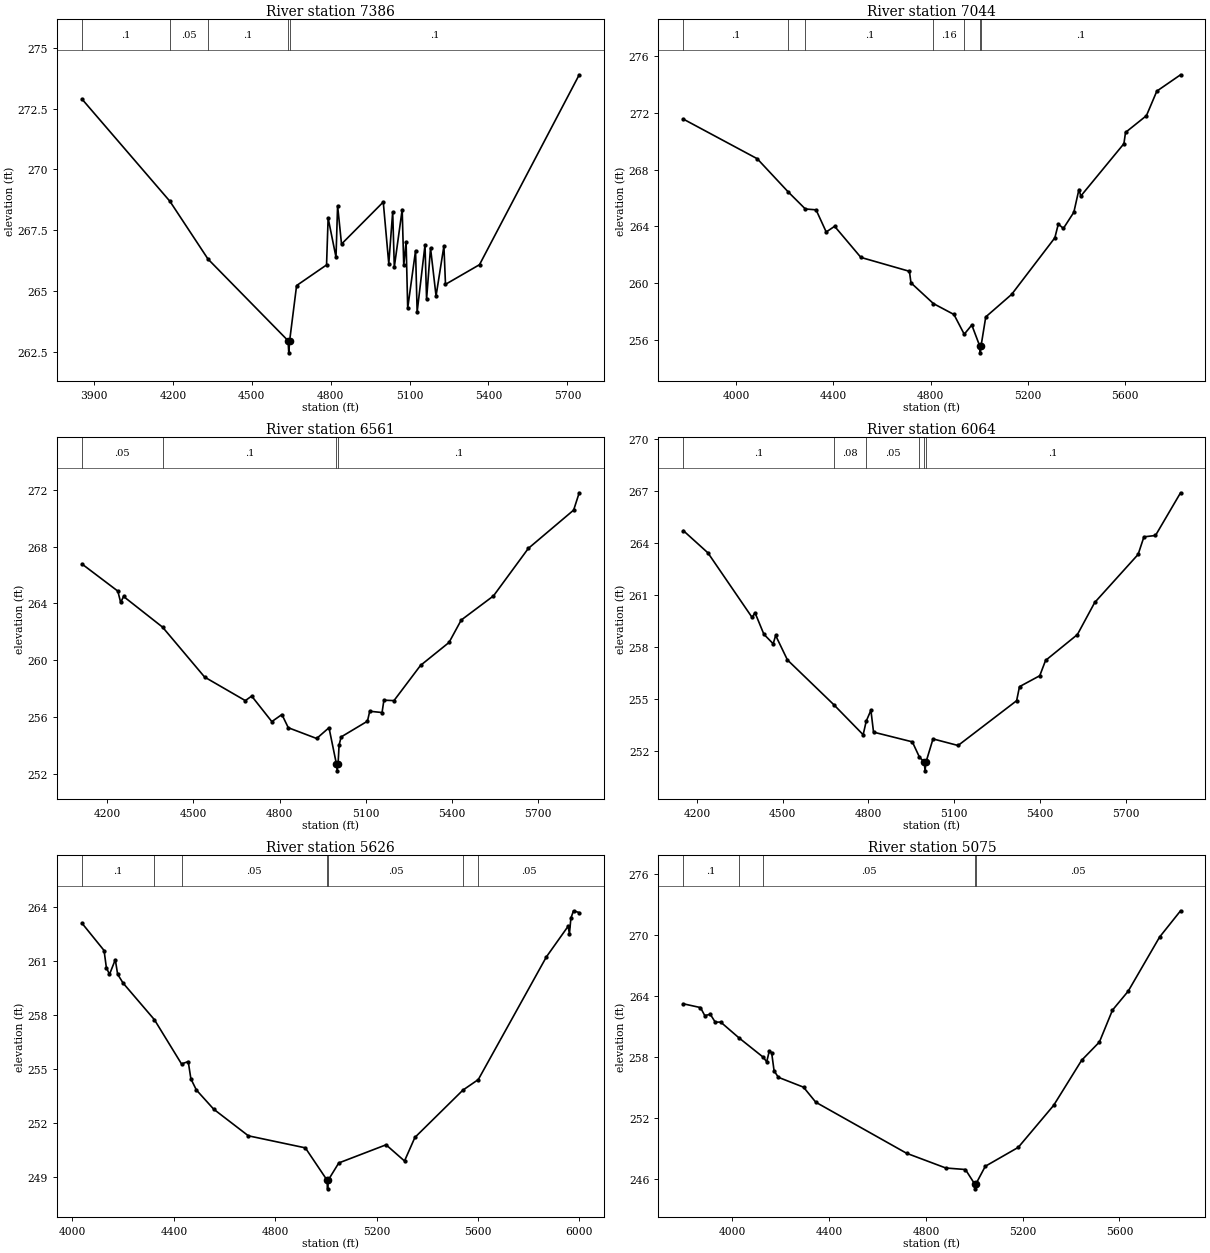
Type RM Length L Ch R = 1,7386,342,342,342
BEGIN DESCRIPTION:
UNT068 IN SUCR 13.0
END DESCRIPTION:
XS GIS Cut Line= 3
      2255618.71     13389102.48      2255293.18     13388303.84
      2254715.92     13387453.14
#Sta/Elev= 30
  3854.4  272.90  4188.8  268.69  4333.7  266.31  4638.0  262.95  4640.7  262.45
  4644.0  262.95  4670.4  265.22  4784.3  266.07  4790.3  268.00  4820.2  266.39
  4826.3  268.51  4841.2  266.93  4999.9  268.66  5020.9  266.12  5035.8  268.26
  5041.9  265.98  5071.8  268.35  5077.8  266.05  5086.7  267.02  5092.8  264.29
  5122.7  266.66  5128.7  264.13  5158.6  266.89  5164.6  264.66  5179.6  266.77
  5200.6  264.79  5230.5  266.85  5236.5  265.27  5365.8  266.08  5744.9  273.90
#Mann=5,-1,0
  3854.4     0.1       0  4188.8    0.05       0  4333.7     0.1       0
  4638.0    0.07       0  4644.0     0.1       0
Bank Sta=4638,4644
Exp/Cntr=0.3,0.1

Type RM Length L Ch R = 1,7044,483,483,483
BEGIN DESCRIPTION:
UNT068 IN SUCR 12.0
END DESCRIPTION:
XS GIS Cut Line= 3
      2255870.43     13388950.53      2255432.07     13387900.20
      2254855.01     13387201.66
#Sta/Elev= 30
  3782.8  271.56  4086.6  268.77  4214.1  266.43  4284.5  265.23  4328.6  265.17
  4370.3  263.61  4404.9  264.01  4512.8  261.82  4712.4  260.84  4718.7  260.03
  4810.9  258.57  4895.4  257.80  4937.7  256.41  4968.8  257.06  5001.0  255.60
  5003.7  255.10  5007.0  255.60  5026.2  257.63  5132.8  259.22  5310.2  263.20
  5324.5  264.17  5345.3  263.86  5388.3  265.00  5409.2  266.60  5417.0  266.14
  5594.2  269.83  5600.7  270.62  5686.7  271.80  5729.5  273.53  5827.0  274.68
#Mann=7,-1,0
  3782.8     0.1       0  4214.1    0.05       0  4284.5     0.1       0
  4810.9    0.16       0  4937.7     0.1       0  5001.0    0.07       0
  5007.0     0.1       0
Bank Sta=5001,5007
Exp/Cntr=0.3,0.1

Type RM Length L Ch R = 1,6561,497,497,497
BEGIN DESCRIPTION:
UNT068 IN SUCR 11.0
END DESCRIPTION:
XS GIS Cut Line= 4
      2256065.90     13388390.66      2255993.84     13387862.24
      2255457.44     13387213.75      2255121.95     13387085.95
#Sta/Elev= 30
  4111.1  266.78  4236.1  264.87  4246.1  264.07  4256.2  264.49  4392.1  262.33
  4538.8  258.81  4680.7  257.15  4702.9  257.47  4773.2  255.67  4808.3  256.17
  4830.5  255.24  4929.5  254.48  4972.5  255.24  4998.2  252.70  5000.9  252.20
  5004.2  252.70  5007.7  254.02  5014.8  254.59  5106.6  255.70  5114.5  256.40
  5157.5  256.31  5164.0  257.18  5199.1  257.15  5291.6  259.63  5391.1  261.25
  5433.6  262.83  5546.0  264.53  5667.6  267.88  5825.6  270.58  5845.0  271.80
#Mann=4,-1,0
  4111.1    0.05       0  4392.1     0.1       0  4998.2    0.07       0
  5004.2     0.1       0
Bank Sta=4998.2,5004.2
Exp/Cntr=0.3,0.1

Type RM Length L Ch R = 1,6064,438,438,438
BEGIN DESCRIPTION:
UNT068 IN SUCR 10.0
END DESCRIPTION:
XS GIS Cut Line= 4
      2256458.18     13388110.39      2256322.08     13387566.02
      2256009.85     13387085.66      2255411.11     13386989.86
#Sta/Elev= 30
  4152.0  264.72  4238.1  263.44  4392.7  259.72  4403.0  259.99  4434.0  258.75
  4466.6  258.20  4475.2  258.68  4516.4  257.27  4678.2  254.70  4781.5  252.96
  4792.2  253.74  4808.6  254.37  4817.8  253.11  4953.6  252.55  4978.5  251.67
  4995.4  251.38  4998.1  250.88  5001.4  251.38  5026.0  252.72  5113.7  252.34
  5318.6  254.92  5328.7  255.73  5399.6  256.36  5419.9  257.24  5531.3  258.73
  5592.0  260.58  5743.9  263.35  5764.2  264.36  5804.7  264.44  5892.4  266.90
#Mann=6,-1,0
  4152.0     0.1       0  4678.2    0.08       0  4792.2    0.05       0
  4978.5     0.1       0  4995.4    0.07       0  5001.4     0.1       0
Bank Sta=4995.4,5001.4
Exp/Cntr=0.3,0.1

Type RM Length L Ch R = 1,5626,551,551,551
BEGIN DESCRIPTION:
UNT068 IN SUCR 9.0
END DESCRIPTION:
XS GIS Cut Line= 4
      2256818.45     13387878.25      2256594.28     13387293.81
      2256322.08     13386781.43      2256153.97     13386044.92
#Sta/Elev= 30
  4037.4  263.10  4124.6  261.58  4133.6  260.63  4146.0  260.25  4168.9  261.07
  4178.1  260.26  4199.5  259.77  4323.2  257.73  4430.1  255.27  4456.6  255.40
  4467.1  254.44  4488.7  253.82  4557.2  252.75  4693.9  251.27  4918.6  250.60
  5003.5  248.82  5006.3  248.32  5009.5  248.82  5050.5  249.76  5237.0  250.77
  5309.8  249.87  5350.8  251.18  5540.0  253.81  5600.9  254.40  5869.3  261.22
  5955.3  262.93  5960.4  262.51  5966.2  263.38  5976.5  263.79  5999.0  263.69
#Mann=7,-1,0
  4037.4     0.1       0  4323.2    0.08       0  4430.1    0.05       0
  5003.5    0.03       0  5009.5    0.05       0  5540.0     0.1       0
  5600.9    0.05       0
Bank Sta=5003.5,5009.5
Exp/Cntr=0.3,0.1

Type RM Length L Ch R = 1,5075,465,465,465
BEGIN DESCRIPTION:
UNT068 IN SUCR 8.0
END DESCRIPTION:
XS GIS Cut Line= 3
      2257037.71     13387846.81      2256837.72     13386646.85
      2256587.71     13385846.82
#Sta/Elev= 30
  3797.6  263.28  3868.5  262.91  3886.3  262.12  3909.1  262.25  3929.4  261.48
  3952.2  261.48  4027.6  259.93  4128.2  258.02  4142.2  257.57  4152.4  258.59
  4162.5  258.49  4172.7  256.69  4190.4  256.05  4294.3  255.08  4345.0  253.60
  4720.1  248.58  4882.3  247.13  4963.4  246.98  5001.0  245.58  5003.7  245.08
  5007.0  245.58  5045.5  247.30  5181.7  249.16  5327.9  253.29  5443.7  257.73
  5517.0  259.52  5571.0  262.66  5635.9  264.52  5765.8  269.85  5852.3  272.43
#Mann=5,-1,0
  3797.6     0.1       0  4027.6    0.08       0  4128.2    0.05       0
  5001.0    0.03       0  5007.0    0.05       0
Bank Sta=5001,5007
Exp/Cntr=0.3,0.1

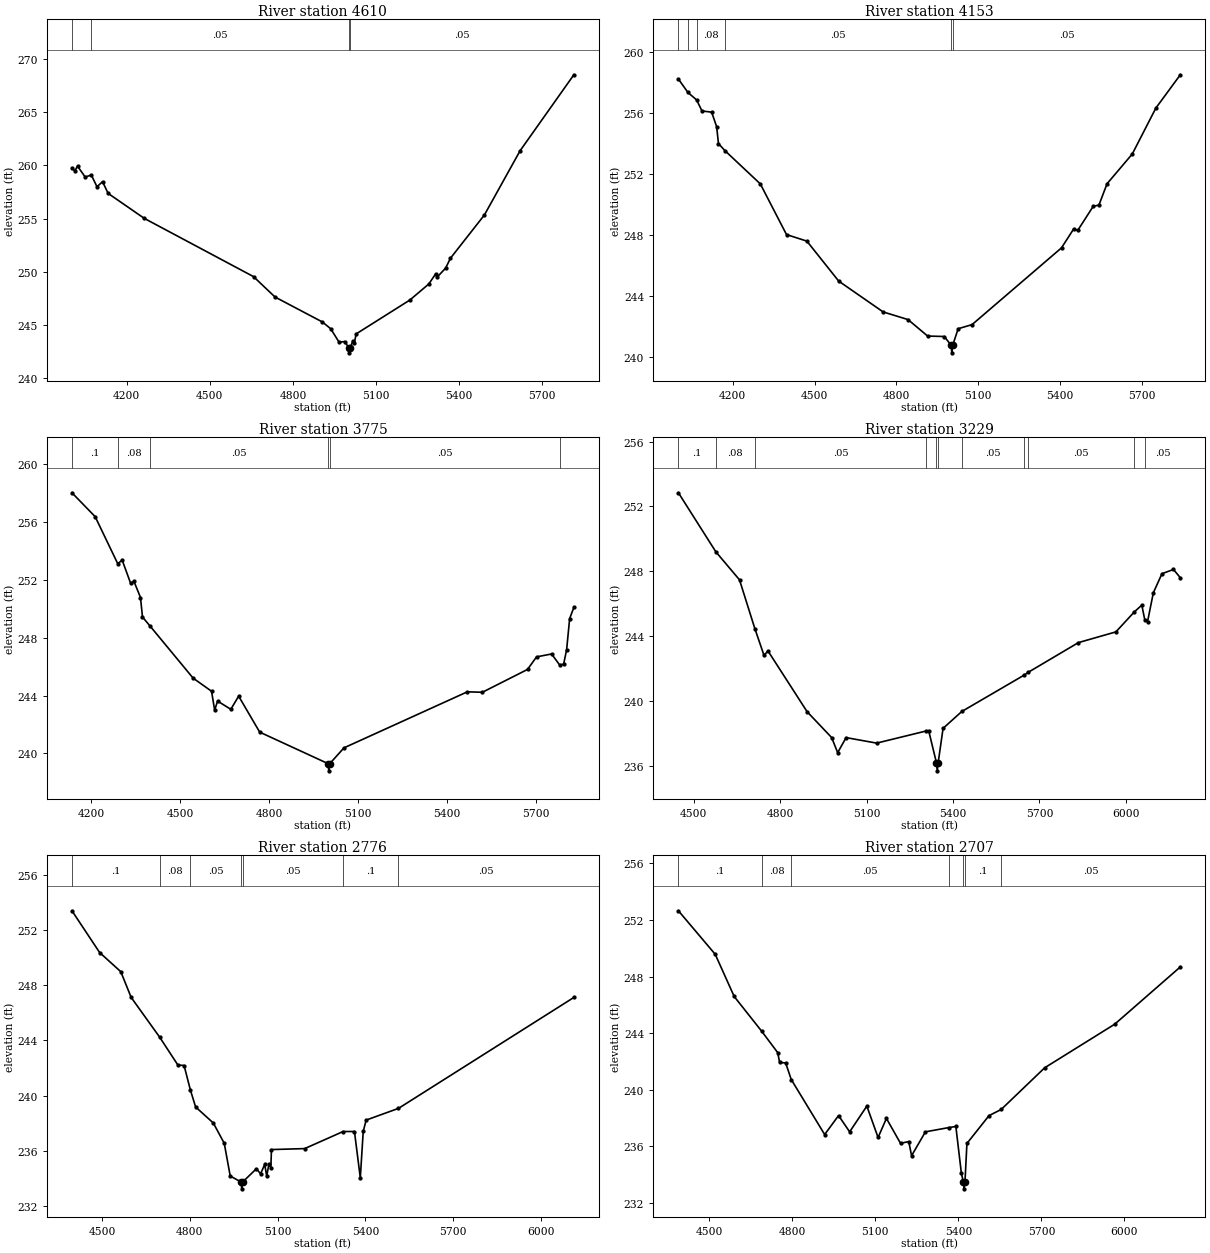
Type RM Length L Ch R = 1,4610,457,457,457
BEGIN DESCRIPTION:
UNT068 IN SUCR 7.0
END DESCRIPTION:
XS GIS Cut Line= 3
      2257187.72     13387596.83      2257287.72     13386596.85
      2256987.73     13385846.89
#Sta/Elev= 30
  4001.9  259.78  4011.9  259.48  4022.0  259.94  4049.6  258.92  4072.0  259.10
  4092.3  258.00  4112.4  258.48  4132.5  257.38  4263.2  255.03  4657.6  249.56
  4735.5  247.64  4906.4  245.30  4936.5  244.66  4966.7  243.40  4986.8  243.46
  5001.3  242.90  5004.1  242.40  5007.3  242.90  5016.3  243.51  5021.7  243.32
  5028.4  244.18  5222.3  247.36  5290.9  248.87  5315.2  249.81  5320.5  249.50
  5351.5  250.36  5369.0  251.29  5491.5  255.35  5620.8  261.40  5814.6  268.52
#Mann=4,-1,0
  4001.9    0.08       0  4072.0    0.05       0  5001.3    0.03       0
  5007.3    0.05       0
Bank Sta=5001.3,5007.3
Exp/Cntr=0.3,0.1

Type RM Length L Ch R = 1,4153,378,378,378
BEGIN DESCRIPTION:
UNT068 IN SUCR 6.0
END DESCRIPTION:
XS GIS Cut Line= 4
      2257450.91     13387598.07      2257651.07     13387061.64
      2257771.16     13386437.18      2257411.80     13385918.10
#Sta/Elev= 30
  4000.7  258.24  4035.6  257.36  4067.6  256.87  4086.9  256.15  4122.5  256.07
  4140.8  255.12  4147.5  254.01  4171.7  253.54  4300.9  251.37  4396.9  248.05
  4471.6  247.62  4588.3  245.00  4751.2  242.98  4842.3  242.48  4914.2  241.40
  4975.3  241.37  5000.2  240.80  5002.9  240.30  5006.2  240.80  5026.2  241.88
  5077.1  242.15  5405.0  247.18  5449.6  248.42  5464.4  248.32  5521.2  249.90
  5542.1  249.98  5571.9  251.38  5664.4  253.33  5750.9  256.34  5840.5  258.52
#Mann=6,-1,0
  4000.7    0.08       0  4035.6     0.1       0  4067.6    0.08       0
  4171.7    0.05       0  5000.2    0.03       0  5006.2    0.05       0
Bank Sta=5000.2,5006.2
Exp/Cntr=0.3,0.1

Type RM Length L Ch R = 1,3775,546,546,546
BEGIN DESCRIPTION:
UNT068 IN SUCR 5.0
END DESCRIPTION:
XS GIS Cut Line= 3
      2257771.15     13387686.13      2257955.30     13387293.81
      2258171.46     13386052.89
#Sta/Elev= 30
  4135.0  258.04  4213.2  256.39  4289.5  253.13  4304.4  253.38  4333.0  251.77
  4344.1  251.91  4366.2  250.79  4372.9  249.44  4397.0  248.85  4543.6  245.21
  4605.9  244.30  4616.4  242.99  4626.2  243.62  4670.9  243.05  4697.3  243.96
  4768.3  241.47  4998.8  239.29  5001.5  238.79  5004.8  239.29  5052.5  240.38
  5468.7  244.26  5519.5  244.23  5671.7  245.81  5702.2  246.68  5752.9  246.88
  5780.1  246.12  5793.5  246.17  5803.7  247.19  5813.8  249.33  5828.0  250.10
#Mann=6,-1,0
  4135.0     0.1       0  4289.5    0.08       0  4397.0    0.05       0
  4998.8    0.03       0  5004.8    0.05       0  5780.1     0.1       0
Bank Sta=4998.8,5004.8
Exp/Cntr=0.3,0.1

Type RM Length L Ch R = 1,3229,453,453,453
BEGIN DESCRIPTION:
UNT068 IN SUCR 4.0
END DESCRIPTION:
XS GIS Cut Line= 4
      2258037.73     13387646.85      2258322.63     13387361.94
      2258534.03     13387081.76      2258529.58     13386093.17
#Sta/Elev= 30
  4446.7  252.84  4576.6  249.20  4658.8  247.47  4712.1  244.46  4743.7  242.82
  4757.8  243.08  4893.4  239.34  4978.8  237.74  4999.6  236.81  5028.8  237.74
  5134.9  237.40  5307.4  238.15  5315.5  238.17  5342.5  236.19  5345.3  235.69
  5348.5  236.19  5365.5  238.31  5430.5  239.35  5646.6  241.59  5661.4  241.77
  5835.5  243.60  5965.5  244.26  6029.9  245.50  6055.5  245.91  6066.1  244.98
  6075.5  244.90  6095.5  246.67  6125.5  247.85  6165.5  248.11  6189.2  247.60
#Mann=11,-1,0
  4446.7     0.1       0  4576.6    0.08       0  4712.1    0.05       0
  5307.4     0.1       0  5342.5    0.03       0  5348.5     0.1       0
  5430.5    0.05       0  5646.6     0.1       0  5661.4    0.05       0
  6029.9     0.1       0  6066.1    0.05       0
Bank Sta=5342.5,5348.5
Exp/Cntr=0.3,0.1

Type RM Length L Ch R = 1,2776,69,69,69
BEGIN DESCRIPTION:
Mapping XS aeaa2aaf
END DESCRIPTION:
XS GIS Cut Line= 6
      2258672.80     13387855.38      2258846.42     13387395.28
      2258859.44     13387312.81      2258759.61     13387221.67
      2258761.10     13386751.71      2258655.44     13386227.72
#Sta/Elev= 30
  4397.2  253.41  4491.8  250.38  4564.1  248.99  4599.6  247.12  4697.5  244.22
  4759.0  242.22  4780.4  242.18  4801.8  240.41  4819.8  239.17  4880.2  238.01
  4917.7  236.53  4938.0  234.16  4974.8  233.73  4977.5  233.23  4980.8  233.73
  5027.5  234.69  5041.7  234.32  5055.9  235.00  5062.7  234.15  5070.0  235.01
  5076.9  234.77  5078.9  236.08  5192.5  236.15  5323.8  237.39  5362.5  237.39
  5382.5  234.03  5392.5  237.40  5402.5  238.22  5513.0  239.07  6112.2  247.12
#Mann=7,-1,0
  4397.2     0.1       0  4697.5    0.08       0  4801.8    0.05       0
  4974.8    0.03       0  4980.8    0.05       0  5323.8     0.1       0
  5513.0    0.05       0
Bank Sta=4974.8,4980.8
Exp/Cntr=0.3,0.1

Type RM Length L Ch R = 1,2707,102,102,102
BEGIN DESCRIPTION:
UNT068 IN SUCR 3.0
END DESCRIPTION:
XS GIS Cut Line= 6
      2258707.54     13387850.98      2258915.86     13387382.26
      2258902.84     13387230.35      2258807.36     13387217.33
      2258811.70     13386761.60      2258729.27     13386171.61
#Sta/Elev= 30
  4388.4  252.65  4521.5  249.57  4589.9  246.59  4689.4  244.13  4747.2  242.62
  4754.0  241.93  4775.9  241.89  4796.0  240.72  4916.8  236.83  4967.0  238.17
  5007.1  237.02  5069.2  238.84  5109.8  236.62  5139.9  237.97  5190.8  236.21
  5220.8  236.33  5230.8  235.33  5280.8  237.02  5364.9  237.32  5390.8  237.40
  5410.8  234.08  5417.8  233.49  5420.6  232.99  5423.8  233.49  5430.8  236.20
  5510.8  238.17  5554.5  238.60  5711.8  241.55  5964.7  244.63  6201.8  248.68
#Mann=7,-1,0
  4388.4     0.1       0  4689.4    0.08       0  4796.0    0.05       0
  5364.9     0.1       0  5417.8    0.03       0  5423.8     0.1       0
  5554.5    0.05       0
Bank Sta=5417.8,5423.8
Exp/Cntr=0.3,0.1

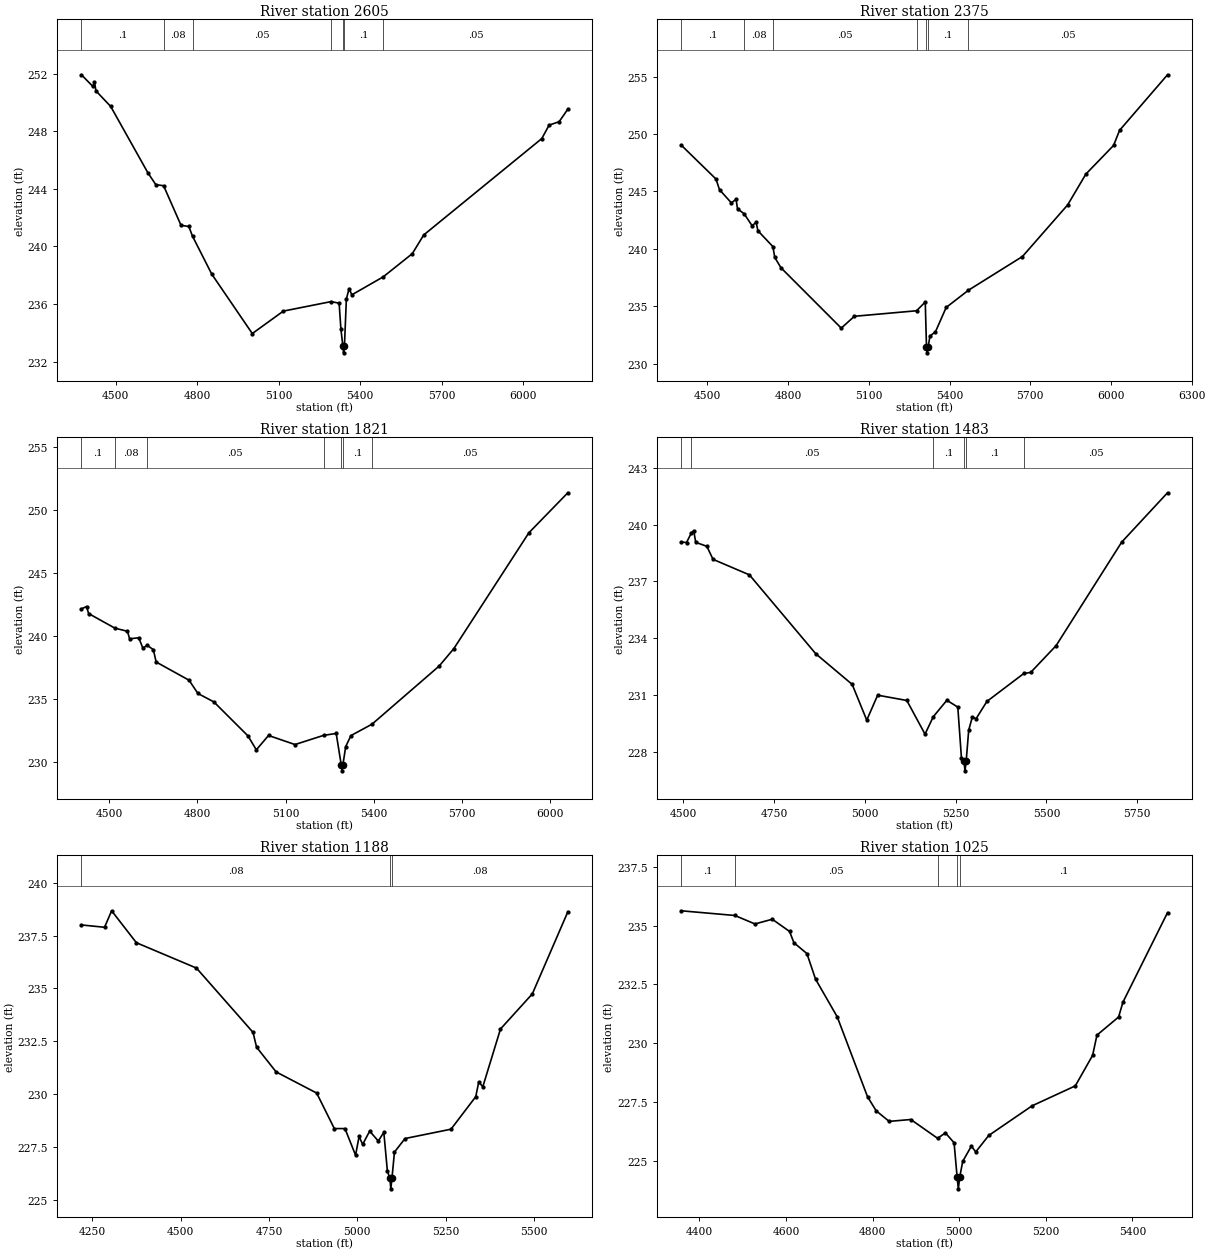
Type RM Length L Ch R = 1,2605,230,230,230
BEGIN DESCRIPTION:
Mapping XS 293d67fa
END DESCRIPTION:
XS GIS Cut Line= 5
      2258803.01     13387855.35      2259028.71     13387347.53
      2258967.95     13387134.86      2259002.67     13386735.56
      2258812.56     13386152.27
#Sta/Elev= 30
  4373.2  251.93  4415.3  251.12  4421.3  251.41  4426.7  250.81  4481.0  249.73
  4618.2  245.11  4647.0  244.30  4675.8  244.22  4740.0  241.47  4768.7  241.39
  4782.4  240.71  4853.1  238.08  5002.4  233.95  5116.8  235.51  5292.6  236.17
  5322.2  236.06  5328.8  234.25  5335.8  233.11  5338.6  232.61  5341.8  233.11
  5348.9  236.35  5358.9  237.08  5368.9  236.64  5484.6  237.89  5591.6  239.50
  5633.7  240.80  6068.6  247.50  6095.3  248.43  6132.4  248.67  6164.4  249.54
#Mann=7,-1,0
  4373.2     0.1       0  4675.8    0.08       0  4782.4    0.05       0
  5292.6     0.1       0  5335.8    0.03       0  5341.8     0.1       0
  5484.6    0.05       0
Bank Sta=5335.8,5341.8
Exp/Cntr=0.3,0.1

Type RM Length L Ch R = 1,2375,554,554,554
BEGIN DESCRIPTION:
UNT068 IN SUCR 2.0
END DESCRIPTION:
XS GIS Cut Line= 3
      2258987.71     13387796.89      2259237.72     13387246.85
      2259337.72     13386046.90
#Sta/Elev= 30
  4401.9  249.04  4531.6  246.08  4544.7  245.15  4588.7  244.01  4606.2  244.31
  4611.7  243.49  4636.2  243.06  4665.6  242.03  4680.9  242.30  4687.5  241.58
  4743.2  240.20  4750.1  239.26  4773.2  238.36  4997.3  233.11  5046.2  234.14
  5277.1  234.62  5309.6  235.38  5314.2  231.46  5316.9  230.96  5320.2  231.46
  5327.2  232.43  5347.3  232.78  5387.4  234.91  5470.3  236.41  5670.9  239.34
  5839.0  243.83  5906.7  246.51  6009.6  249.00  6032.1  250.32  6210.2  255.15
#Mann=7,-1,0
  4401.9     0.1       0  4636.2    0.08       0  4743.2    0.05       0
  5277.1     0.1       0  5314.2    0.03       0  5320.2     0.1       0
  5470.3    0.05       0
Bank Sta=5314.2,5320.2
Exp/Cntr=0.3,0.1

Type RM Length L Ch R = 1,1821,338,338,338
BEGIN DESCRIPTION:
Mapping XS d2aaca17
END DESCRIPTION:
XS GIS Cut Line= 4
      2259620.52     13387702.15      2259788.66     13387381.88
      2259724.61     13386429.17      2259605.08     13386110.43
#Sta/Elev= 30
  4404.7  242.15  4422.0  242.34  4429.3  241.78  4518.8  240.62  4561.6  240.37
  4568.8  239.77  4600.0  239.86  4614.0  239.03  4628.5  239.26  4649.8  238.91
  4659.2  237.93  4771.5  236.48  4801.5  235.43  4855.8  234.76  4971.9  232.06
  5000.5  230.95  5042.1  232.09  5132.3  231.37  5229.7  232.10  5272.6  232.25
  5289.6  229.78  5292.4  229.28  5295.6  229.78  5304.9  231.20  5322.7  232.08
  5394.7  232.99  5623.4  237.61  5673.5  239.00  5929.0  248.20  6061.7  251.38
#Mann=7,-1,0
  4404.7     0.1       0  4518.8    0.08       0  4628.5    0.05       0
  5229.7     0.1       0  5289.6    0.03       0  5295.6     0.1       0
  5394.7    0.05       0
Bank Sta=5289.6,5295.6
Exp/Cntr=0.3,0.1

Type RM Length L Ch R = 1,1483,295,295,295
BEGIN DESCRIPTION:
Mapping XS 36f01444
END DESCRIPTION:
XS GIS Cut Line= 3
      2260008.97     13387539.52      2260109.67     13387261.72
      2260043.76     13386220.99
#Sta/Elev= 30
  4494.7  239.09  4509.6  239.06  4523.1  239.57  4529.4  239.69  4534.9  239.07
  4565.5  238.86  4582.6  238.17  4682.7  237.35  4865.2  233.18  4965.4  231.56
  5005.5  229.67  5035.5  230.99  5115.7  230.71  5165.8  228.93  5188.5  229.85
  5225.9  230.72  5256.0  230.36  5266.0  227.68  5273.0  227.49  5275.8  226.99
  5279.0  227.49  5286.0  229.14  5296.1  229.84  5306.1  229.74  5336.1  230.66
  5437.9  232.14  5456.4  232.19  5526.5  233.61  5706.9  239.08  5833.0  241.69
#Mann=6,-1,0
  4494.7    0.08       0  4523.1    0.05       0  5188.5     0.1       0
  5273.0    0.03       0  5279.0     0.1       0  5437.9    0.05       0
Bank Sta=5273,5279
Exp/Cntr=0.3,0.1

Type RM Length L Ch R = 1,1188,163,163,163
BEGIN DESCRIPTION:
Mapping XS e963b96a
END DESCRIPTION:
XS GIS Cut Line= 2
      2260213.61     13387612.27      2260261.35     13386236.40
#Sta/Elev= 30
  4219.4  238.00  4284.9  237.89  4304.9  238.67  4374.9  237.16  4545.0  235.96
  4705.1  232.92  4715.1  232.22  4770.4  231.05  4885.2  230.05  4935.2  228.37
  4965.3  228.37  4995.3  227.11  5005.3  228.00  5015.3  227.62  5035.3  228.25
  5059.6  227.78  5075.3  228.19  5085.3  226.37  5092.3  226.02  5095.1  225.52
  5098.3  226.02  5105.4  227.26  5135.4  227.90  5265.4  228.34  5335.5  229.88
  5343.9  230.57  5355.5  230.35  5405.5  233.08  5495.6  234.74  5596.1  238.62
#Mann=3,-1,0
  4219.4    0.08       0  5092.3    0.07       0  5098.3    0.08       0
Bank Sta=5092.3,5098.3
Exp/Cntr=0.3,0.1

Type RM Length L Ch R = 1,1025,487,487,487
BEGIN DESCRIPTION:
Mapping XS 36ca5de8
END DESCRIPTION:
XS GIS Cut Line= 2
      2260352.88     13387427.49      2260352.88     13386303.89
#Sta/Elev= 30
  4357.5  235.63  4481.6  235.43  4528.1  235.07  4568.1  235.27  4608.1  234.75
  4618.1  234.27  4648.1  233.81  4668.1  232.72  4718.1  231.12  4788.1  227.72
  4808.1  227.12  4838.1  226.67  4888.1  226.75  4950.0  225.95  4968.1  226.18
  4988.1  225.76  4995.1  224.30  4997.9  223.80  5001.1  224.30  5008.1  224.97
  5028.1  225.62  5038.1  225.37  5068.1  226.07  5168.1  227.33  5268.1  228.18
  5308.1  229.48  5318.1  230.34  5368.1  231.11  5378.1  231.74  5481.1  235.55
#Mann=5,-1,0
  4357.5     0.1       0  4481.6    0.05       0  4950.0     0.1       0
  4995.1    0.07       0  5001.1     0.1       0
Bank Sta=4995.1,5001.1
Exp/Cntr=0.3,0.1

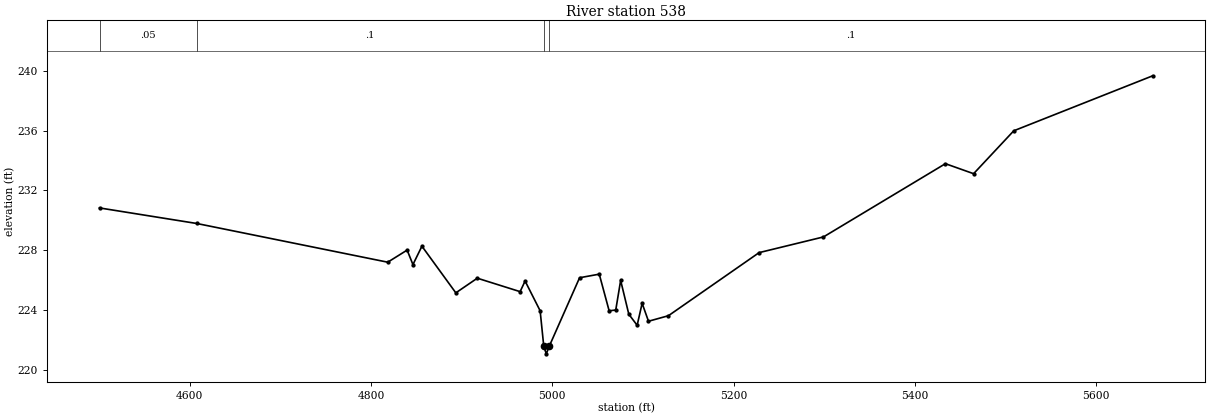
Type RM Length L Ch R = 1,538,0,0,0
BEGIN DESCRIPTION:
UNT068 IN SUCR 1.0
END DESCRIPTION:
XS GIS Cut Line= 4
      2260637.17     13387072.15      2260813.17     13386781.07
      2260562.72     13386192.17      2260400.29     13386110.96
#Sta/Elev= 30
  4500.6  230.83  4607.8  229.79  4818.5  227.20  4839.9  228.01  4846.3  227.04
  4856.2  228.27  4893.6  225.15  4917.3  226.13  4964.5  225.23  4970.0  225.94
  4986.6  223.95  4990.6  221.57  4993.4  221.07  4996.6  221.57  5030.1  226.16
  5051.8  226.40  5062.7  223.95  5070.0  224.00  5075.4  225.98  5084.4  223.72
  5093.6  222.98  5099.1  224.45  5106.1  223.25  5128.1  223.62  5228.1  227.84
  5299.1  228.89  5433.6  233.79  5464.7  233.12  5509.0  235.99  5662.3  239.67
#Mann=4,-1,0
  4500.6    0.05       0  4607.8     0.1       0  4990.6    0.07       0
  4996.6     0.1       0
Bank Sta=4990.6,4996.6
Exp/Cntr=0.3,0.1

Chan Stop Cuts=-1