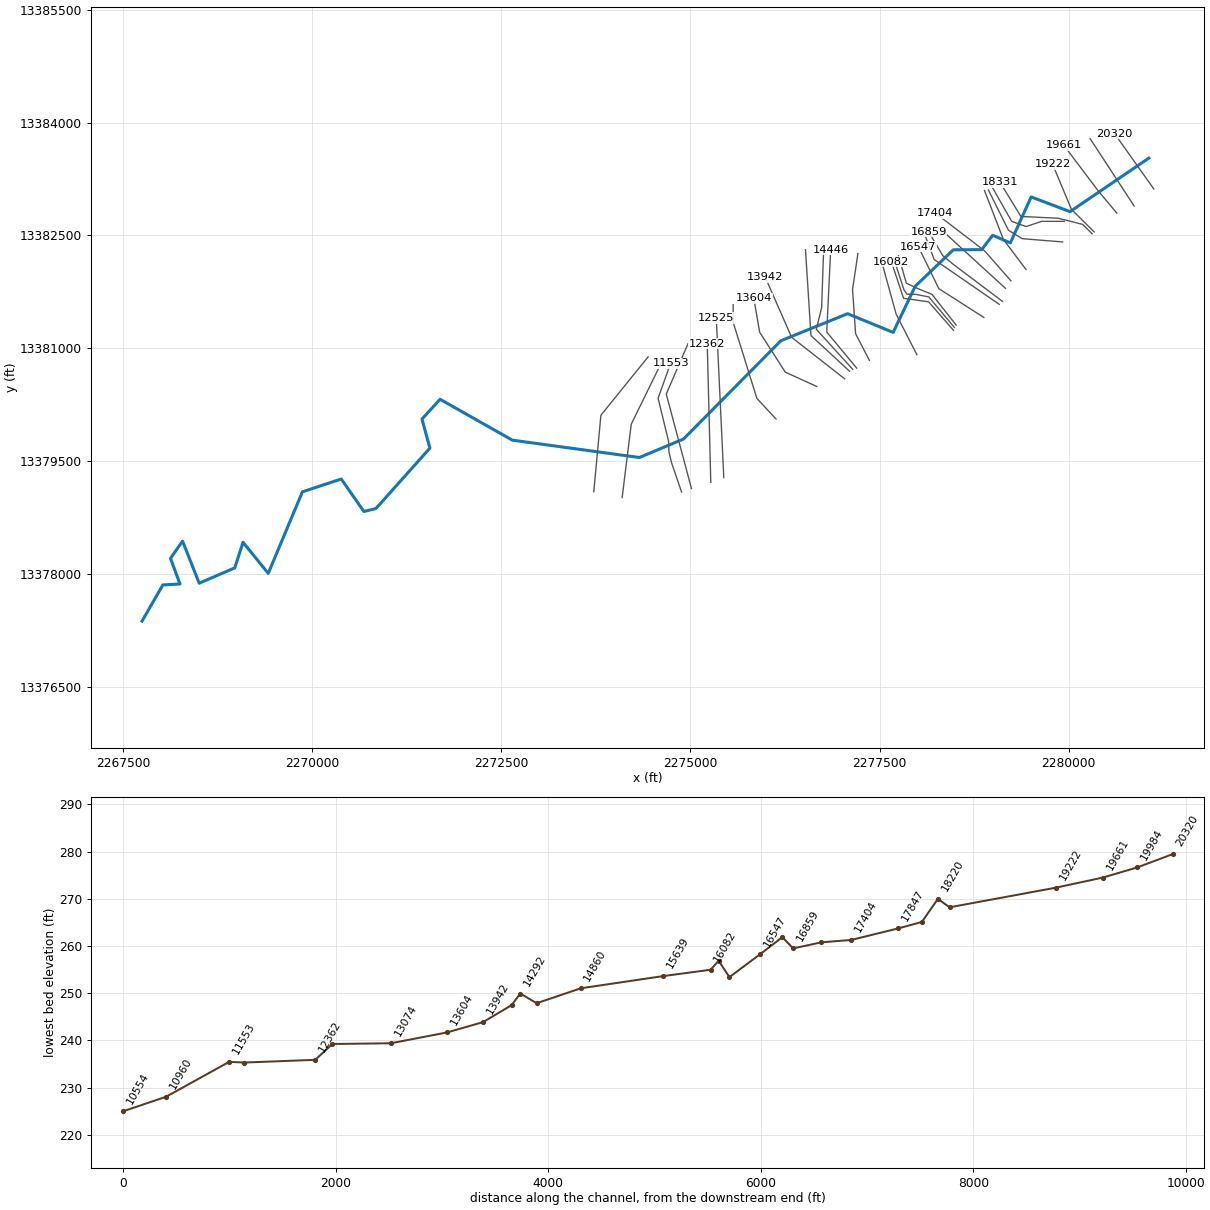
--- UNT069 IN SUCR.prj (project) ---

Proj Title=UNT069 IN SUCR Base Level Engineering
Current Plan=p01
Default Exp/Contr=0.3,0.1
English Units
Geom File=g01
Flow File=f01
Plan File=p01
Y Axis Title=Elevation
X Axis Title(PF)=Main Channel Distance
X Axis Title(XS)=Station
BEGIN DESCRIPTION:
UNT069 IN SUCR
END DESCRIPTION:
DSS Export Rating Curves= 0
DSS Export Rating Curve Sorted= 0
DSS Export Volume Flow Curves= 0
DXF OffsetX= 0
DXF OffsetY= 0
DXF ScaleX= 1
DXF ScaleY= 10

--- UNT069 IN SUCR.p01 (plan) ---

Plan Title=Multiple Run
Short Identifier=Multiple
Geom File=g01
Flow File=f01
Subcritical Flow
K Sum by GR= 0
Std Step Tol= 0.01
Critical Tol= 0.01
Num of Std Step Trials= 20
Max Error Tol= 0.3
Flow Tol Ratio= 0.001
Split Flow NTrial= 30
Split Flow Tol= 0.02
Split Flow Ratio= 0.02
Log Output Level= 0
Friction Slope Method= 1
Unsteady Friction Slope Method= 2
Unsteady Bridges Friction Slope Method= 1
Parabolic Critical Depth
Global Vel Dist=  1 , 1 , 1
Global Log Level= 0
CheckData=True
Encroach Param= -1, 0, 0, 0
BEGIN DESCRIPTION:
Multiple Run
END DESCRIPTION:

--- UNT069 IN SUCR.f01 (steady flow) ---

Flow Title=Multiple
Program Version=4.10
Number of Profiles= 7
Profile Names=10-year,25-year,50-year,1pct_min,100-year,1pct_plu,500-year
River Rch & RM=UNT069 IN SUCR,Reach-1         ,20320
     212     291     356     322     435     588     657
River Rch & RM=UNT069 IN SUCR,Reach-1         ,18331
     354     499     621     569     769    1040    1197
River Rch & RM=UNT069 IN SUCR,Reach-1         ,12362
     440     626     784     721     975    1318    1531
Boundary for River Rch & Prof#=UNT069 IN SUCR,Reach-1         , 1
Up Type= 0
Dn Type= 3
Dn Slope=0.0053
Boundary for River Rch & Prof#=UNT069 IN SUCR,Reach-1         , 2
Up Type= 0
Dn Type= 3
Dn Slope=0.0053
Boundary for River Rch & Prof#=UNT069 IN SUCR,Reach-1         , 3
Up Type= 0
Dn Type= 3
Dn Slope=0.0053
Boundary for River Rch & Prof#=UNT069 IN SUCR,Reach-1         , 4
Up Type= 0
Dn Type= 3
Dn Slope=0.0053
Boundary for River Rch & Prof#=UNT069 IN SUCR,Reach-1         , 5
Up Type= 0
Dn Type= 3
Dn Slope=0.0053
Boundary for River Rch & Prof#=UNT069 IN SUCR,Reach-1         , 6
Up Type= 0
Dn Type= 3
Dn Slope=0.0053
Boundary for River Rch & Prof#=UNT069 IN SUCR,Reach-1         , 7
Up Type= 0
Dn Type= 3
Dn Slope=0.0053
DSS Import GetInterval= 0
DSS Import GetPeak= 0
DSS Import FillOption= 0

--- UNT069 IN SUCR.g01 (geometry) ---

Geom Title=Existing Conditions
Program Version=4.10

River Reach=UNT069 IN SUCR  ,Reach-1
Reach XY= 30
      2281061.09     13383527.12      2280019.42     13382816.18
      2279505.18     13383011.24      2279229.14     13382400.29
      2278997.12     13382502.93      2278850.57     13382311.31
      2278475.76     13382309.45      2277972.54     13381825.73
      2277680.06      13381212.4      2277078.08     13381460.51
      2276194.97     13381101.26      2274908.14     13379796.05
      2274323.95     13379550.39      2272644.65     13379780.83
      2271689.03     13380323.83      2271449.67     13380060.87
       2271554.5     13379675.23      2270840.34     13378871.91
      2270681.38     13378833.94      2270382.31     13379265.21
      2269868.69     13379094.49      2269416.94     13378011.48
      2269083.66     13378424.21       2268974.1     13378084.35
      2268504.38     13377880.82      2268283.96     13378439.66
      2268124.19     13378210.49      2268250.06     13377870.86
      2268023.28     13377857.84      2267747.72     13377376.85

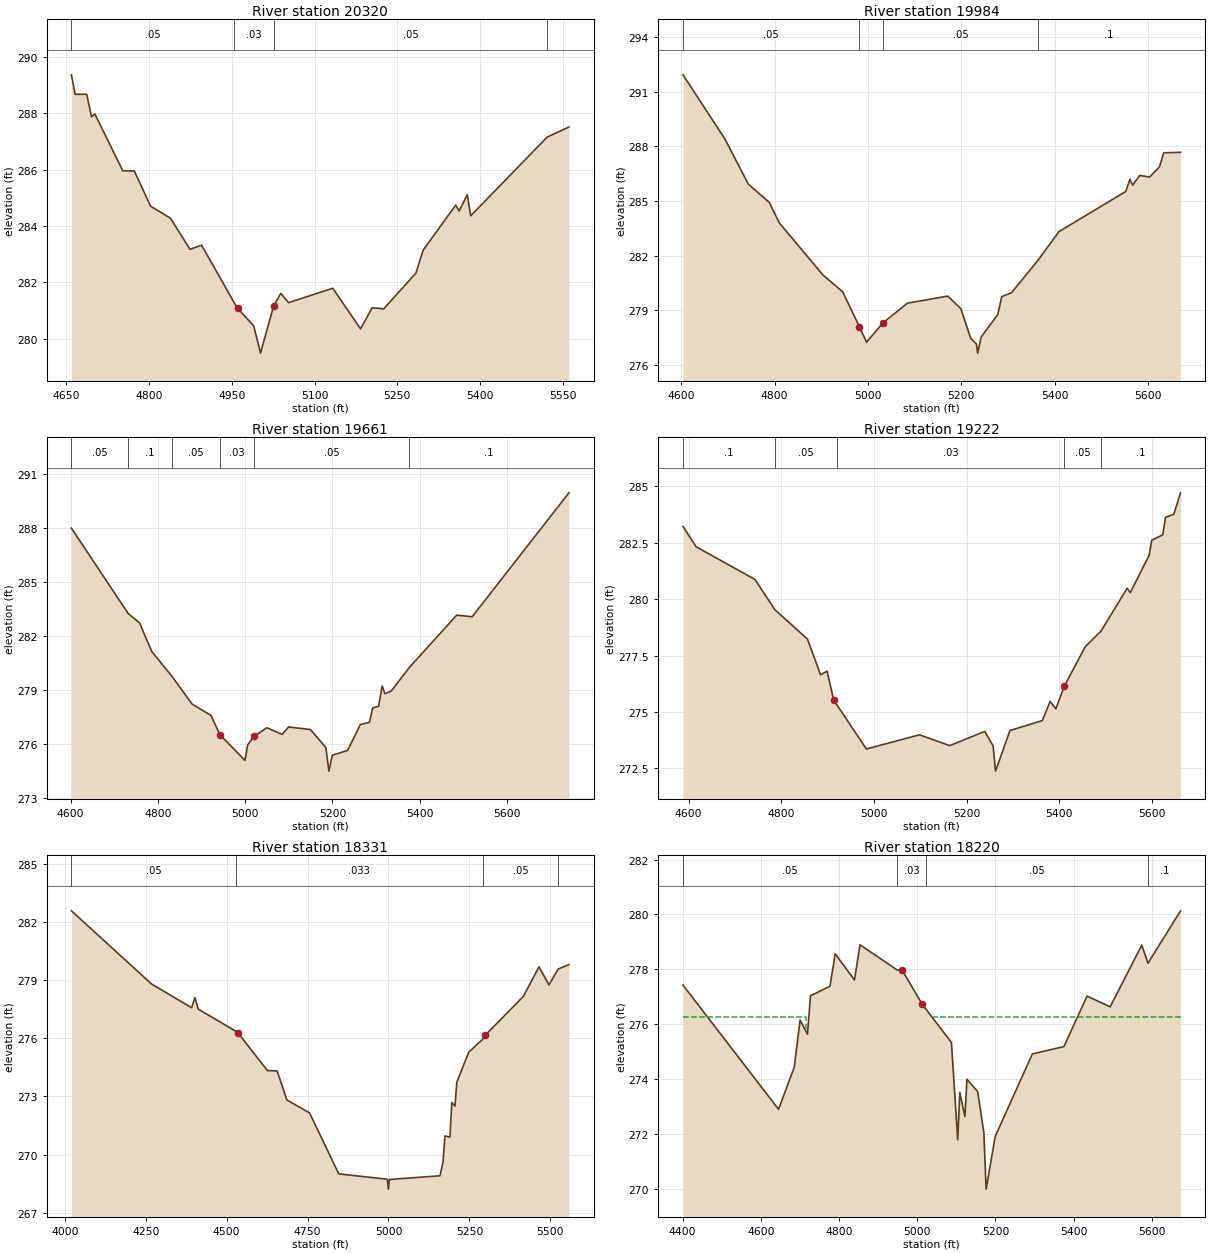
Type RM Length L Ch R = 1 ,20320   ,336,336,336
BEGIN DESCRIPTION:
UNT069 IN SUCR 34.0
END DESCRIPTION:
XS GIS Cut Line= 2
      2281127.06     13383116.91      2280607.24     13383853.33
#Sta/Elev= 30
  4659.5  289.36  4666.3  288.67  4687.2  288.67  4695.9  287.87    4702  287.97
  4752.5  285.96  4773.4  285.95    4803   284.7  4838.7  284.28  4874.4  283.17
  4895.3  283.32  4953.2  281.32  4960.6  281.08  4989.9  280.45  5002.1  279.49
  5025.8  281.16  5038.9  281.61  5052.9  281.28    5133  281.79  5183.4  280.35
  5204.4   281.1  5225.3  281.06  5283.7  282.33  5296.7  283.14  5355.8  284.74
    5362  284.53  5376.7  285.11  5382.9  284.36  5521.4  287.15  5560.9  287.51
#Mann= 4 ,-1 , 0
  4659.5     .05       0  4953.2     .03       0  5025.8     .05       0
  5521.4      .1       0
Bank Sta=4960.6,5025.8
XS Rating Curve= 0 ,0
Exp/Cntr=0.3,0.1

Type RM Length L Ch R = 1 ,19984   ,323,323,323
BEGIN DESCRIPTION:
Mapping XS 69c3d571
END DESCRIPTION:
XS GIS Cut Line= 2
      2280866.69     13382891.16       2280285.1     13383785.25
#Sta/Elev= 30
  4603.5  291.92  4693.8  288.38  4743.3  285.93  4788.7  284.91  4809.8   283.8
  4903.4  280.94  4945.6  280.02  4981.8  278.09    4997  277.25 5032.19  278.31
  5084.6  279.39    5171  279.78  5199.2  279.09  5220.3  277.46  5232.5  277.15
  5235.2  276.65  5242.6  277.53  5278.3  278.77  5286.8  279.75  5307.9  279.97
  5363.8  281.72  5409.6  283.32  5552.7  285.52  5561.6  286.19  5567.5  285.87
  5582.7   286.4  5603.8  286.31  5624.9  286.87    5634  287.64  5670.1  287.67
#Mann= 4 ,-1 , 0
  4603.5     .05       0  4981.8     .03       0 5032.19     .05       0
  5363.8      .1       0
Bank Sta=4981.8,5032.19
XS Rating Curve= 0 ,0
Exp/Cntr=0.3,0.1

Type RM Length L Ch R = 1 ,19661   ,439,439,439
BEGIN DESCRIPTION:
UNT069 IN SUCR 33.0
END DESCRIPTION:
XS GIS Cut Line= 3
      2280637.72     13382796.85      2280387.72     13383096.85
      2279937.73     13383696.84
#Sta/Elev= 30
  4601.8     288  4731.9  283.26    4758  282.74    4786  281.15    4833  279.75
  4878.4  278.23  4921.4  277.61  4942.2  276.53  4999.6  275.11  5005.9  275.97
  5020.4  276.44  5049.6  276.92    5085  276.55  5099.6  276.96  5149.6  276.82
    5185  275.82  5192.1  274.51  5199.6  275.39    5235  275.66  5264.2   277.1
    5285  277.22  5292.3  278.01  5305.9  278.11  5314.2  279.24  5320.4  278.81
    5335  278.96  5376.7  280.27    5485  283.17  5520.4  283.08  5742.3  289.96
#Mann= 6 ,-1 , 0
  4601.8     .05       0  4731.9      .1       0    4833     .05       0
  4942.2     .03       0  5020.4     .05       0  5376.7      .1       0
Bank Sta=4942.2,5020.4
XS Rating Curve= 0 ,0
Exp/Cntr=0.3,0.1

Type RM Length L Ch R = 1 ,19222   ,1002,1002,1002
BEGIN DESCRIPTION:
UNT069 IN SUCR 32.0
END DESCRIPTION:
XS GIS Cut Line= 3
       2280337.7     13382546.88      2280037.72     13382846.85
      2279787.73     13383446.83
#Sta/Elev= 30
  4587.8  283.22  4616.1  282.32  4743.3  280.87  4785.8  279.54  4856.5  278.23
  4884.8  276.65  4898.9  276.81    4913  275.54    4920  275.32  4983.7  273.36
  5098.2  273.99  5163.7  273.51  5239.5  274.14  5257.4  273.49  5262.6  272.38
  5293.7  274.18  5363.6  274.62  5380.4  275.47  5392.8  275.14  5411.2  276.15
  5456.2  277.89  5490.5  278.59  5546.7  280.48  5553.7  280.29  5594.3  281.95
  5599.7  282.61  5623.6  282.85  5629.5  283.62  5647.4  283.76    5662  284.71
#Mann= 5 ,-1 , 0
  4587.8      .1       0  4785.8     .05       0    4920     .03       0
  5411.2     .05       0  5490.5      .1       0
Bank Sta=4913,5411.2
XS Rating Curve= 0 ,0
Exp/Cntr=0.3,0.1

Type RM Length L Ch R = 1 ,18331   ,111,111,111
BEGIN DESCRIPTION:
UNT069 IN SUCR 31.0
END DESCRIPTION:
XS GIS Cut Line= 5
      2280311.79     13382522.01      2280185.08     13382646.98
      2279863.71     13382728.18      2279369.28     13382752.29
      2279092.11     13383207.02
#Sta/Elev= 30
  4020.5   282.6  4267.9  278.82  4391.7  277.59    4402  278.11  4412.3  277.52
  4529.9  276.36  4535.9  276.27    4626  274.34  4656.1  274.32  4686.1  272.82
  4756.2  272.15  4846.3     269  4996.5  268.72  4999.8  268.21    5003  268.71
  5159.1   268.9  5168.5   269.6  5174.4  270.96  5189.8   270.9  5195.7  272.69
  5205.3   272.5  5211.2  273.74  5247.9  275.29  5290.6  275.95  5299.7  276.18
  5416.4  278.17  5464.9   279.7  5495.8  278.77  5524.1  279.59  5557.5  279.82
#Mann= 4 ,-1 , 0
  4020.5     .05       0  4529.9    .033       0  5290.6     .05       0
  5524.1      .1       0
Bank Sta=4535.9,5299.7
XS Rating Curve= 0 ,0
Exp/Cntr=0.3,0.1

Type RM Length L Ch R = 1 ,18220   ,151,151,151
BEGIN DESCRIPTION:
UNT069 IN SUCR 30.0
END DESCRIPTION:
XS GIS Cut Line= 5
      2279942.16     13382687.19      2279642.71     13382687.19
      2279438.72     13382617.75      2279247.75     13382687.19
      2278974.31     13383168.96
#Sta/Elev= 30
  4401.1  277.42  4645.5  272.89  4685.5  274.43  4700.5  276.15  4719.4  275.63
    4727  277.03  4776.8  277.38  4790.3  278.56  4839.5  277.61  4853.7  278.89
    4949  277.97  4961.2  277.97  5011.7  276.75  5023.5  276.52  5087.4  275.33
  5103.5  271.78  5108.8  273.51  5121.9  272.63    5127  273.99  5154.4  273.54
  5170.3  272.05  5176.1  269.98  5199.3   271.9  5294.3  274.91  5375.1  275.18
  5434.2  277.02  5493.3  276.63  5574.1  278.88    5590  278.22  5673.2  280.13
#Mann= 4 ,-1 , 0
  4401.1     .05       0    4949     .03       0  5023.5     .05       0
    5590      .1       0
#XS Ineff= 2 , 0
       0    4715  276.24 5040.34       0  276.25
Permanent Ineff=
       T       T
Bank Sta=4961.2,5011.7
XS Rating Curve= 0 ,0
Exp/Cntr=0.3,0.1

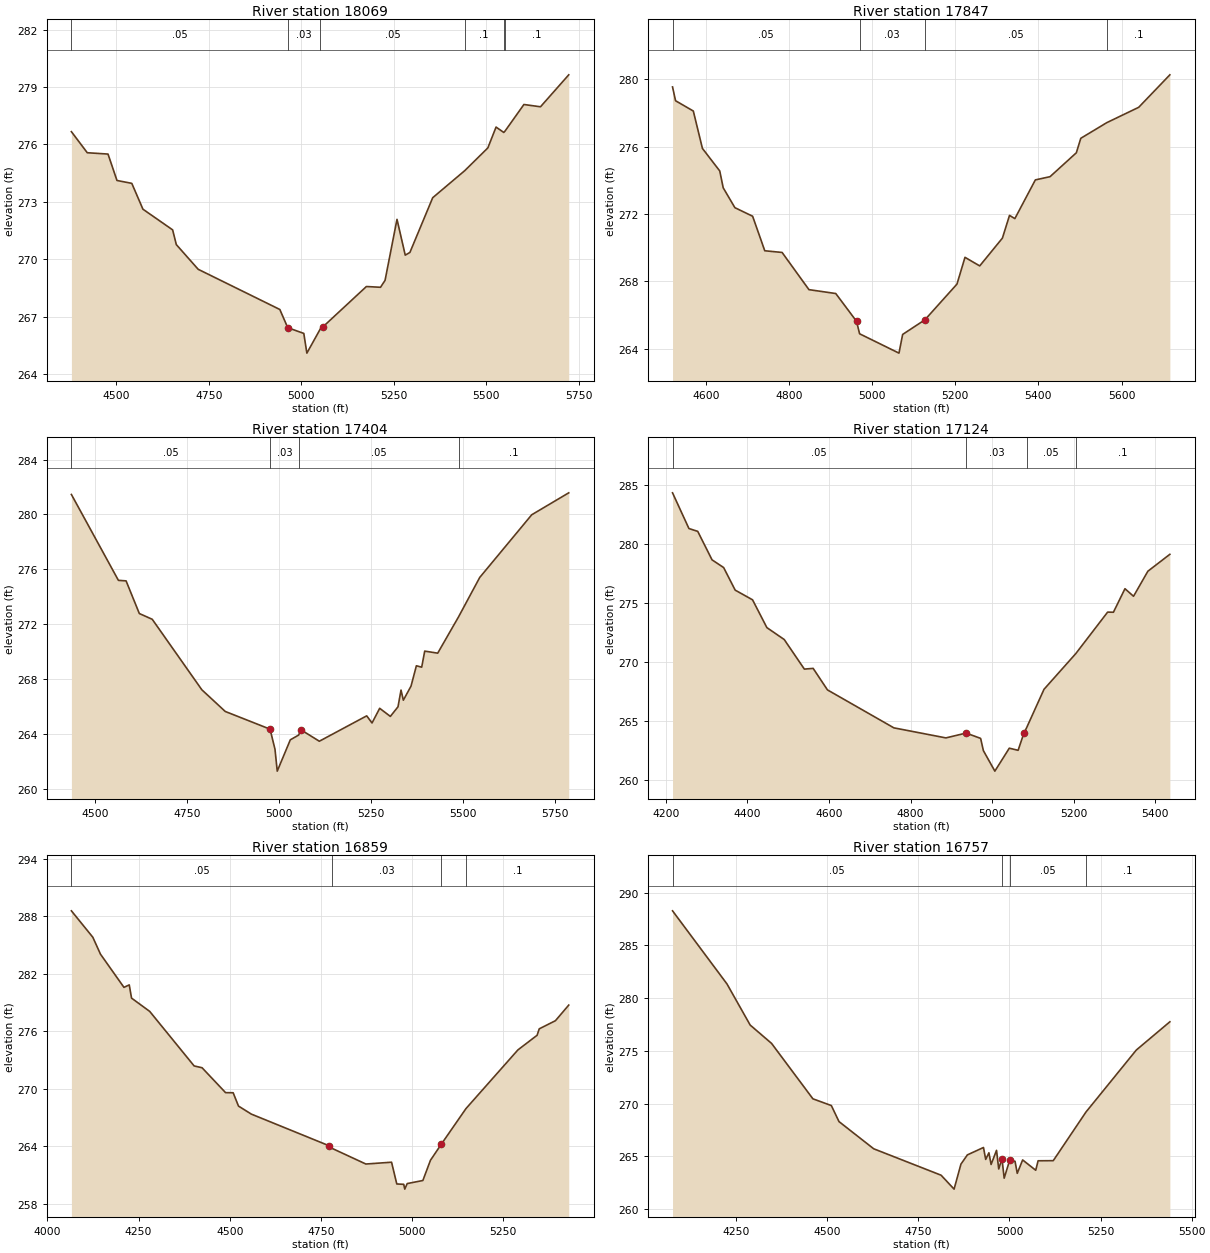
Type RM Length L Ch R = 1 ,18069   ,222,222,222
BEGIN DESCRIPTION:
Mapping XS fb15decf
END DESCRIPTION:
XS GIS Cut Line= 4
      2279920.47     13382413.75      2279386.64     13382457.16
      2279204.35       13382570.      2278940.07     13383102.88
#Sta/Elev= 30
  4378.4  276.67  4421.3  275.57  4477.4   275.5  4501.6  274.12  4541.7  273.97
  4571.8  272.62  4652.1  271.54  4662.1  270.77  4721.2  269.48    4942  267.38
  4963.3  266.43  5006.8  266.13  5015.1   265.1  5051.9  266.38  5057.8  266.46
  5176.1  268.58  5214.2  268.54  5226.5   268.9  5258.8  272.09  5281.1  270.22
  5293.7  270.36  5355.4  273.22  5441.8  274.63  5504.4  275.82  5526.7  276.91
  5547.5  276.63  5550.5  276.69    5602  278.09  5646.8  277.97  5723.2  279.64
#Mann= 6 ,-1 , 0
  4378.4     .05       0  4963.3     .03       0  5051.9     .05       0
  5441.8      .1       0  5547.5     .05       0  5550.5      .1       0
Bank Sta=4963.3,5057.8
XS Rating Curve= 0 ,0
Exp/Cntr=0.3,0.1

Type RM Length L Ch R = 1 ,17847   ,443,443,443
BEGIN DESCRIPTION:
UNT069 IN SUCR 29.0
END DESCRIPTION:
XS GIS Cut Line= 3
      2279437.74     13382046.82      2279137.72     13382446.85
      2278887.71     13383096.89
#Sta/Elev= 30
  4519.8  279.55  4527.1  278.73  4569.8  278.12  4591.7   275.9  4633.4  274.56
  4641.7  273.56  4669.8  272.38  4712.5  271.87  4741.7  269.82  4783.4  269.72
    4848  267.51  4912.5  267.28  4962.5  265.63  4969.8  264.89  5064.6  263.74
  5073.4  264.85    5127  265.72  5204.1  267.84  5223.4  269.43  5258.8  268.92
  5313.4  270.57  5330.5  271.92  5343.4  271.73  5392.7  274.03    5428  274.22
  5491.3  275.64    5502   276.5  5564.6  277.43  5641.3  278.34  5716.3  280.27
#Mann= 4 ,-1 , 0
  4519.8     .05       0  4969.8     .03       0    5127     .05       0
  5564.6      .1       0
Bank Sta=4962.5,5127
XS Rating Curve= 0 ,0
Exp/Cntr=0.3,0.1

Type RM Length L Ch R = 1 ,17404   ,280,280,280
BEGIN DESCRIPTION:
UNT069 IN SUCR 28.0
END DESCRIPTION:
XS GIS Cut Line= 3
      2279237.74     13381896.84      2278887.72     13382296.85
      2278237.71     13382796.86
#Sta/Elev= 30
    4436  281.46  4563.7   275.2  4584.6  275.16  4620.6  272.78  4655.7  272.36
  4790.5  267.22  4854.1  265.64 4975.91  264.35  4989.3  262.88  4995.4  261.29
  5030.9  263.57  5053.6  263.92  5059.9   264.3  5109.8  263.47  5238.5  265.32
    5253   264.8  5273.8  265.87  5302.8  265.28  5323.6  265.98  5331.8   267.2
  5338.1  266.46    5359  267.49  5373.5  268.97    5388  268.87  5396.2  270.04
  5431.5  269.89  5488.4  272.55  5545.7  275.41    5687  279.98  5787.6  281.58
#Mann= 4 ,-1 , 0
    4436     .05       0 4975.91     .03       0  5053.6     .05       0
  5488.4      .1       0
Bank Sta=4975.91,5059.9
XS Rating Curve= 0 ,0
Exp/Cntr=0.3,0.1

Type RM Length L Ch R = 1 ,17124   ,265,265,265
BEGIN DESCRIPTION:
Mapping XS 8b0f82c5
END DESCRIPTION:
XS GIS Cut Line= 2
      2279165.31     13381797.41      2278266.96     13382621.98
#Sta/Elev= 30
  4216.4  284.33  4256.6  281.31  4278.2  281.07  4313.3  278.66  4341.7  278.01
    4370   276.1  4412.6  275.28  4447.7  272.93  4490.3  271.92  4539.6  269.42
  4561.2  269.48  4596.3  267.66  4759.1  264.45  4886.7   263.6  4936.1  264.01
  4971.8  263.56  4978.6  262.52  5006.7  260.79  5042.1  262.73  5063.7  262.55
  5077.9     264  5084.7  264.47  5127.2  267.71  5205.1  270.73  5283.2  274.24
  5297.4  274.23  5325.7  276.22  5346.7  275.58  5381.9   277.7  5435.8  279.13
#Mann= 4 ,-1 , 0
  4216.4     .05       0  4936.1     .03       0  5084.7     .05       0
  5205.1      .1       0
Bank Sta=4936.1,5077.9
XS Rating Curve= 0 ,0
Exp/Cntr=0.3,0.1

Type RM Length L Ch R = 1 ,16859   ,102,102,102
BEGIN DESCRIPTION:
UNT069 IN SUCR 27.0
END DESCRIPTION:
XS GIS Cut Line= 4
      2279126.25      13381623.8       2278466.5     13382122.95
      2278336.29     13382231.46      2278149.67     13382548.29
#Sta/Elev= 30
  4065.7  288.56  4124.5   285.8  4145.4  284.04  4209.9  280.57  4224.4  280.83
  4230.7  279.45  4280.6  278.06  4402.4  272.37  4424.2  272.18  4488.7  269.58
  4509.5  269.57  4524.1  268.18  4559.4  267.34  4773.8  264.02    4780  263.78
  4873.6  262.13  4944.1  262.32  4958.4  260.05  4977.5  260.01  4980.3  259.51
    4987  260.09    5030  260.41  5050.8  262.52  5080.4  264.19  5148.3  267.92
  5290.7  274.04  5343.4  275.57  5349.2  276.24  5393.7  277.09  5430.2  278.72
#Mann= 4 ,-1 , 0
  4065.7     .05       0    4780     .03       0  5080.4     .05       0
  5148.3      .1       0
Bank Sta=4773.8,5080.4
XS Rating Curve= 0 ,0
Exp/Cntr=0.3,0.1

Type RM Length L Ch R = 1 ,16757   ,210,210,210
BEGIN DESCRIPTION:
UNT069 IN SUCR 26.0
END DESCRIPTION:
XS GIS Cut Line= 4
      2279082.81     13381584.77      2278431.78     13382036.15
      2278223.44     13382179.38      2278110.58      13382478.9
#Sta/Elev= 30
  4075.1  288.29  4224.6  281.35  4288.2  277.45  4346.9  275.71  4460.4  270.45
    4511  269.81    4532  268.29  4627.2  265.71  4812.3   263.2  4847.9  261.88
  4866.7  264.25  4884.4  265.13  4928.6  265.83  4934.7   264.7  4943.5  265.33
  4949.5  264.22  4964.4  265.56  4970.5  263.79  4979.3  264.78  4985.4  262.92
  5000.3   264.6  5015.2  264.52  5021.3  263.38  5036.1  264.65    5072  263.67
  5078.5  264.57  5120.1  264.58    5210   269.2  5348.1  275.08  5440.2  277.76
#Mann= 4 ,-1 , 0
  4075.1     .05       0  4979.3     .03       0  5000.3     .05       0
    5210      .1       0
Bank Sta=4979.3,5000.3
XS Rating Curve= 0 ,0
Exp/Cntr=0.3,0.1

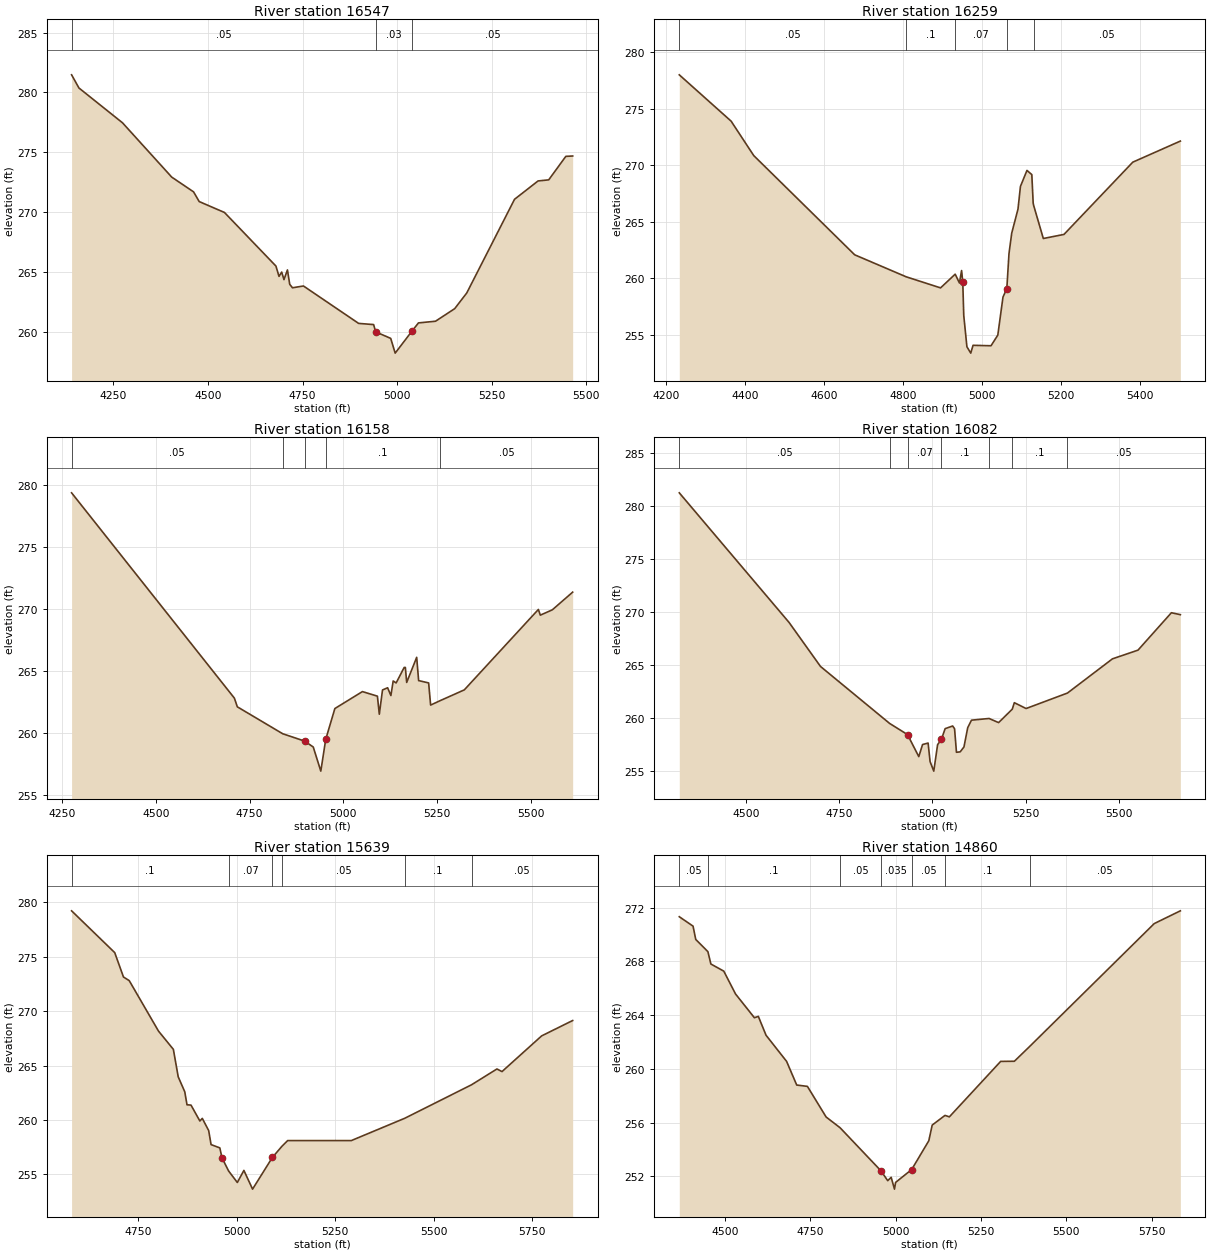
Type RM Length L Ch R = 1 ,16547   ,288,288,288
BEGIN DESCRIPTION:
Mapping XS fb93ada3
END DESCRIPTION:
XS GIS Cut Line= 3
      2278878.86     13381411.12      2278284.21     13381793.09
      2278015.09     13382348.68
#Sta/Elev= 30
  4139.6  281.47  4159.1  280.37  4274.1  277.47  4404.2  272.94  4461.9  271.71
  4476.8   270.9  4543.6  269.99  4679.6  265.52  4687.7  264.66  4694.8  265.02
  4700.8  264.39    4710   265.2    4716     264  4723.3  263.71  4752.3  263.86
  4898.1  260.74  4937.7  260.64  4943.3  260.03  4982.9  259.49  4994.7  258.26
  5039.4  260.11  5056.2  260.78  5101.3  260.92    5152  261.97  5183.9  263.28
  5310.1  271.09  5372.3  272.62  5400.4  272.71  5445.6  274.67  5463.7   274.7
#Mann= 3 , 0 , 0
  4139.6     .05       0  4943.3     .03       0  5039.4     .05       0
Bank Sta=4943.3,5039.4
XS Rating Curve= 0 ,0
Exp/Cntr=0.3,0.1

Type RM Length L Ch R = 1 ,16259   ,101,101,101
BEGIN DESCRIPTION:
Mapping XS b0f44c37
END DESCRIPTION:
XS GIS Cut Line= 5
       2278513.5     13381308.44      2278193.17     13381717.32
      2277997.85     13381798.05      2277854.63     13381865.76
      2277750.45     13382230.38
#Sta/Elev= 30
  4233.3  277.98  4364.5  273.89  4421.8  270.85  4677.3  262.09  4807.5  260.15
  4894.7  259.17  4931.7  260.38  4942.5   259.6  4947.9   260.7 4950.91  259.69
  4953.4  256.73  4961.4  253.97  4971.1  253.41  4976.9   254.1  5022.4  254.06
  5039.6     255  5052.7  258.36  5062.4   259.1  5067.9   262.2  5074.8     264
  5090.7  266.13  5096.9  268.13  5113.4  269.54  5125.7  269.17  5129.1  266.66
  5130.5  266.43  5154.8  263.53  5207.1  263.89  5381.3  270.27  5501.7  272.13
#Mann= 5 ,-1 , 0
  4233.3     .05       0  4807.5      .1       0  4931.7     .07       0
  5062.4      .1       0  5130.5     .05       0
Bank Sta=4950.91,5062.4
XS Rating Curve= 0 ,0
Exp/Cntr=0.3,0.1

Type RM Length L Ch R = 1 ,16158   ,76,76,76
BEGIN DESCRIPTION:
Mapping XS 66db8225
END DESCRIPTION:
XS GIS Cut Line= 6
      2278490.07     13381277.18       2278151.5     13381683.47
      2277979.63     13381717.32      2277862.44     13381719.92
      2277823.38     13381777.22      2277685.34     13382201.74
#Sta/Elev= 30
  4275.3  279.39  4709.7  262.79  4717.5  262.09  4838.7  259.91    4897  259.32
  4920.1  258.84  4940.3  256.89  4953.4  259.46  4977.8  261.95  5051.3  263.32
  5091.3  262.95  5096.4  261.49  5104.9  263.45  5118.5  263.63  5127.3     263
  5133.4  264.18  5141.3  264.02  5162.7  265.27  5165.9  265.27  5169.4  264.06
  5196.1  266.09  5201.3  264.21    5228  264.02  5233.3  262.23  5258.2  262.58
  5323.2  263.46  5520.8  269.96    5526   269.5    5558  269.93  5612.3  271.36
#Mann= 5 ,-1 , 0
  4275.3     .05       0  4838.7      .1       0    4897     .07       0
  4953.4      .1       0  5258.2     .05       0
Bank Sta=4897,4953.4
XS Rating Curve= 0 ,0
Exp/Cntr=0.3,0.1

Type RM Length L Ch R = 1 ,16082   ,443,443,443
BEGIN DESCRIPTION:
UNT069 IN SUCR 25.0
END DESCRIPTION:
XS GIS Cut Line= 4
        2278477.     13381240.78       2278148.9     13381618.36
      2277818.17     13381665.24      2277656.72     13382149.58
#Sta/Elev= 30
  4320.8  281.25  4615.3  269.02  4699.8  264.86  4885.4  259.48  4933.3  258.43
  4963.6  256.35  4973.7  257.49  4988.6  257.63  4993.9  255.88  5003.8  254.98
  5014.1  257.48  5024.2  257.97  5034.3  258.99  5054.5  259.24  5059.6  258.98
  5064.7  256.76  5074.7   256.8  5084.8  257.26  5094.9  259.08    5105  259.79
  5152.2  259.95  5177.8  259.56  5214.5  260.83    5220  261.44  5251.6  260.89
  5362.6  262.35  5483.4  265.58  5551.9   266.4  5641.5  269.93  5665.6  269.75
#Mann= 7 ,-1 , 0
  4320.8     .05       0  4885.4      .1       0  4933.3     .07       0
  5024.2      .1       0  5152.2     .05       0  5214.5      .1       0
  5362.6     .05       0
Bank Sta=4933.3,5024.2
XS Rating Curve= 0 ,0
Exp/Cntr=0.3,0.1

Type RM Length L Ch R = 1 ,15639   ,779,779,779
BEGIN DESCRIPTION:
UNT069 IN SUCR 24.0
END DESCRIPTION:
XS GIS Cut Line= 3
      2277993.43     13380916.32      2277719.97     13381454.55
      2277542.38     13382099.95
#Sta/Elev= 30
  4580.4  279.22    4690  275.38  4712.2  273.14  4726.8  272.81  4801.2  268.17
    4839  266.49  4851.3  263.97    4868  262.59  4873.6   261.4  4883.8  261.37
  4906.3  259.91  4912.5  260.15  4928.7  259.03  4934.8  257.74    4957  257.44
  4962.6  256.52  4979.3  255.32  5001.5  254.26  5018.2  255.37  5040.2  253.65
  5090.5  256.56  5115.2   257.6  5129.4  258.11  5291.1  258.11  5426.9  260.16
  5596.7  263.24  5661.1  264.69    5674  264.45  5774.7  267.73  5853.5  269.14
#Mann= 6 ,-1 , 0
  4580.4      .1       0  4979.3     .07       0  5090.5      .1       0
  5115.2     .05       0  5426.9      .1       0  5596.7     .05       0
Bank Sta=4962.6,5090.5
XS Rating Curve= 0 ,0
Exp/Cntr=0.3,0.1

Type RM Length L Ch R = 1 ,14860   ,414,414,414
BEGIN DESCRIPTION:
UNT069 IN SUCR 23.0
END DESCRIPTION:
XS GIS Cut Line= 4
      2277365.77     13380841.02      2277183.61     13381195.23
      2277143.13     13381782.13      2277213.96     13382257.68
#Sta/Elev= 30
  4366.3  271.33  4406.6  270.63  4414.5  269.64  4450.1  268.73  4458.8  267.81
  4496.6  267.28    4531  265.58  4586.3  263.81  4597.8  263.91  4620.3  262.51
  4680.6  260.56  4710.2   258.8  4741.5   258.7  4796.3  256.42  4837.2  255.62
  4956.7  252.42  4976.7  251.68  4986.8  251.93  4996.5  251.05  4999.8  251.55
  5046.9  252.51    5097  254.65    5107  255.82  5144.5  256.54  5157.2  256.43
  5307.5  260.56  5347.6  260.57  5391.9  261.66  5757.2  270.82  5833.7  271.77
#Mann= 7 ,-1 , 0
  4366.3     .05       0  4450.1      .1       0  4837.2     .05       0
  4956.7    .035       0  5046.9     .05       0  5144.5      .1       0
  5391.9     .05       0
Bank Sta=4956.7,5046.9
XS Rating Curve= 0 ,0
Exp/Cntr=0.3,0.1

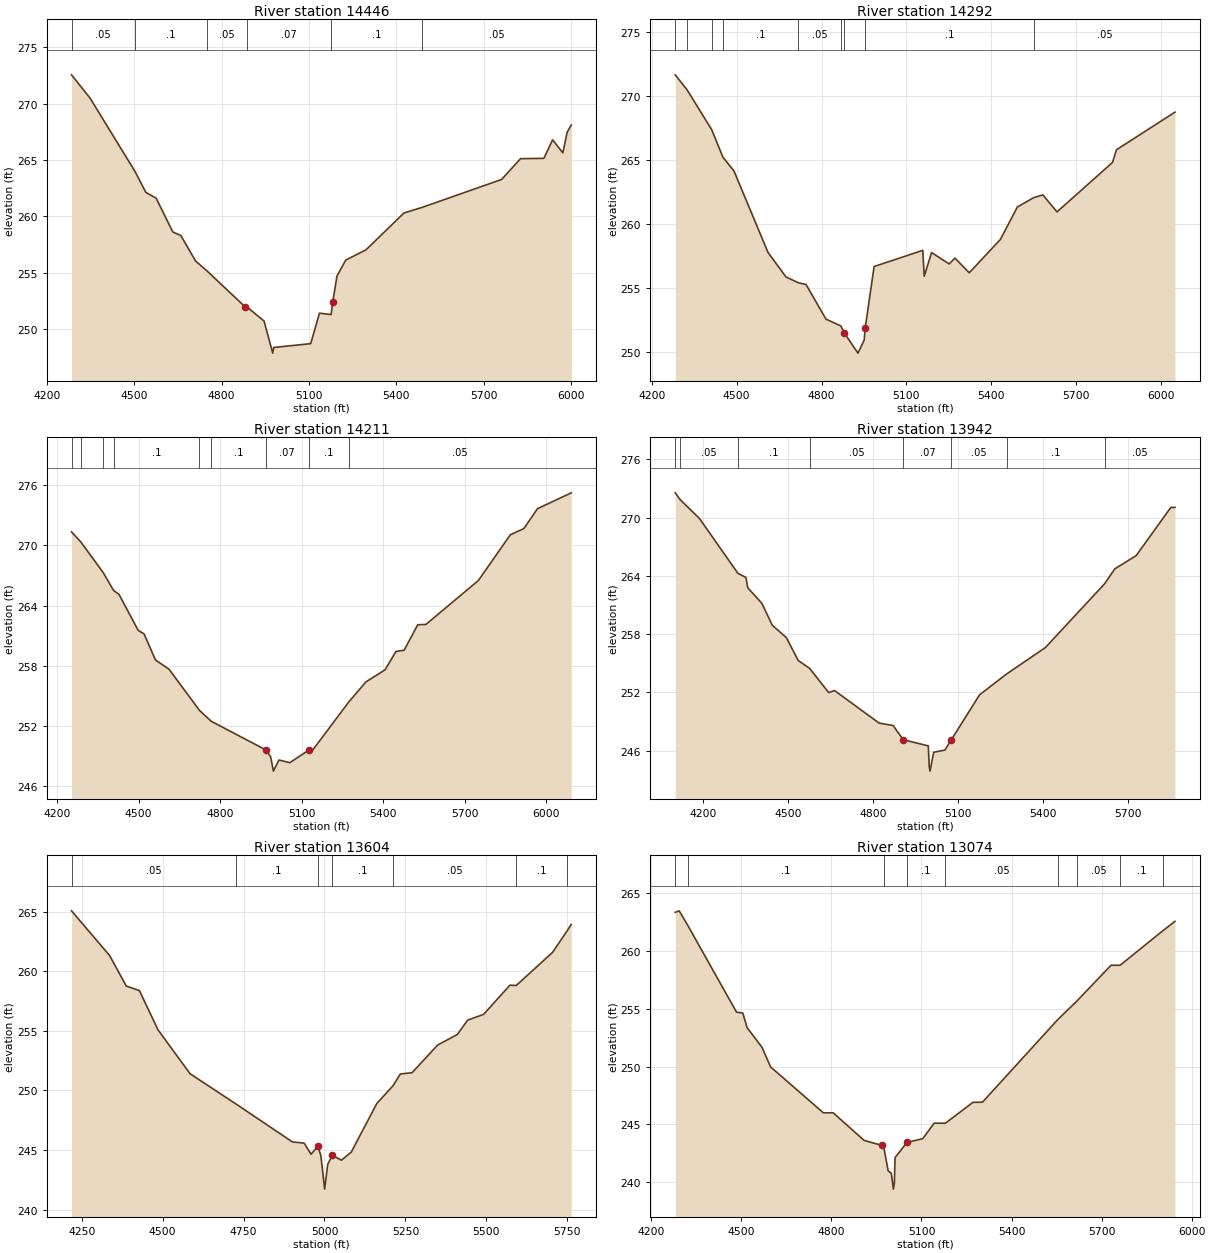
Type RM Length L Ch R = 1 ,14446   ,154,154,154
BEGIN DESCRIPTION:
Mapping XS 7765f1ad
END DESCRIPTION:
XS GIS Cut Line= 3
      2277197.87     13380737.81      2276802.02       13381217.
       2276854.1     13382310.71
#Sta/Elev= 30
  4284.8  272.55  4348.4  270.49  4501.9  264.03  4540.3  262.13  4575.5  261.62
  4632.8  258.62  4660.1  258.32    4711  256.05  4748.8  255.21  4880.3  252.01
  4888.1  251.97  4946.2  250.73    4976  247.89  4979.3  248.39  5106.4  248.73
  5136.5  251.43  5176.5  251.31 5182.05   252.4  5196.5  254.71  5226.6  256.13
  5296.6  257.05  5426.8  260.31  5488.8   260.8  5762.1  263.28  5827.2  265.12
  5907.3  265.15  5937.4  266.79  5972.4  265.64  5987.4  267.47  6001.3   268.1
#Mann= 6 ,-1 , 0
  4284.8     .05       0  4501.9      .1       0  4748.8     .05       0
  4888.1     .07       0  5176.5      .1       0  5488.8     .05       0
Bank Sta=4880.3,5182.05
XS Rating Curve= 0 ,0
Exp/Cntr=0.3,0.1

Type RM Length L Ch R = 1 ,14292   ,81,81,81
BEGIN DESCRIPTION:
UNT069 IN SUCR 22.0
END DESCRIPTION:
XS GIS Cut Line= 4
      2277145.76     13380722.22      2276663.98     13381253.36
      2276734.31     13381539.92      2276760.29     13382293.51
#Sta/Elev= 30
  4282.9  271.64  4324.1  270.49  4411.4  267.38  4451.6  265.21  4490.4  264.15
  4610.7   257.8  4674.2  255.89  4717.4  255.44  4745.1   255.3  4815.7   252.6
  4868.1  252.07  4879.6  251.55  4928.7  249.95  4950.6  250.96 4954.34  251.91
  4985.7   256.7  5157.7  257.96  5162.9  255.94  5188.9  257.79  5251.2   256.9
  5271.3  257.36    5322  256.21  5432.1  258.81  5492.1  261.34  5550.1  262.07
  5582.2  262.28  5632.2  260.96  5828.3  264.81  5842.3   265.8  6049.1  268.73
#Mann= 9 ,-1 , 0
  4282.9     .05       0  4324.1      .1       0  4411.4     .05       0
  4451.6      .1       0  4717.4     .05       0  4868.1      .1       0
  4879.6     .07       0 4954.34      .1       0  5550.1     .05       0
Bank Sta=4879.6,4954.34
XS Rating Curve= 0 ,0
Exp/Cntr=0.3,0.1

Type RM Length L Ch R = 1 ,14211   ,269,269,269
BEGIN DESCRIPTION:
Mapping XS 37786f8a
END DESCRIPTION:
XS GIS Cut Line= 3
      2277104.11     13380696.16      2276593.68     13381170.13
      2276520.77     13382310.75
#Sta/Elev= 30
  4253.2  271.35  4287.2  270.35  4369.1  267.32    4408  265.51  4427.9  265.12
  4498.7  261.53  4520.2  261.18  4562.2  258.58  4612.1  257.66  4724.1  253.56
  4767.5  252.47  4968.2  249.62  4986.6   248.9  4996.3   247.5  5016.6  248.61
  5056.7  248.34  5126.8   249.6  5136.9  249.45    5274   254.4  5337.3   256.4
  5407.4   257.6  5447.5  259.43  5477.6  259.55  5527.7  262.09  5557.7  262.12
  5750.9   266.5  5868.3  271.05  5918.4  271.68  5968.6  273.66  6092.7  275.24
#Mann= 9 ,-1 , 0
  4253.2     .05       0  4287.2      .1       0  4369.1     .05       0
    4408      .1       0  4724.1     .05       0  4767.5      .1       0
  4968.2     .07       0  5126.8      .1       0    5274     .05       0
Bank Sta=4968.2,5126.8
XS Rating Curve= 0 ,0
Exp/Cntr=0.3,0.1

Type RM Length L Ch R = 1 ,13942   ,338,338,338
BEGIN DESCRIPTION:
UNT069 IN SUCR 21.0
END DESCRIPTION:
XS GIS Cut Line= 3
      2277037.74     13380596.84      2276337.72     13381146.85
      2275987.71     13381946.89
#Sta/Elev= 30
  4100.8  272.56  4118.1  271.86  4186.7   269.9  4321.9  264.27  4350.3  263.84
  4356.6  262.78  4406.3  261.18  4443.3  258.92    4493  257.64  4534.7  255.29
  4575.1  254.47  4642.2  251.99    4663  252.19  4820.2  248.84  4869.7  248.59
  4905.2  247.13  4993.8  246.49    4997  244.39  4999.8  243.89  5012.9  245.83
  5052.3  246.06  5075.6  247.14  5174.7  251.75  5269.9  253.89    5407  256.62
  5615.7  263.18  5651.8  264.72  5727.4  266.09  5849.8  271.06  5864.3  271.06
#Mann= 8 ,-1 , 0
  4100.8      .1       0  4118.1     .05       0  4321.9      .1       0
  4575.1     .05       0  4905.2     .07       0  5075.6     .05       0
  5269.9      .1       0  5615.7     .05       0
Bank Sta=4905.2,5075.6
XS Rating Curve= 0 ,0
Exp/Cntr=0.3,0.1

Type RM Length L Ch R = 1 ,13604   ,530,530,530
BEGIN DESCRIPTION:
UNT069 IN SUCR 20.0
END DESCRIPTION:
XS GIS Cut Line= 4
      2276670.63     13380493.35      2276253.93     13380684.33
      2275915.39     13381213.85      2275837.57      13381663.5
#Sta/Elev= 30
  4218.8  265.06  4336.4  261.31  4387.9  258.75  4428.4  258.37    4486  255.07
    4585  251.39  4727.6  248.84    4901  245.67  4937.3  245.57  4958.5  244.64
  4979.6  245.29  4988.8  244.53  5000.5  241.71  5010.1   243.8  5024.4  244.54
  5052.4  244.14  5082.8  244.82  5161.5  248.89  5211.5  250.38  5234.2  251.37
  5270.6  251.48  5349.3   253.8  5410.2  254.68  5442.2  255.89  5491.4  256.37
  5572.6  258.82  5592.4   258.8  5704.5  261.58  5749.8   263.4    5762  263.92
#Mann= 7 ,-1 , 0
  4218.8     .05       0  4727.6      .1       0  4979.6     .05       0
  5024.4      .1       0  5211.5     .05       0  5592.4      .1       0
  5749.8     .05       0
Bank Sta=4979.6,5024.4
XS Rating Curve= 0 ,0
Exp/Cntr=0.3,0.1

Type RM Length L Ch R = 1 ,13074   ,549,549,549
BEGIN DESCRIPTION:
UNT069 IN SUCR 19.0
END DESCRIPTION:
XS GIS Cut Line= 4
      2276131.25     13380061.87      2275878.25     13380335.11
      2275564.56     13381347.01      2275564.56     13381579.73
#Sta/Elev= 30
  4279.9  263.32    4293  263.45  4321.9  262.18    4484   254.7    4505  254.62
  4519.2  253.36  4569.1  251.65  4597.4  249.97  4773.4     246    4806     246
    4909  243.62  4968.2  243.19  4974.2  243.07  4989.1  240.99  4999.6  240.78
  5006.5  239.41  5009.8  239.91    5012  242.13  5051.9  243.45  5104.3  243.77
  5142.4  245.11  5179.6   245.1  5271.8  246.91  5303.2  246.92  5553.8  254.05
  5617.1  255.64  5731.5  258.75  5761.8  258.75  5903.6  261.72  5944.4  262.54
#Mann= 9 ,-1 , 0
  4279.9     .05       0  4321.9      .1       0  4974.2     .07       0
  5051.9      .1       0  5179.6     .05       0  5553.8      .1       0
  5617.1     .05       0  5761.8      .1       0  5903.6     .05       0
Bank Sta=4968.2,5051.9
XS Rating Curve= 0 ,0
Exp/Cntr=0.3,0.1

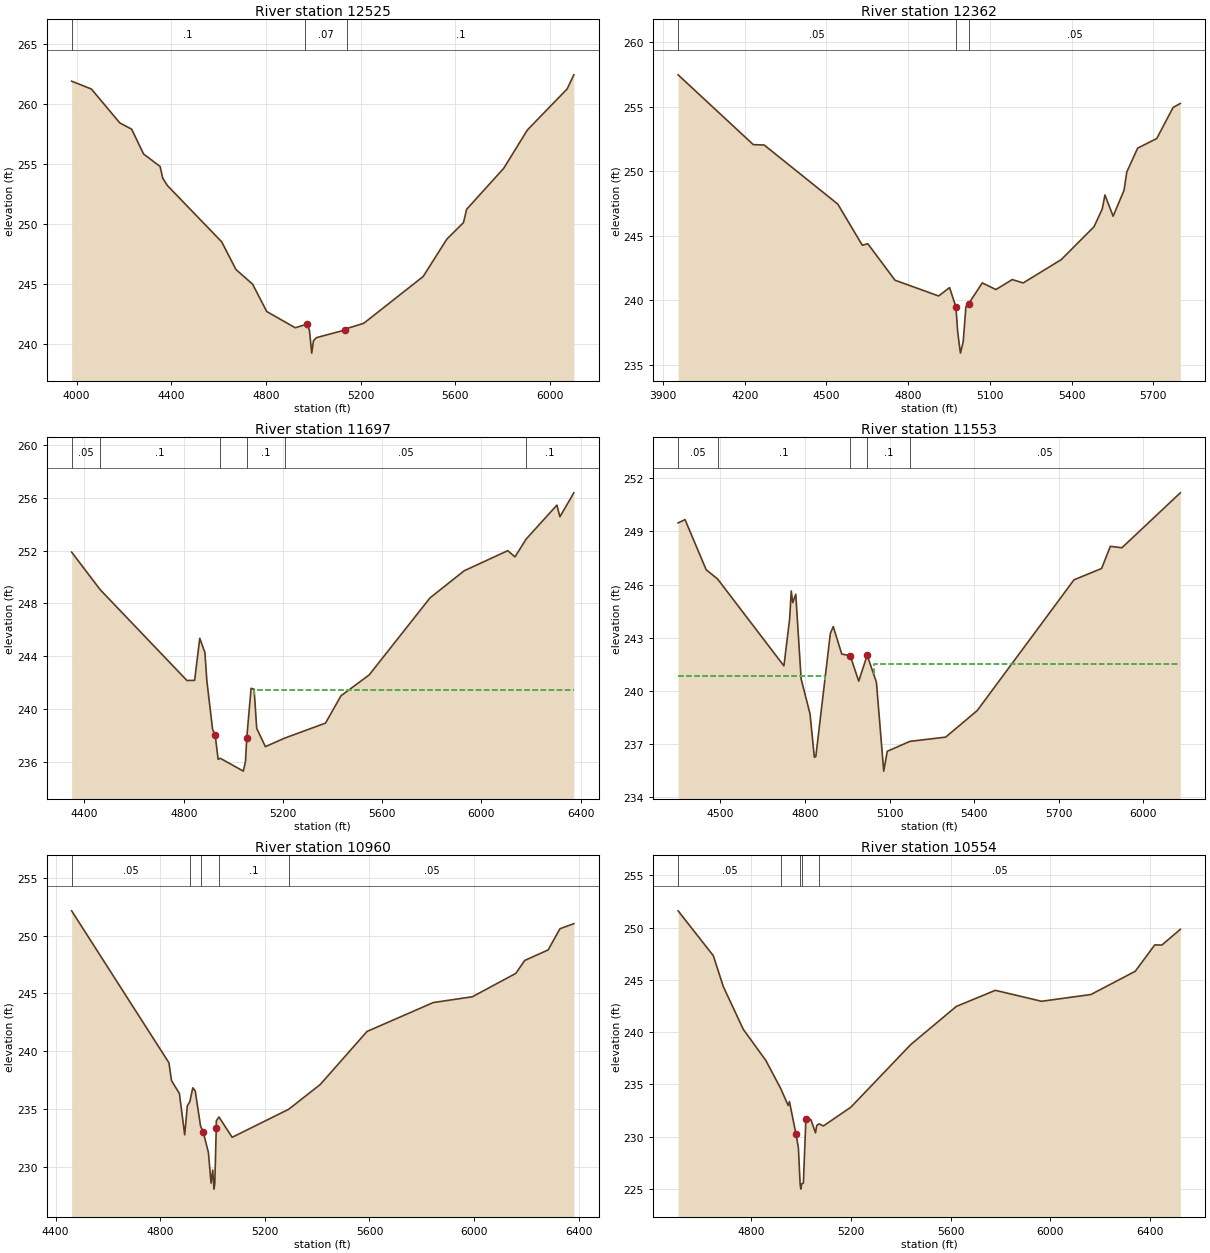
Type RM Length L Ch R = 1 ,12525   ,163,163,163
BEGIN DESCRIPTION:
UNT069 IN SUCR 18.0
END DESCRIPTION:
XS GIS Cut Line= 2
      2275440.46     13379283.53      2275341.53     13381402.62
#Sta/Elev= 30
  3978.8  261.87  4062.2  261.22  4182.3   258.4  4232.4  257.88  4282.5  255.82
  4352.5  254.78  4363.4  253.82  4382.6  253.21  4612.8  248.51  4672.9  246.21
    4743     245    4803  242.72  4923.2  241.37  4963.2  241.61  4973.2  241.65
  4983.2  241.17    4993  239.26  5000.4   240.3  5013.2  240.55  5133.4  241.18
  5143.4  241.32  5212.7  241.74  5463.7  245.63  5563.8  248.74  5633.9  250.11
  5647.4  251.22  5804.1  254.63  5904.2  257.82  6072.1  261.23  6100.2   262.4
#Mann= 3 ,-1 , 0
  3978.8      .1       0  4963.2     .07       0  5143.4      .1       0
Bank Sta=4973.2,5133.4
XS Rating Curve= 0 ,0
Exp/Cntr=0.3,0.1

Type RM Length L Ch R = 1 ,12362   ,665,665,665
BEGIN DESCRIPTION:
Mapping XS 463d672e
END DESCRIPTION:
XS GIS Cut Line= 2
      2275268.58     13379221.08      2275221.75     13381063.28
#Sta/Elev= 30
  3955.8  257.47  4231.7  252.06  4271.7  252.03  4541.8  247.45  4631.8  244.26
  4651.8  244.38  4751.8  241.55  4911.9  240.33  4951.9  240.98  4975.1  239.49
  4981.9  237.51  4991.7   235.9  5001.9  236.78  5011.9  239.51  5021.9  239.73
  5071.9  241.34    5122  240.83    5182   241.6    5222  241.34  5361.9  243.15
  5482.1   245.7  5512.1  247.07  5522.1  248.16  5552.1  246.51  5592.1  248.52
  5602.1  249.93  5642.1  251.79  5712.1  252.53  5772.2  254.94  5798.6  255.25
#Mann= 3 , 0 , 0
  3955.8     .05       0  4975.1     .04       0  5021.9     .05       0
Bank Sta=4975.1,5021.9
XS Rating Curve= 0 ,0
Exp/Cntr=0.3,0.1

Type RM Length L Ch R = 1 ,11697   ,144,144,144
BEGIN DESCRIPTION:
Mapping XS 6d7eff
END DESCRIPTION:
XS GIS Cut Line= 3
      2275013.36     13379137.75      2274680.04     13380392.92
      2274966.51     13381059.61
#Sta/Elev= 30
  4348.3  251.88  4462.9  249.05    4813  242.18    4844  242.19  4864.7  245.37
  4885.4   244.3  4893.4  242.14  4916.4  238.49  4926.8  238.06  4938.8  236.22
  4947.5   236.3  5040.3  235.33  5048.9  236.04  5054.1  237.82  5071.6  241.59
 5083.81  241.51  5094.3  238.56  5129.3  237.18  5206.4  237.82  5371.7  238.96
  5433.8  241.02  5547.6   242.6  5792.8  248.42  5930.6  250.47  6106.3  251.99
  6135.3  251.52  6180.5  252.87  6304.3  255.43  6316.5  254.55  6372.6  256.36
#Mann= 6 ,-1 , 0
  4348.3     .05       0  4462.9      .1       0  4947.5     .07       0
  5054.1      .1       0  5206.4     .05       0  6180.5      .1       0
#XS Ineff= 2 , 0
                         5085.23          241.45
Permanent Ineff=
       F       F
Bank Sta=4926.8,5054.1
XS Rating Curve= 0 ,0
Exp/Cntr=0.3,0.1

Type RM Length L Ch R = 1 ,11553   ,593,593,593
BEGIN DESCRIPTION:
Mapping XS 6d7eff18
END DESCRIPTION:
XS GIS Cut Line= 6
      2274882.01      13379092.7      2274749.21     13379483.29
      2274715.36     13379623.92      2274710.15     13379767.15
      2274572.13     13380337.46      2274737.05     13380801.85
#Sta/Elev= 30
  4350.5  249.48    4375  249.67  4449.9  246.84  4490.8  246.31  4725.5  241.41
  4745.7  244.04  4751.6  245.64  4756.8  244.98  4767.5  245.46  4786.5  240.68
  4818.1   238.7  4833.5  236.25  4838.7   236.3  4890.1  243.24  4900.4  243.63
  4930.6  242.08  4960.7  241.98  4990.7  240.55  5020.7  242.01  5053.4  240.49
  5079.3  235.47  5091.9  236.59  5172.1  237.15    5299  237.39  5410.8  238.89
  5753.8  246.27  5851.7  246.91  5882.6  248.16  5923.7  248.08  6130.6  251.18
#Mann= 5 ,-1 , 0
  4350.5     .05       0  4490.8      .1       0  4960.7     .07       0
  5020.7      .1       0  5172.1     .05       0
#XS Ineff= 2 , 0
         4870.74  240.83 5044.03           241.5
Permanent Ineff=
       F       F
Bank Sta=4960.7,5020.7
XS Rating Curve= 0 ,0
Exp/Cntr=0.3,0.1

Type RM Length L Ch R = 1 ,10960   ,406,406,406
BEGIN DESCRIPTION:
UNT069 IN SUCR 17.0
END DESCRIPTION:
XS GIS Cut Line= 3
       2274096.7     13379017.88       2274216.5     13379991.88
      2274627.97     13380835.66
#Sta/Elev= 30
  4461.3  252.14  4833.1  239.01  4843.2  237.46  4873.4  236.34  4893.5  232.78
  4903.6  235.29  4913.3  235.65  4924.5  236.84  4933.8  236.57    4954  233.55
    4964  233.04  4984.2  231.25  4994.3   228.6  5000.7  229.73  5005.5  228.08
  5008.7  228.58  5014.2  233.37  5014.4  233.98  5024.5  234.32  5074.9  232.56
  5291.6  234.99    5412  237.13  5590.5  241.71  5843.9  244.21  5993.3  244.71
  6159.4  246.73  6193.6  247.85  6283.2  248.76  6328.2  250.59  6381.4  251.03
#Mann= 5 ,-1 , 0
  4461.3     .05       0  4913.3      .1       0    4954     .07       0
  5024.5      .1       0  5291.6     .05       0
Bank Sta=4964,5014.2
XS Rating Curve= 0 ,0
Exp/Cntr=0.3,0.1

Type RM Length L Ch R = 1 ,10554   ,424,424,424
BEGIN DESCRIPTION:
UNT069 IN SUCR 16.0
END DESCRIPTION:
XS GIS Cut Line= 3
      2273721.71     13379096.03      2273815.46     13380111.67
      2274440.47     13380887.72
#Sta/Elev= 30
  4505.7   251.6  4647.1  247.31  4687.3  244.35  4767.6  240.26    4858  237.29
  4917.6  234.61  4947.6  232.99  4952.7  233.36  4978.5   230.3  4988.6  228.97
  4995.6  225.49  4998.4  224.99  5001.6  225.49  5008.7  225.57  5018.7  231.69
  5038.8  231.64  5057.3  230.37  5062.3  231.08  5072.1  231.23    5089  231.03
  5199.5  232.83  5440.5  238.83  5622.8  242.46  5779.5     244  5965.1  242.95
  6163.4   243.6  6341.2  245.82  6419.4  248.34  6448.2  248.33  6522.1  249.83
#Mann= 5 ,-1 , 0
  4505.7     .05       0  4917.6      .1       0  4995.6     .07       0
  5001.6      .1       0  5072.1     .05       0
Bank Sta=4978.5,5018.7
XS Rating Curve= 0 ,0
Exp/Cntr=0.3,0.1