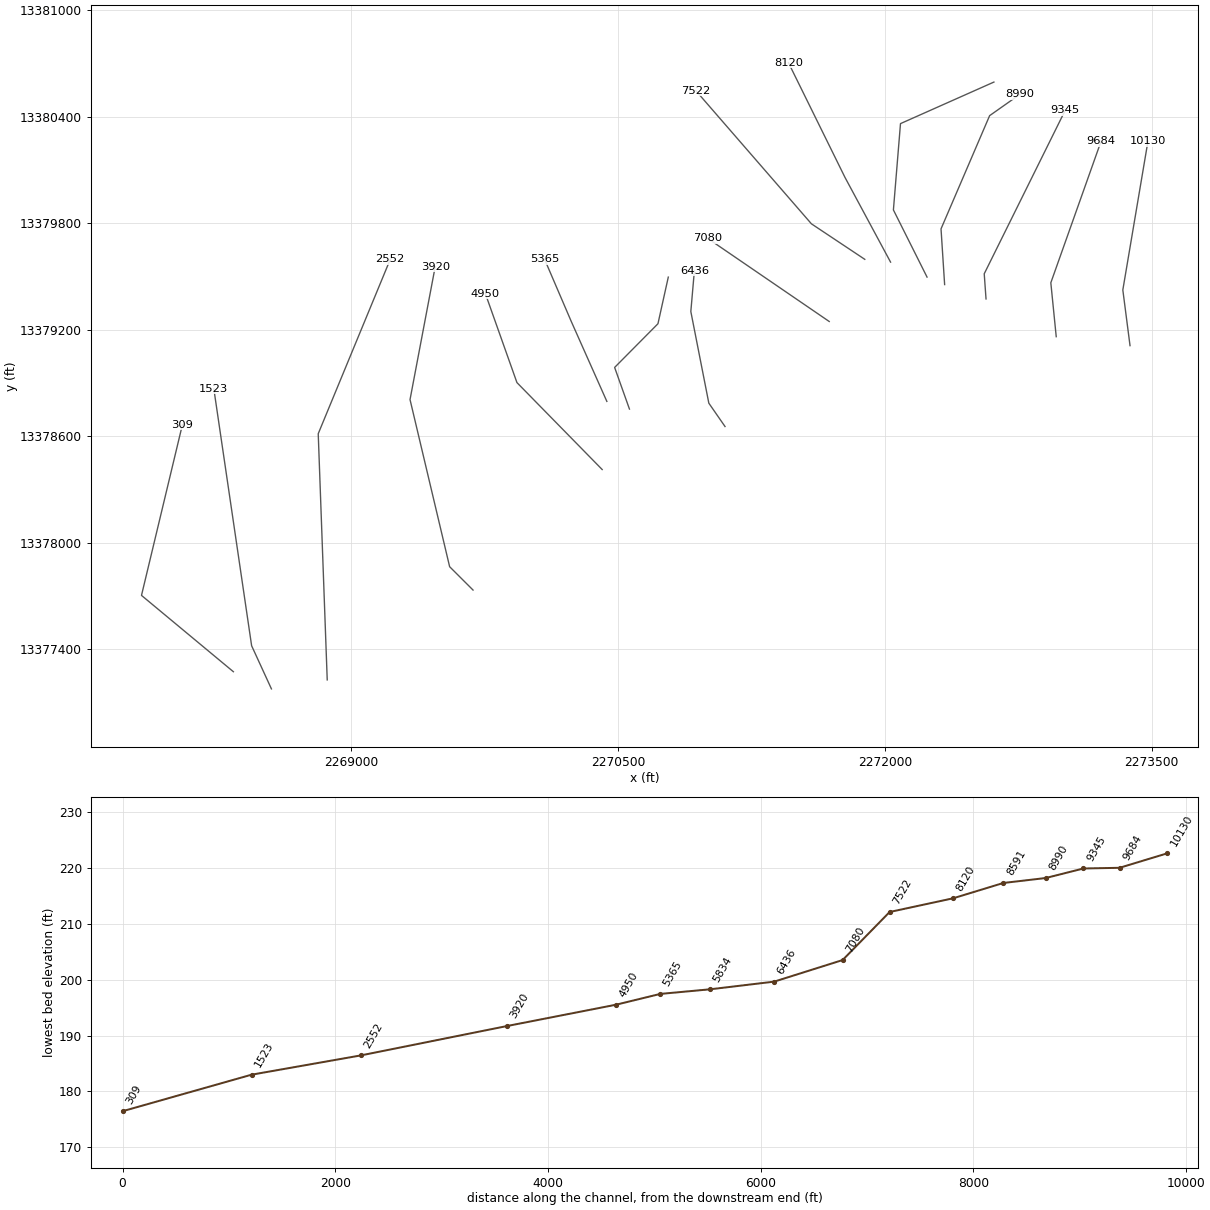
HEC-RAS study UNT069 IN SUCR.prj: UNT069 IN SUCR Base Level Engineering

--- UNT069 IN SUCR.g01 (geometry) --- (continued)

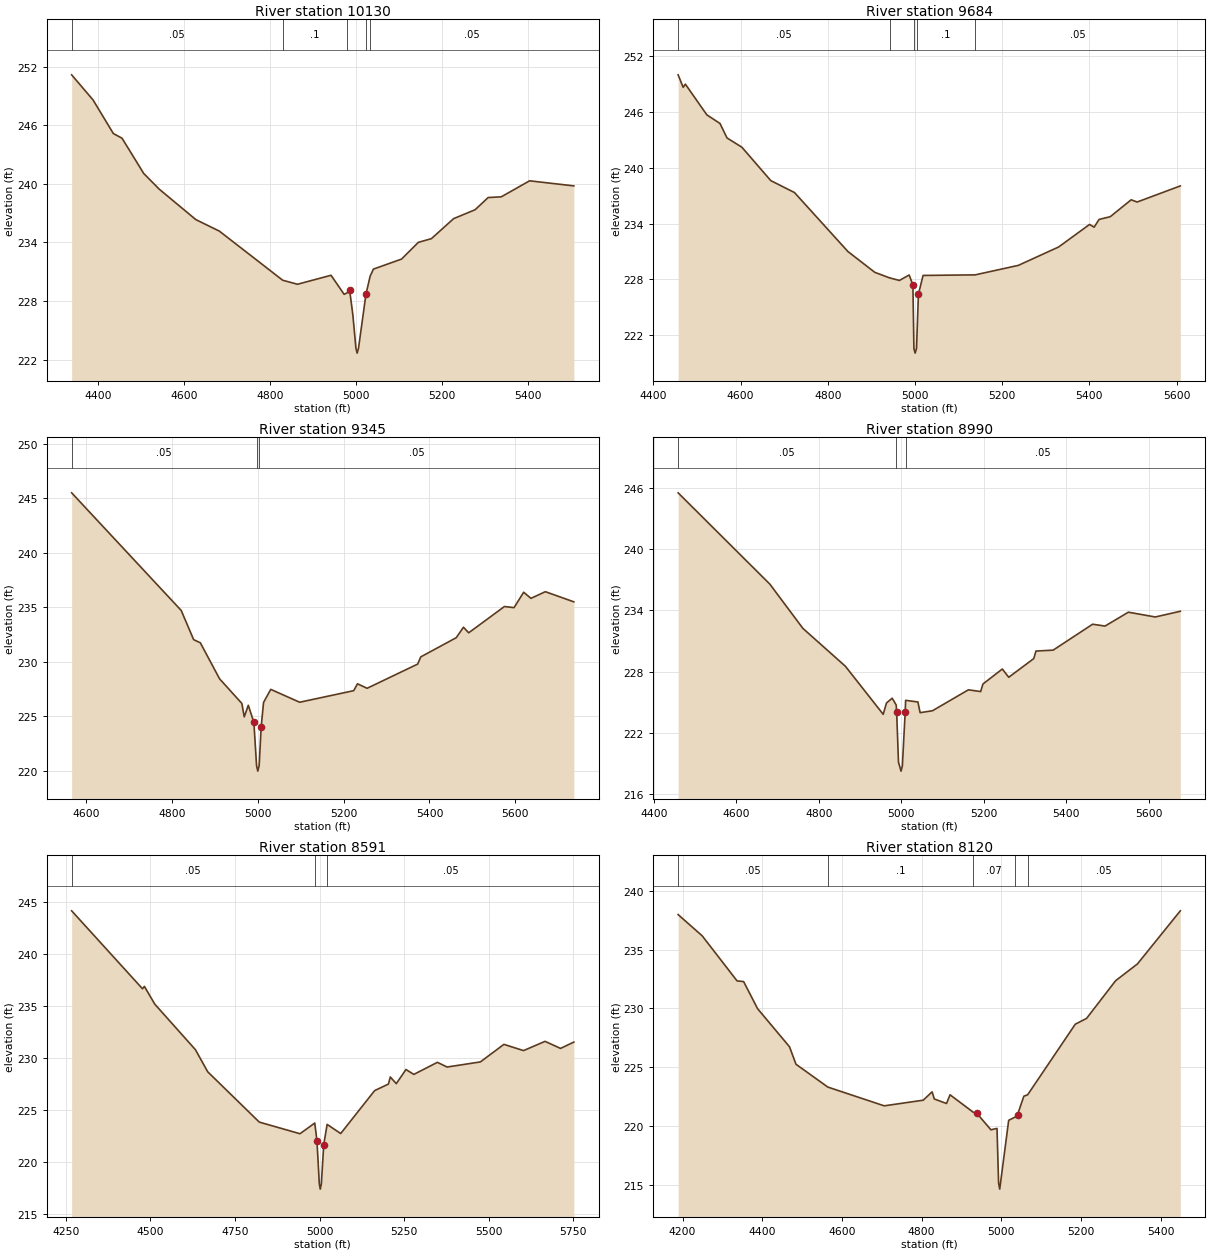
Type RM Length L Ch R = 1 ,10130   ,446,446,446
BEGIN DESCRIPTION:
UNT069 IN SUCR 15.0
END DESCRIPTION:
XS GIS Cut Line= 3
      2273378.84     13379110.75      2273338.37     13379424.39
      2273479.84      13380263.1
#Sta/Elev= 30
  4339.4  251.15  4389.1  248.58  4436.3  245.14  4456.5  244.66  4506.9  241.05
  4542.8  239.45  4627.9  236.33  4682.6  235.15  4829.8  230.12  4864.1  229.71
  4942.1  230.63  4972.5  228.68    4980  228.85  4985.1  229.17  4992.8  226.56
  4999.9  223.16  5002.7  222.66  5005.9  223.16  5023.2  228.69  5032.9  230.53
  5040.5  231.26    5106  232.29  5144.9     234  5175.3  234.38    5227  236.43
  5276.8  237.34  5307.2  238.59  5337.6  238.66  5403.4   240.3  5506.2  239.78
#Mann= 5 ,-1 , 0
  4339.4     .05       0  4829.8      .1       0    4980     .07       0
  5023.2      .1       0  5032.9     .05       0
Bank Sta=4985.1,5023.2
XS Rating Curve= 0 ,0
Exp/Cntr=0.3,0.1

Type RM Length L Ch R = 1 ,9684    ,339,339,339
BEGIN DESCRIPTION:
UNT069 IN SUCR 14.0
END DESCRIPTION:
XS GIS Cut Line= 3
      2272963.97     13379161.27      2272933.61     13379464.87
      2273216.53      13380263.1
#Sta/Elev= 30
  4456.5  249.99  4468.1  248.65  4473.1  248.99  4522.4  245.69  4552.6  244.76
  4568.6  243.21  4602.8  242.21  4669.1  238.62  4723.4  237.34    4846     231
  4907.8  228.76  4941.5  228.17  4964.2  227.89  4986.5  228.48  4995.1  227.41
  4997.4  220.58  5000.2  220.08  5003.4  220.58  5007.7   226.4  5018.4  228.43
  5137.8  228.49  5236.9  229.51  5329.5  231.49  5400.3  233.91  5410.9  233.62
  5422.2  234.45  5447.7  234.74  5495.8  236.56  5509.5  236.32  5608.5  238.05
#Mann= 5 ,-1 , 0
  4456.5     .05       0  4941.5      .1       0  4997.4     .07       0
  5003.4      .1       0  5137.8     .05       0
Bank Sta=4995.1,5007.7
XS Rating Curve= 0 ,0
Exp/Cntr=0.3,0.1

Type RM Length L Ch R = 1 ,9345    ,355,355,355
BEGIN DESCRIPTION:
UNT069 IN SUCR 13.0
END DESCRIPTION:
XS GIS Cut Line= 3
      2272569.32     13379373.83       2272559.2     13379515.46
      2273014.58     13380436.32
#Sta/Elev= 30
  4566.8  245.49  4821.9   234.7  4850.9  232.02  4866.5  231.73  4911.2  228.43
  4963.1  226.17  4968.7  224.94  4978.1     226  4991.1  224.44  4997.4  220.46
  5000.2  219.96  5003.4  220.46    5008  223.97  5013.6  226.26  5030.4  227.46
  5097.7  226.28  5223.5  227.34  5232.4  227.97  5254.8  227.56  5372.5  229.78
  5379.7  230.44  5462.3   232.2  5479.1  233.16  5491.3  232.65  5574.5  235.06
  5596.9  234.96  5619.3  236.37  5636.2  235.81  5669.8  236.42  5736.1  235.49
#Mann= 3 ,-1 , 0
  4566.8     .05       0  4997.4    .035       0  5003.4     .05       0
Bank Sta=4991.1,5008
XS Rating Curve= 0 ,0
Exp/Cntr=0.3,0.1

Type RM Length L Ch R = 1 ,8990    ,399,399,399
BEGIN DESCRIPTION:
UNT069 IN SUCR 12.0
END DESCRIPTION:
XS GIS Cut Line= 4
      2272336.59     13379454.72      2272316.35     13379768.44
      2272589.56     13380405.94      2272761.58     13380527.36
#Sta/Elev= 30
  4458.4  245.53    4681  236.58  4761.2  232.24  4864.3  228.53    4956  223.82
    4964  224.93  4977.8   225.4  4987.6  224.73 4988.64  224.07  4993.1  219.13
  4999.3  218.25  5002.5  218.75 5009.32  224.02  5010.4  225.19  5040.2  225.03
  5045.6  223.98  5075.7  224.17  5162.7  226.22  5192.5  226.05    5198  226.79
  5245.1  228.26  5260.6  227.45  5321.3  229.28  5326.7  230.02  5368.4  230.11
  5464.1  232.65  5494.3  232.47  5550.9  233.83  5616.2  233.36  5676.9  233.92
#Mann= 3 ,-1 , 0
  4458.4     .05       0  4987.6    .035       0  5010.4     .05       0
Bank Sta=4988.64,5009.32
XS Rating Curve= 0 ,0
Exp/Cntr=0.3,0.1

Type RM Length L Ch R = 1 ,8591    ,471,471,471
BEGIN DESCRIPTION:
UNT069 IN SUCR 11.0
END DESCRIPTION:
XS GIS Cut Line= 4
       2272237.7     13379496.89      2272048.63     13379875.03
      2272088.48      13380361.1      2272613.64     13380595.08
#Sta/Elev= 30
  4266.8  244.14  4476.4  236.64    4482  236.87  4512.7  235.16  4632.9  230.78
  4669.3  228.65  4821.8  223.81  4942.2  222.69  4985.9  223.72  4992.4  222.02
  4999.4  217.86  5002.2  217.36  5005.4  217.86  5012.5  221.65  5022.5  223.59
  5062.6  222.71    5163  226.84  5203.8  227.47  5209.3  228.15    5227  227.51
  5255.7  228.87  5278.9   228.4  5348.6  229.56  5377.3  229.11  5475.7   229.6
  5545.4  231.29  5603.4  230.69  5667.1  231.58  5712.9   230.9  5752.2  231.51
#Mann= 3 ,-1 , 0
  4266.8     .05       0  4985.9    .035       0  5022.5     .05       0
Bank Sta=4992.4,5012.5
XS Rating Curve= 0 ,0
Exp/Cntr=0.3,0.1

Type RM Length L Ch R = 1 ,8120    ,598,598,598
BEGIN DESCRIPTION:
UNT069 IN SUCR 10.0
END DESCRIPTION:
XS GIS Cut Line= 3
      2272032.71     13379581.14      2271775.98     13380059.02
      2271458.98     13380703.39
#Sta/Elev= 30
  4188.8  237.99  4249.3  236.18  4336.9  232.34  4353.2  232.29  4388.3  229.98
  4468.4  226.74  4484.7  225.25  4564.5  223.31  4706.1  221.71    4804  222.19
  4826.4   222.9    4832  222.29  4862.6  221.91  4871.4  222.65  4929.5  221.17
  4938.8  221.07    4974  219.67  4989.3  219.79  4993.3  215.12  4996.1  214.62
  5018.6  220.48  5034.2  220.74  5040.9  220.97  5056.7  222.53  5066.2  222.65
  5185.8  228.66    5214  229.15    5287  232.36  5341.8  233.79  5449.4  238.31
#Mann= 5 ,-1 , 0
  4188.8     .05       0  4564.5      .1       0  4929.5     .07       0
  5034.2      .1       0  5066.2     .05       0
Bank Sta=4938.8,5040.9
XS Rating Curve= 0 ,0
Exp/Cntr=0.3,0.1

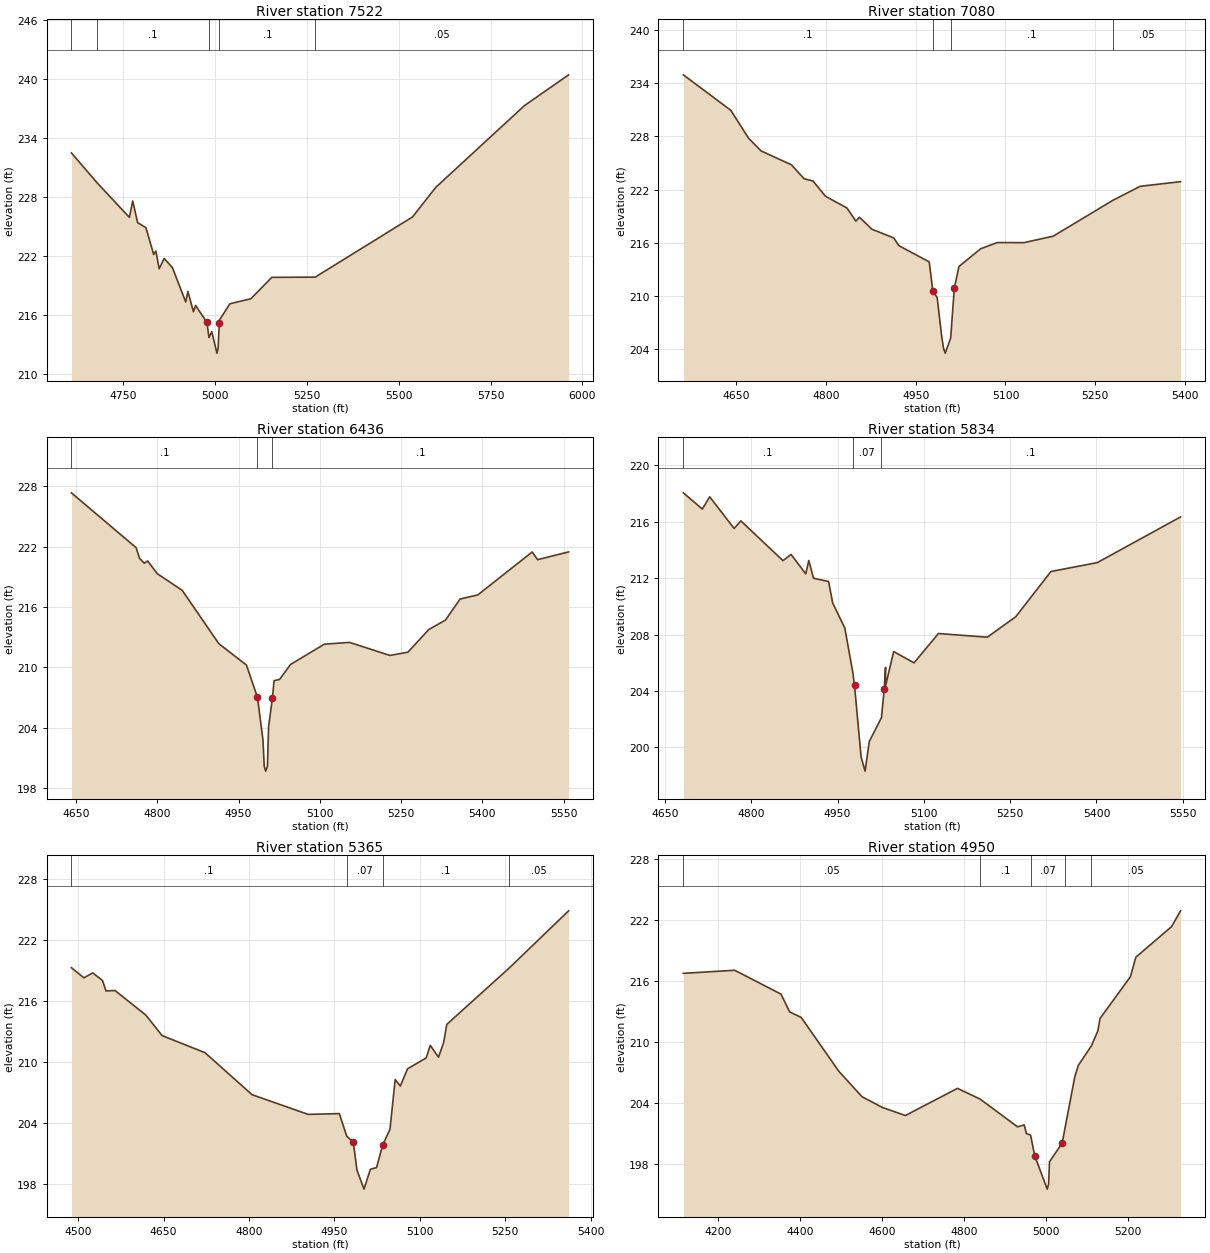
Type RM Length L Ch R = 1 ,7522    ,442,442,442
BEGIN DESCRIPTION:
UNT069 IN SUCR 9.0
END DESCRIPTION:
XS GIS Cut Line= 3
      2271887.74     13379596.84      2271587.72     13379796.85
      2270937.75     13380546.82
#Sta/Elev= 30
  4609.3  232.53  4680.1  229.45  4767.1  225.97  4776.1  227.64  4789.6  225.43
  4812.1  224.92  4833.2   222.2  4839.2  222.54  4848.2  220.74  4861.7  221.79
  4884.2  220.86  4920.3  217.37  4926.3  218.44  4941.3  216.37  4947.3     217
 4978.18  215.28  4983.6  213.74  4991.3  214.34  5005.3  212.16  5008.5  212.66
 5011.72  215.25  5012.1  215.52  5040.6  217.18  5097.6  217.69  5154.6  219.87
  5272.6  219.89  5537.4  226.01    5601  229.03  5842.2  237.34  5962.3  240.47
#Mann= 5 ,-1 , 0
  4609.3     .05       0  4680.1      .1       0  4983.6     .07       0
  5012.1      .1       0  5272.6     .05       0
Bank Sta=4978.18,5011.72
XS Rating Curve= 0 ,0
Exp/Cntr=0.3,0.1

Type RM Length L Ch R = 1 ,7080    ,644,644,644
BEGIN DESCRIPTION:
UNT069 IN SUCR 8.0
END DESCRIPTION:
XS GIS Cut Line= 2
      2271687.76     13379246.83      2271002.14     13379716.57
#Sta/Elev= 30
  4561.6  234.96  4640.9  230.96  4670.7   227.8  4691.6  226.37  4742.4   224.8
  4763.4  223.23  4778.3  222.98  4799.3  221.25  4835.1  219.93    4850  218.45
  4856.1  218.88  4877.1  217.52  4913.2  216.56  4921.8  215.68  4972.6  213.85
  4978.6  210.59  4985.9  209.81  4993.5  205.42  4996.6  204.05  4999.4  203.55
  5008.5  205.26  5014.5  210.85  5022.3  213.33  5058.6  215.33  5086.3  216.03
    5131  216.02  5179.9  216.75  5279.9  220.81  5325.3  222.38  5392.7   222.9
#Mann= 4 ,-1 , 0
  4561.6      .1       0  4978.6     .07       0  5008.5      .1       0
  5279.9     .05       0
Bank Sta=4978.6,5014.5
XS Rating Curve= 0 ,0
Exp/Cntr=0.3,0.1

Type RM Length L Ch R = 1 ,6436    ,602,602,602
BEGIN DESCRIPTION:
UNT069 IN SUCR 7.0
END DESCRIPTION:
XS GIS Cut Line= 4
      2271102.07     13378655.34      2271010.99     13378786.89
       2270909.8     13379302.96      2270929.87     13379533.79
#Sta/Elev= 30
  4641.6  227.35  4761.2  221.89  4767.3  220.84  4776.1  220.35  4782.2  220.58
  4800.1  219.31    4846  217.66  4913.7  212.35  4964.6  210.23    4985  207.02
  4995.2  202.75  4997.4  200.18  5000.1  199.68  5003.4  200.18  5005.5   204.1
  5012.5  206.91  5015.6  208.67  5025.8   208.8  5046.1  210.29  5108.4   212.3
  5154.8  212.48  5229.6  211.18  5262.8  211.51  5300.9  213.75    5332   214.7
  5358.9  216.79  5391.6   217.2    5492  221.47    5502   220.7  5559.2  221.48
#Mann= 3 ,-1 , 0
  4641.6      .1       0    4985     .07       0  5012.5      .1       0
Bank Sta=4985,5012.5
XS Rating Curve= 0 ,0
Exp/Cntr=0.3,0.1

Type RM Length L Ch R = 1 ,5834    ,469,469,469
BEGIN DESCRIPTION:
UNT069 IN SUCR 6.0
END DESCRIPTION:
XS GIS Cut Line= 4
      2270564.78     13378753.68      2270481.43      13378988.1
      2270724.99     13379234.12      2270783.13     13379496.78
#Sta/Elev= 30
  4682.1  218.05  4715.1   216.9  4727.9  217.77  4770.4  215.52    4782  216.06
  4855.3  213.24  4869.3  213.68  4894.8   212.3  4900.1  213.25  4908.3  211.99
  4934.5  211.76  4941.6  210.24  4962.7  208.46  4976.9  205.24 4979.55  204.39
    4991  199.32  4997.9  198.31  5005.2  200.41  5026.4  202.11 5031.25  204.14
  5033.5  205.67 5033.52  204.36  5047.6  206.79    5083  205.99  5125.4  208.07
  5210.3  207.81  5259.7  209.26  5320.9  212.47  5401.5   213.1  5546.1  216.34
#Mann= 3 ,-1 , 0
  4682.1      .1       0  4976.9     .07       0  5026.4      .1       0
Bank Sta=4979.55,5031.25
XS Rating Curve= 0 ,0
Exp/Cntr=0.3,0.1

Type RM Length L Ch R = 1 ,5365    ,415,415,415
BEGIN DESCRIPTION:
UNT069 IN SUCR 5.0
END DESCRIPTION:
XS GIS Cut Line= 3
      2270437.71     13378796.88      2270237.72     13379246.85
      2270087.72     13379596.85
#Sta/Elev= 30
  4488.1  219.29    4510  218.29  4525.7  218.78  4542.8  218.02  4548.9     217
  4564.7  217.04  4618.7  214.63  4647.4   212.6  4722.7  210.92  4805.4  206.78
  4903.9  204.84  4958.6  204.92  4971.6   202.7  4983.2   202.1  4989.6  199.35
    5002  197.48  5013.2  199.44    5024   199.6  5034.9  201.85  5047.6  203.38
  5056.7  208.28  5065.7  207.63  5078.4  209.33  5111.1   210.4  5118.3  211.64
  5132.8  210.47  5141.9  211.94  5147.3   213.7  5256.6  219.24  5361.3  224.89
#Mann= 4 ,-1 , 0
  4488.1      .1       0  4971.6     .07       0  5034.9      .1       0
  5256.6     .05       0
Bank Sta=4983.2,5034.9
XS Rating Curve= 0 ,0
Exp/Cntr=0.3,0.1

Type RM Length L Ch R = 1 ,4950    ,1030,1030,1030
BEGIN DESCRIPTION:
Mapping XS a1a1812d
END DESCRIPTION:
XS GIS Cut Line= 3
      2270411.41     13378413.16      2269932.23     13378902.77
      2269755.31     13379402.28
#Sta/Elev= 30
  4114.5  216.75    4240  217.05  4353.1  214.71  4374.3  212.96  4402.5  212.42
  4494.6  207.12  4551.1  204.63  4600.6  203.58  4657.1  202.78  4784.4  205.45
  4839.6   204.4  4931.2  201.67  4947.5  201.86  4952.8  201.01    4963  200.86
  4973.1  198.84  5003.7  195.55    5007  196.05  5009.3  198.24  5040.2  200.07
  5047.9   201.7  5071.1  206.59  5079.7  207.71  5111.4  209.61  5127.5   211.1
  5132.8  212.32    5207  216.42  5220.2  218.33  5307.6  221.34  5329.5  222.89
#Mann= 5 ,-1 , 0
  4114.5     .05       0  4839.6      .1       0    4963     .07       0
  5047.9      .1       0  5111.4     .05       0
Bank Sta=4973.1,5040.2
XS Rating Curve= 0 ,0
Exp/Cntr=0.3,0.1

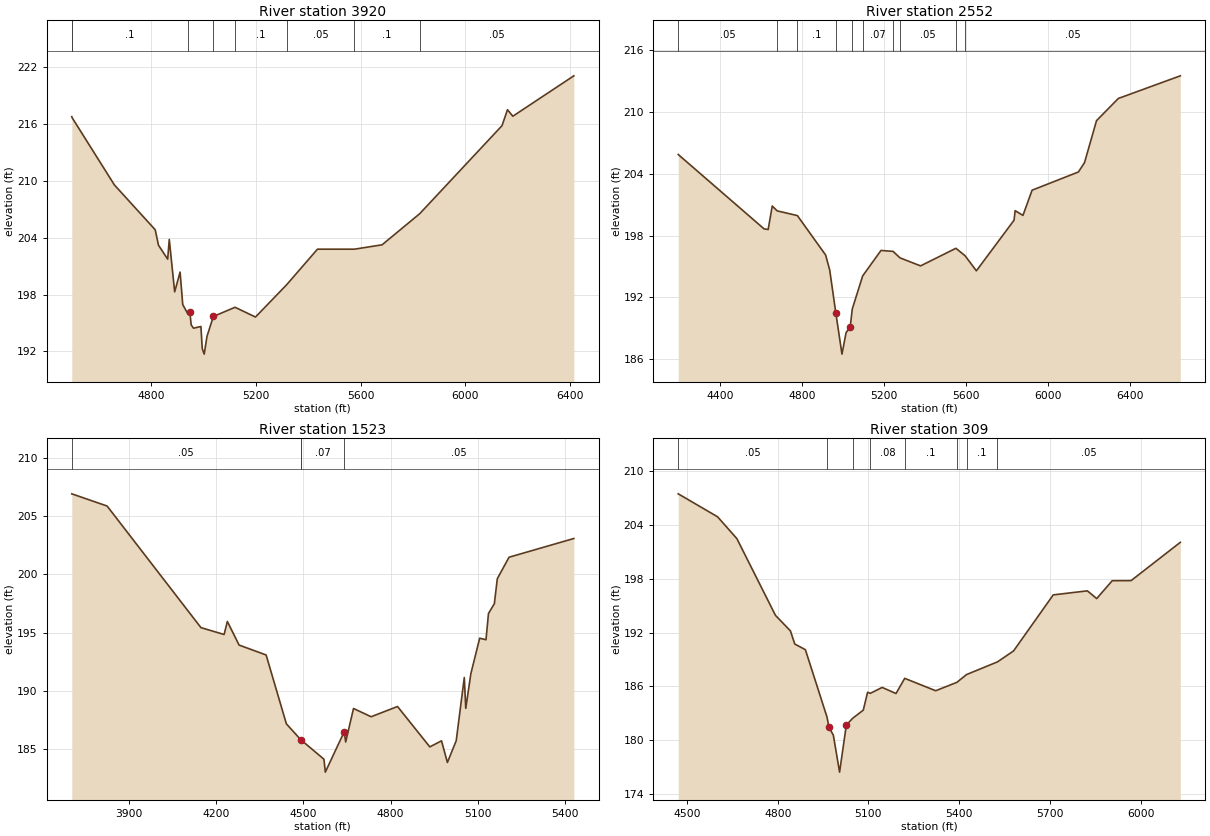
Type RM Length L Ch R = 1 ,3920    ,1368,1368,1368
BEGIN DESCRIPTION:
UNT069 IN SUCR 4.0
END DESCRIPTION:
XS GIS Cut Line= 4
      2269685.38     13377734.53      2269553.85     13377866.06
      2269331.23     13378807.13      2269472.81     13379555.49
#Sta/Elev= 30
  4498.5   216.8  4500.2  216.68  4661.1  209.59  4816.8  204.85  4829.2  203.22
  4864.2  201.75  4870.3  203.83  4890.9  198.29  4911.6  200.38  4921.7  196.95
  4942.2  195.91  4948.7  196.18  4953.9   194.8  4962.8  194.45    4991  194.63
  4996.1  192.29  5003.6  191.71  5014.2  193.59  5038.4  195.69  5121.2  196.66
  5199.1  195.63  5317.6  199.03  5435.5   202.8  5576.2   202.8  5681.8  203.26
  5825.4  206.55  6139.2  215.85  6160.2  217.54  6180.5  216.85  6413.2  221.12
#Mann= 8 ,-1 , 0
  4498.5     .08       0  4500.2      .1       0  4942.2     .03       0
  5038.4     .05       0  5121.2      .1       0  5317.6     .05       0
  5576.2      .1       0  5825.4     .05       0
Bank Sta=4948.7,5038.4
XS Rating Curve= 0 ,0
Exp/Cntr=0.3,0.1

Type RM Length L Ch R = 1 ,2552    ,1029,1029,1029
BEGIN DESCRIPTION:
UNT069 IN SUCR 3.0
END DESCRIPTION:
XS GIS Cut Line= 3
      2268865.75     13377228.57      2268815.16     13378614.87
       2269219.9     13379596.37
#Sta/Elev= 30
  4197.4  205.88    4616  198.65    4636  198.59    4656  200.87  4679.9   200.4
  4778.6  199.94  4916.2  196.11  4936.2  194.65  4966.2  190.46    4996  186.47
  5016.2  188.56  5036.2  189.11  5046.2  190.85  5096.9  194.07  5186.3  196.55
  5245.3  196.46  5279.1  195.83  5379.4  195.05  5551.7  196.76  5596.4  196.04
  5651.6  194.57  5835.3  199.49  5840.8  200.42  5878.8  199.96  5923.4  202.41
  6149.2  204.18  6178.9  205.08  6237.6  209.17  6344.1  211.33  6646.3  213.53
#Mann= 10 ,-1 , 0
  4197.4     .05       0  4679.9     .08       0  4778.6      .1       0
  4966.2     .07       0  5046.2      .1       0  5096.9     .07       0
  5245.3      .1       0  5279.1     .05       0  5551.7      .1       0
  5596.4     .05       0
Bank Sta=4966.2,5036.2
XS Rating Curve= 0 ,0
Exp/Cntr=0.3,0.1

Type RM Length L Ch R = 1 ,1523    ,1214,1214,1214
BEGIN DESCRIPTION:
UNT069 IN SUCR 2.0
END DESCRIPTION:
XS GIS Cut Line= 3
      2268552.04       13377178.      2268440.75     13377420.82
      2268228.26      13378867.8
#Sta/Elev= 30
  3701.9  206.93  3823.7  205.88  4146.9  195.43  4226.7  194.84  4237.9  195.96
  4278.3  193.93  4371.4  193.08  4441.2  187.16  4490.6   185.8  4570.6  184.12
  4575.4  183.01  4640.4  186.48  4645.5   185.6  4672.5  188.48  4733.1  187.77
  4824.1  188.65  4935.3  185.18  4975.7   185.7  4995.9  183.84  5026.3  185.71
  5054.1  191.14  5059.2  188.49  5076.8  191.48  5107.1  194.52  5128.9  194.39
  5137.4  196.64  5157.7  197.49  5167.8  199.63  5208.2  201.48  5431.5  203.09
#Mann= 4 ,-1 , 0
  3701.9     .05       0  4490.6     .12       0  4490.6     .07       0
  4640.4     .05       0
Bank Sta=4490.6,4640.4
XS Rating Curve= 0 ,0
Exp/Cntr=0.3,0.1

Type RM Length L Ch R = 1 ,309     ,0,0,0
BEGIN DESCRIPTION:
UNT069 IN SUCR 1.0
END DESCRIPTION:
XS GIS Cut Line= 3
      2268338.12     13377274.68       2267821.6     13377704.38
      2268051.64     13378665.76
#Sta/Elev= 30
    4471  207.44  4601.2  204.88    4665  202.45  4792.6  193.91  4842.1  192.18
  4856.4  190.72  4891.5  190.09  4963.1  182.58  4969.6  181.45    4984  180.57
  5004.6  176.46  5026.9   181.7  5047.8  182.45  5082.9  183.36  5097.2  185.35
  5106.3  185.23  5145.3  185.89  5191.2  185.21    5220   186.9  5322.5  185.52
  5392.8  186.46  5424.4  187.32  5526.6  188.73  5579.9  189.95  5711.2  196.19
  5824.1  196.64  5854.9  195.78  5906.3  197.77  5968.7  197.78  6131.4  202.04
#Mann= 8 ,-1 , 0
    4471     .05       0  4963.1     .07       0  5047.8      .1       0
  5106.3     .08       0    5220      .1       0  5392.8     .05       0
  5424.4      .1       0  5526.6     .05       0
Bank Sta=4969.6,5026.9
XS Rating Curve= 0 ,0
Exp/Cntr=0.3,0.1

Chan Stop Cuts=-1
Use User Specified Reach Order=0
Composite Channel Slope=5