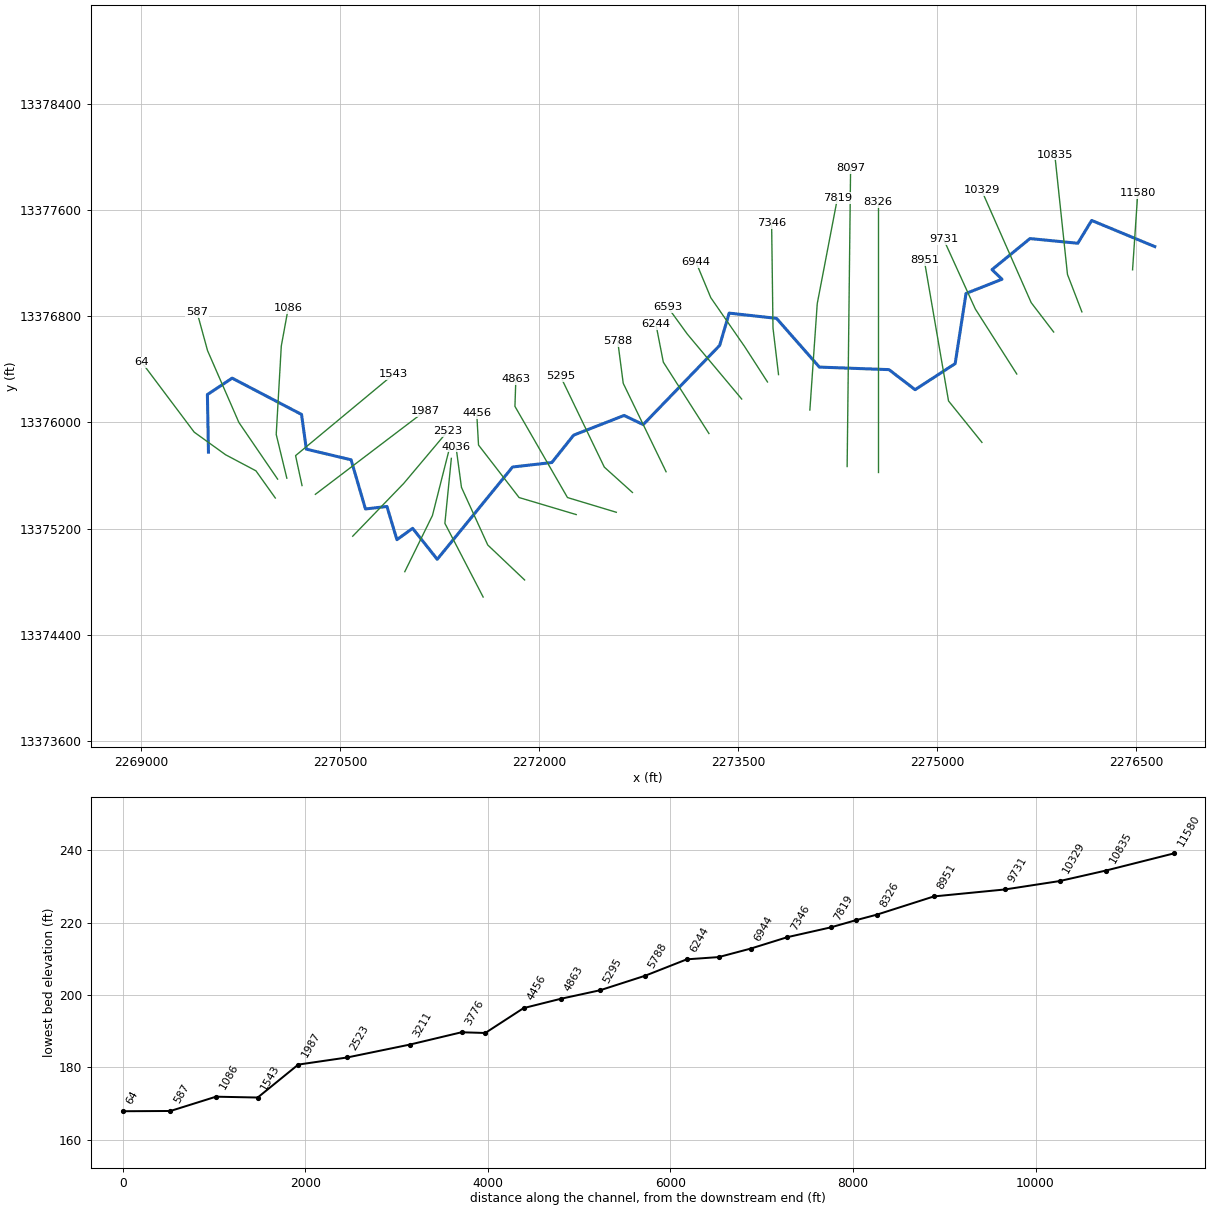
--- UNT070 IN SUCR.prj (project) ---

Proj Title=UNT070 IN SUCR Base Level Engineering
Current Plan=p01
Default Exp/Contr=0.3,0.1
English Units
Geom File=g01
Flow File=f01
Plan File=p01
Y Axis Title=Elevation
X Axis Title(PF)=Main Channel Distance
X Axis Title(XS)=Station
BEGIN DESCRIPTION:
UNT070 IN SUCR
END DESCRIPTION:
DSS Export Rating Curves= 0
DSS Export Rating Curve Sorted= 0
DSS Export Volume Flow Curves= 0
DXF OffsetX= 0
DXF OffsetY= 0
DXF ScaleX= 1
DXF ScaleY= 10

--- UNT070 IN SUCR.p01 (plan) ---

Plan Title=Multiple Run
Short Identifier=Multiple
Geom File=g01
Flow File=f01
Subcritical Flow
K Sum by GR= 0
Std Step Tol= 0.01
Critical Tol= 0.01
Num of Std Step Trials= 20
Max Error Tol= 0.3
Flow Tol Ratio= 0.001
Split Flow NTrial= 30
Split Flow Tol= 0.02
Split Flow Ratio= 0.02
Log Output Level= 0
Friction Slope Method= 1
Unsteady Friction Slope Method= 2
Unsteady Bridges Friction Slope Method= 1
Parabolic Critical Depth
Global Vel Dist=  1 , 1 , 1
Global Log Level= 0
CheckData=True
Encroach Param= -1, 0, 0, 0
BEGIN DESCRIPTION:
Multiple Run
END DESCRIPTION:

--- UNT070 IN SUCR.f01 (steady flow) ---

Flow Title=Multiple
Program Version=4.10
Number of Profiles= 7
Profile Names=10-year,25-year,50-year,1pct_min,100-year,1pct_plu,500-year
River Rch & RM=UNT070 IN SUCR,Reach-1         ,11580
     260     363     450     411     555     751     859
River Rch & RM=UNT070 IN SUCR,Reach-1         ,10835
     270     378     468     426     577     780     890
River Rch & RM=UNT070 IN SUCR,Reach-1         ,8097
     417     596     750     693     937    1267    1485
Boundary for River Rch & Prof#=UNT070 IN SUCR,Reach-1         , 1
Up Type= 0
Dn Type= 3
Dn Slope=0.0039
Boundary for River Rch & Prof#=UNT070 IN SUCR,Reach-1         , 2
Up Type= 0
Dn Type= 3
Dn Slope=0.0039
Boundary for River Rch & Prof#=UNT070 IN SUCR,Reach-1         , 3
Up Type= 0
Dn Type= 3
Dn Slope=0.0039
Boundary for River Rch & Prof#=UNT070 IN SUCR,Reach-1         , 4
Up Type= 0
Dn Type= 3
Dn Slope=0.0039
Boundary for River Rch & Prof#=UNT070 IN SUCR,Reach-1         , 5
Up Type= 0
Dn Type= 3
Dn Slope=0.0039
Boundary for River Rch & Prof#=UNT070 IN SUCR,Reach-1         , 6
Up Type= 0
Dn Type= 3
Dn Slope=0.0039
Boundary for River Rch & Prof#=UNT070 IN SUCR,Reach-1         , 7
Up Type= 0
Dn Type= 3
Dn Slope=0.0039
DSS Import GetInterval= 0
DSS Import GetPeak= 0
DSS Import FillOption= 0

--- UNT070 IN SUCR.g01 (geometry) ---

Geom Title=Existing Conditions
Program Version=4.10

River Reach=UNT070 IN SUCR  ,Reach-1
Reach XY= 30
      2276637.85     13377326.44      2276162.38     13377523.51
      2276057.85      13377351.5      2275697.72     13377386.85
      2275411.68     13377152.56      2275486.67     13377079.93
      2275215.76     13376973.01      2275133.83     13376443.95
       2274832.1     13376247.54      2274634.96     13376398.62
      2274110.65     13376417.72      2273787.76     13376785.24
      2273431.06     13376824.74      2273359.55     13376581.25
      2272783.49     13375984.15      2272639.28     13376053.08
      2272259.23     13375904.54      2272094.92     13375698.17
      2271799.08     13375664.38       2271231.5     13374968.36
      2271045.97     13375202.11      2270927.81     13375116.28
      2270852.51     13375366.71      2270690.61     13375347.96
       2270582.3      13375718.7      2270245.17     13375798.98
      2270209.08      13376060.7      2269686.28      13376334.3
      2269499.75     13376210.57      2269507.72     13375776.85

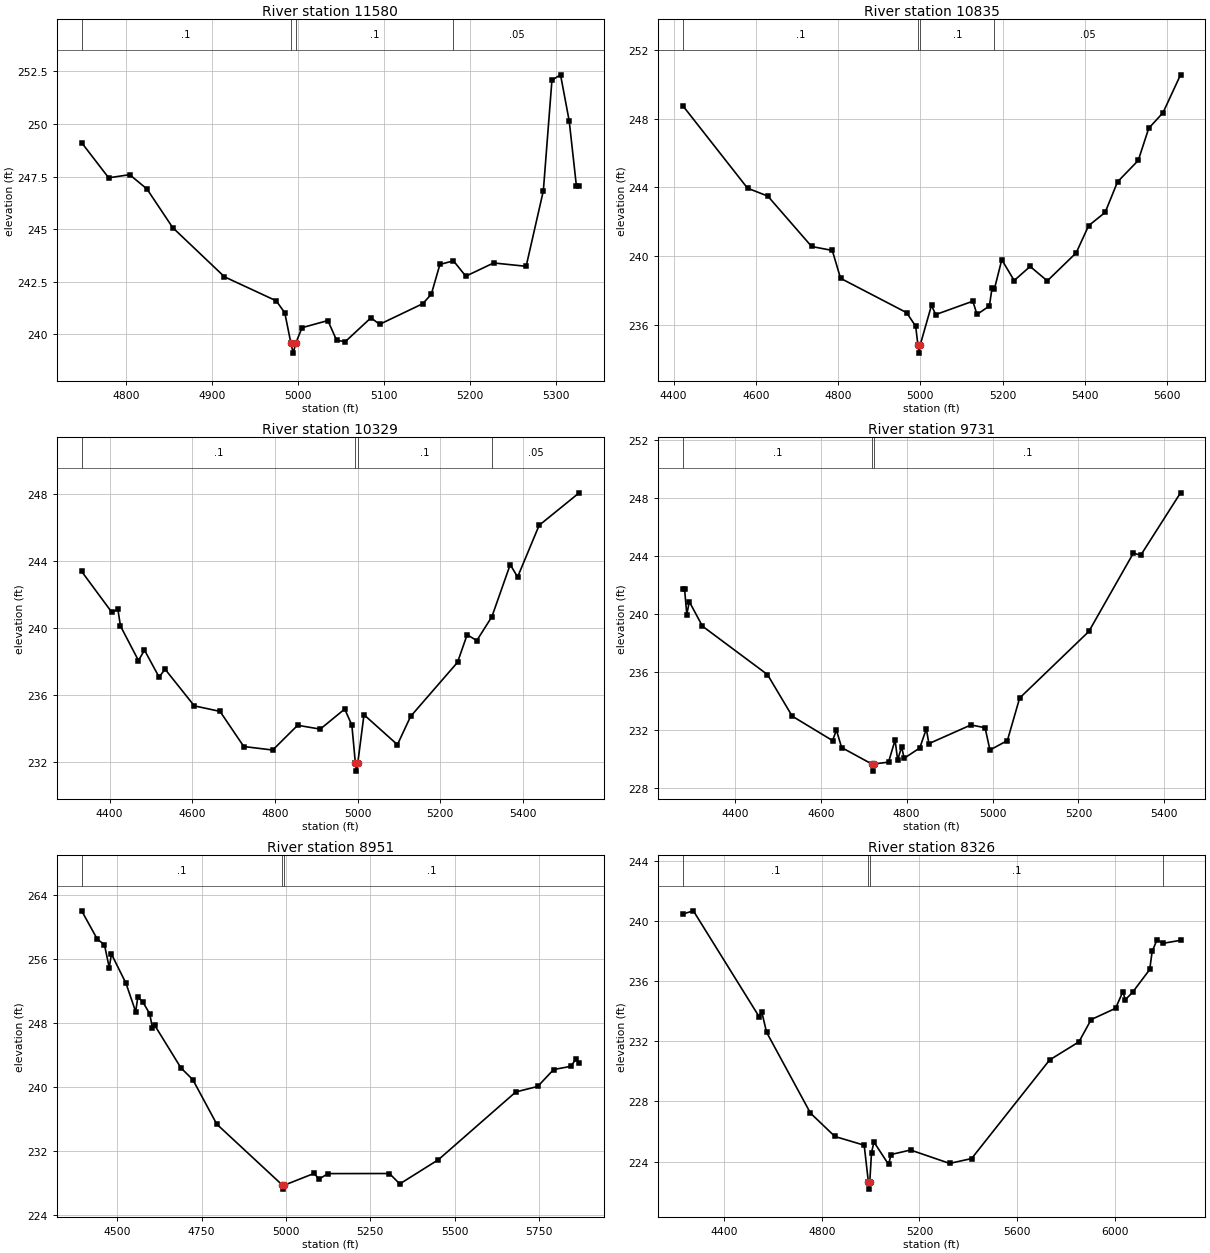
Type RM Length L Ch R = 1 ,11580   ,745,745,745
BEGIN DESCRIPTION:
UNT070 IN SUCR 21.0
END DESCRIPTION:
XS GIS Cut Line= 2
      2276470.56     13377151.18      2276509.62     13377728.46
#Sta/Elev= 30
  4748.8  249.11  4780.2  247.44  4804.6  247.59  4824.7  246.91  4854.7  245.07
  4914.9  242.73    4975  241.59    4985  241.02    4992   239.6  4994.8   239.1
    4998   239.6  5005.1  240.31  5035.1  240.65  5045.2  239.72  5055.2  239.64
  5085.2  240.78  5095.3  240.47  5145.4  241.45  5155.4   241.9  5165.4  243.32
  5181.2  243.49  5195.5  242.76  5227.9  243.39  5265.7  243.23  5285.7  246.82
  5295.7  252.09  5305.7  252.34  5315.8  250.14  5324.1  247.07  5327.4  247.07
#Mann= 4 ,-1 , 0
  4748.8      .1       0    4992     .07       0    4998      .1       0
  5181.2     .05       0
Bank Sta=4992,4998
XS Rating Curve= 0 ,0
Exp/Cntr=0.3,0.1

Type RM Length L Ch R = 1 ,10835   ,506,506,506
BEGIN DESCRIPTION:
UNT070 IN SUCR 20.0
END DESCRIPTION:
XS GIS Cut Line= 3
      2276088.62     13376834.28      2275980.11     13377116.43
      2275884.62      13378019.2
#Sta/Elev= 30
  4422.9  248.73  4579.8  243.95  4629.1  243.49  4735.7  240.56    4786  240.33
  4806.1  238.71    4967  236.71  4988.8  235.92  4994.1  234.86  4996.9  234.36
  5000.1  234.86  5027.3  237.14  5037.4   236.6  5127.9  237.38  5137.9  236.61
  5168.1   237.1  5174.4  238.13  5180.4   238.1  5198.2  239.79  5228.4  238.58
  5267.2   239.4  5308.9  238.56  5379.2  240.19  5409.4  241.77  5449.6  242.54
  5479.8  244.32  5530.1  245.56  5555.6  247.43  5590.4  248.34    5633  250.54
#Mann= 4 ,-1 , 0
  4422.9      .1       0  4994.1     .07       0  5000.1      .1       0
  5180.4     .05       0
Bank Sta=4994.1,5000.1
XS Rating Curve= 0 ,0
Exp/Cntr=0.3,0.1

Type RM Length L Ch R = 1 ,10329   ,598,598,598
BEGIN DESCRIPTION:
UNT070 IN SUCR 19.0
END DESCRIPTION:
XS GIS Cut Line= 3
      2275875.97     13376682.37      2275706.67     13376903.76
      2275333.41      13377750.1
#Sta/Elev= 30
  4332.4  243.39  4405.4  240.95    4420  241.13  4426.3  240.13  4469.8  238.07
  4484.4  238.69  4519.7  237.08  4534.2  237.55  4604.9  235.36  4667.1  235.03
  4724.6  232.93  4794.6  232.72  4854.9   234.2  4909.6  233.97  4968.8  235.17
  4986.1  234.21  4994.5  231.96  4997.3  231.46  5000.5  231.96  5015.4  234.83
  5096.3  233.04  5128.2  234.73  5241.7  237.96    5265  239.61  5288.3  239.26
  5324.9  240.69  5369.2   243.8  5387.1  243.06  5439.2  246.15  5536.1  248.09
#Mann= 4 ,-1 , 0
  4332.4      .1       0  4994.5     .07       0  5000.5      .1       0
  5324.9     .05       0
Bank Sta=4994.5,5000.5
XS Rating Curve= 0 ,0
Exp/Cntr=0.3,0.1

Type RM Length L Ch R = 1 ,9731    ,780,780,780
BEGIN DESCRIPTION:
UNT070 IN SUCR 18.0
END DESCRIPTION:
XS GIS Cut Line= 3
      2275598.14      13376365.6      2275285.66     13376856.02
      2275046.94      13377381.2
#Sta/Elev= 30
  4279.3  241.71    4283  241.71  4288.1  239.96    4294  240.85  4324.4  239.16
    4476  235.81  4533.5  232.94  4627.5  231.25  4636.5  231.97  4648.6  230.77
  4718.4  229.64  4721.2  229.14  4724.4  229.64  4757.8  229.76  4773.1  231.29
    4779  229.91  4788.3  230.81  4794.2  230.03  4830.6  230.74  4845.8  232.06
  4851.8  231.04  4949.6  232.33  4982.6  232.14  4993.9   230.6  5034.5  231.25
  5063.1  234.19  5224.2  238.79  5327.8   244.2  5345.1  244.06  5437.7  248.37
#Mann= 3 ,-1 , 0
  4279.3      .1       0  4718.4     .07       0  4724.4      .1       0
Bank Sta=4718.4,4724.4
XS Rating Curve= 0 ,0
Exp/Cntr=0.3,0.1

Type RM Length L Ch R = 1 ,8951    ,625,625,625
BEGIN DESCRIPTION:
Mapping XS 7c6a45bf
END DESCRIPTION:
XS GIS Cut Line= 3
      2275335.62     13375850.05      2275083.86     13376162.58
      2274901.57     13377221.58
#Sta/Elev= 30
    4394  261.98  4440.6  258.42  4461.5  257.76  4475.8  254.89  4482.3  256.58
  4525.4  252.93  4554.2  249.38  4560.6  251.21    4575  250.62  4595.8  249.13
  4603.8  247.38  4610.2  247.71  4688.6  242.35  4723.8  240.88  4794.9  235.32
  4989.5  227.71  4992.2  227.21  4995.5  227.71  5083.8  229.18  5097.9  228.45
  5124.4  229.15    5307  229.16  5337.6  227.86  5452.3  230.89  5681.8  239.35
  5746.8  240.04  5794.1  242.15  5844.8  242.55  5861.6  243.52  5869.9  242.92
#Mann= 3 ,-1 , 0
    4394      .1       0  4989.5     .07       0  4995.5      .1       0
Bank Sta=4989.5,4995.5
XS Rating Curve= 0 ,0
Exp/Cntr=0.3,0.1

Type RM Length L Ch R = 1 ,8326    ,229,229,229
BEGIN DESCRIPTION:
UNT070 IN SUCR 17.0
END DESCRIPTION:
XS GIS Cut Line= 2
      2274554.35     13375624.43      2274554.35     13377663.13
#Sta/Elev= 30
  4231.2  240.46  4273.6  240.67  4543.6  233.62  4553.6  233.97  4573.6   232.6
  4753.6  227.22  4853.6  225.67  4973.6  225.09  4990.6  222.67  4993.4  222.17
  4996.6  222.67  5003.6  224.59  5013.6   225.3  5073.6  223.81  5083.6  224.47
  5163.6  224.77  5323.6  223.88  5413.6   224.2  5733.6  230.76  5853.6  231.96
  5903.6  233.44  6003.6  234.19  6033.6  235.29  6043.6  234.76  6073.6  235.26
  6143.6  236.77  6153.6  237.97  6173.6  238.75  6198.2  238.51  6269.9  238.71
#Mann= 4 ,-1 , 0
  4231.2      .1       0  4990.6     .07       0  4996.6      .1       0
  6198.2     .05       0
Bank Sta=4990.6,4996.6
XS Rating Curve= 0 ,0
Exp/Cntr=0.3,0.1

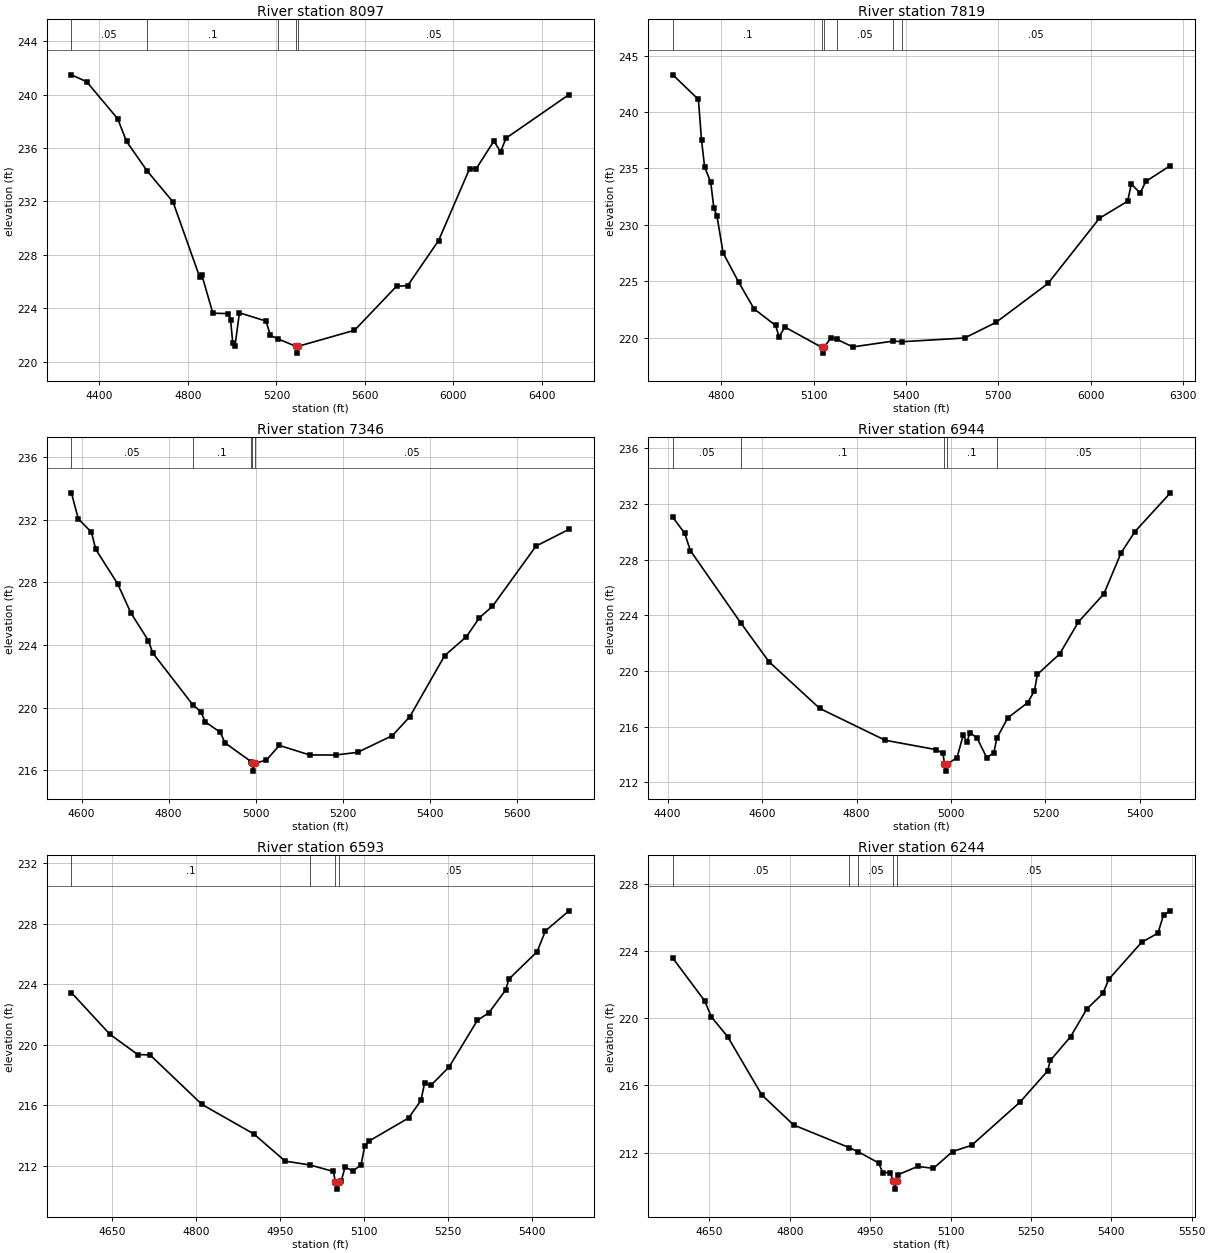
Type RM Length L Ch R = 1 ,8097    ,278,278,278
BEGIN DESCRIPTION:
UNT070 IN SUCR 16.0
END DESCRIPTION:
XS GIS Cut Line= 2
      2274319.97     13375667.75      2274346.01      13377916.1
#Sta/Elev= 30
  4273.7  241.48  4342.8  240.96  4482.8  238.19  4522.8  236.49  4616.1  234.28
  4732.8  231.96  4852.8  226.36  4862.8   226.5  4912.8  223.63  4982.9   223.6
  4992.9  223.12  5002.9  221.39  5012.9  221.18  5032.9  223.66  5152.9  223.04
  5172.9  221.97  5205.1  221.72  5289.9  221.14  5292.6  220.64  5295.9  221.14
  5552.9  222.35  5742.9  225.65  5792.9  225.69  5932.9  229.07  6072.9  234.45
  6102.9  234.45  6182.9  236.52  6212.9  235.72  6237.9  236.74  6522.2     240
#Mann= 5 ,-1 , 0
  4273.7     .05       0  4616.1      .1       0  5205.1     .05       0
  5289.9     .07       0  5295.9     .05       0
Bank Sta=5289.9,5295.9
XS Rating Curve= 0 ,0
Exp/Cntr=0.3,0.1

Type RM Length L Ch R = 1 ,7819    ,473,473,473
BEGIN DESCRIPTION:
Mapping XS fbd03f09
END DESCRIPTION:
XS GIS Cut Line= 3
      2274039.14     13376093.91      2274094.69     13376895.95
      2274247.21     13377693.23
#Sta/Elev= 30
    4643   243.3  4726.1  241.12  4736.2  237.52  4746.2  235.15  4766.2  233.77
  4776.3  231.48  4786.3   230.8  4806.3  227.52  4856.5  224.94  4906.6  222.57
  4976.7  221.09  4988.1  220.09  5006.8  220.95  5127.6  219.14  5130.3  218.64
  5133.6  219.14  5157.2  220.02  5176.8  219.85  5227.3  219.19  5359.3  219.71
  5387.4  219.65  5590.4  219.98  5692.2  221.36  5861.2  224.81  6028.2  230.59
  6119.9   232.1  6131.7  233.62  6160.6  232.82  6178.7  233.85  6258.7  235.26
#Mann= 6 ,-1 , 0
    4643      .1       0  5127.6     .07       0  5133.6      .1       0
  5176.8     .05       0  5359.3      .1       0  5387.4     .05       0
Bank Sta=5127.6,5133.6
XS Rating Curve= 0 ,0
Exp/Cntr=0.3,0.1

Type RM Length L Ch R = 1 ,7346    ,402,402,402
BEGIN DESCRIPTION:
UNT070 IN SUCR 15.0
END DESCRIPTION:
XS GIS Cut Line= 3
      2273803.02      13376361.2      2273761.36     13376711.92
      2273750.95     13377502.77
#Sta/Elev= 30
  4576.6  233.71  4592.4  232.05  4622.6   231.2  4632.6   230.1    4683   227.9
  4713.2  226.05  4753.6  224.28  4763.6  223.49  4855.2   220.2  4874.3  219.73
  4884.4  219.09  4918.9  218.43  4929.8  217.75  4989.6  216.56  4991.7  216.45
  4994.5  215.95  4997.7  216.45  5024.7  216.65  5054.7  217.59  5124.7  216.98
  5184.7  216.98  5234.7  217.15  5314.8  218.22  5354.8  219.43  5434.8  223.32
  5484.8  224.53  5514.8  225.74  5544.8  226.47  5644.8  230.31  5720.7  231.38
#Mann= 5 ,-1 , 0
  4576.6     .05       0  4855.2      .1       0  4989.6     .05       0
  4991.7    .035       0  4997.7     .05       0
Bank Sta=4991.7,4997.7
XS Rating Curve= 0 ,0
Exp/Cntr=0.3,0.1

Type RM Length L Ch R = 1 ,6944    ,351,351,351
BEGIN DESCRIPTION:
UNT070 IN SUCR 14.0
END DESCRIPTION:
XS GIS Cut Line= 4
      2273719.69     13376305.66      2273549.55     13376569.56
      2273292.61     13376941.09      2273182.12     13377206.93
#Sta/Elev= 30
  4410.9  231.05  4436.1   229.9  4448.1  228.65  4555.5  223.42  4614.6  220.66
    4722   217.3  4860.7  215.01  4968.1  214.34    4983  214.07  4986.1  213.29
  4988.8  212.79  4992.1  213.29  5012.8  213.77  5025.6  215.36  5033.7  214.88
  5039.8  215.55  5054.7   215.2  5075.6  213.76  5090.5   214.1  5097.3  215.19
  5120.2  216.62  5162.1  217.71  5176.5  218.55  5182.9  219.75    5230  221.22
  5269.5  223.51  5323.6  225.54  5360.1  228.49  5389.4  230.02  5464.5  232.81
#Mann= 5 ,-1 , 0
  4410.9     .05       0  4555.5      .1       0  4986.1     .07       0
  4992.1      .1       0  5097.3     .05       0
Bank Sta=4986.1,4992.1
XS Rating Curve= 0 ,0
Exp/Cntr=0.3,0.1

Type RM Length L Ch R = 1 ,6593    ,349,349,349
BEGIN DESCRIPTION:
Mapping XS f817e39d
END DESCRIPTION:
XS GIS Cut Line= 3
      2273525.26     13376177.18      2273115.52     13376666.78
      2272969.68     13376868.18
#Sta/Elev= 30
  4578.2  223.43    4647  220.67  4696.4  219.34  4718.5  219.31  4810.9  216.04
  4903.3  214.09  4959.3  212.29  5003.2  212.04  5045.2  211.61  5048.7  210.94
  5051.4  210.44  5054.7  210.94  5059.5     211    5066   211.9  5080.3  211.64
  5094.6  212.05  5101.1   213.3  5108.9  213.62  5179.2  215.14  5201.3   216.3
  5207.8  217.44    5219   217.3  5251.6  218.52  5301.8  221.59  5322.7  222.11
  5352.1  223.59  5358.3  224.33  5408.5  226.14  5423.2  227.51  5465.3  228.84
#Mann= 4 ,-1 , 0
  4578.2      .1       0  5003.2     .05       0  5048.7     .07       0
  5054.7     .05       0
Bank Sta=5048.7,5054.7
XS Rating Curve= 0 ,0
Exp/Cntr=0.3,0.1

Type RM Length L Ch R = 1 ,6244    ,456,456,456
BEGIN DESCRIPTION:
UNT070 IN SUCR 13.0
END DESCRIPTION:
XS GIS Cut Line= 3
      2273278.69     13375916.82      2272934.97     13376454.97
       2272879.4     13376739.74
#Sta/Elev= 30
  4581.6  223.58    4641  221.04  4653.6  220.08    4684   218.9  4747.8  215.43
  4807.1  213.64  4910.4   212.3  4927.4  212.05  4965.8  211.38  4973.2  210.81
  4986.9   210.8  4993.2  210.32    4996  209.82  4999.2  210.32  5002.1  210.68
  5038.5  211.17  5068.1  211.06  5103.7  212.06  5139.3  212.43  5229.5     215
  5281.1  216.86  5286.2  217.49    5324   218.9  5354.5  220.56  5384.3  221.48
  5395.3  222.32  5456.4  224.52    5487  225.07  5497.6  226.16  5510.3   226.4
#Mann= 5 ,-1 , 0
  4581.6     .05       0  4910.4      .1       0  4927.4     .05       0
  4993.2    .035       0  4999.2     .05       0
Bank Sta=4993.2,4999.2
XS Rating Curve= 0 ,0
Exp/Cntr=0.3,0.1

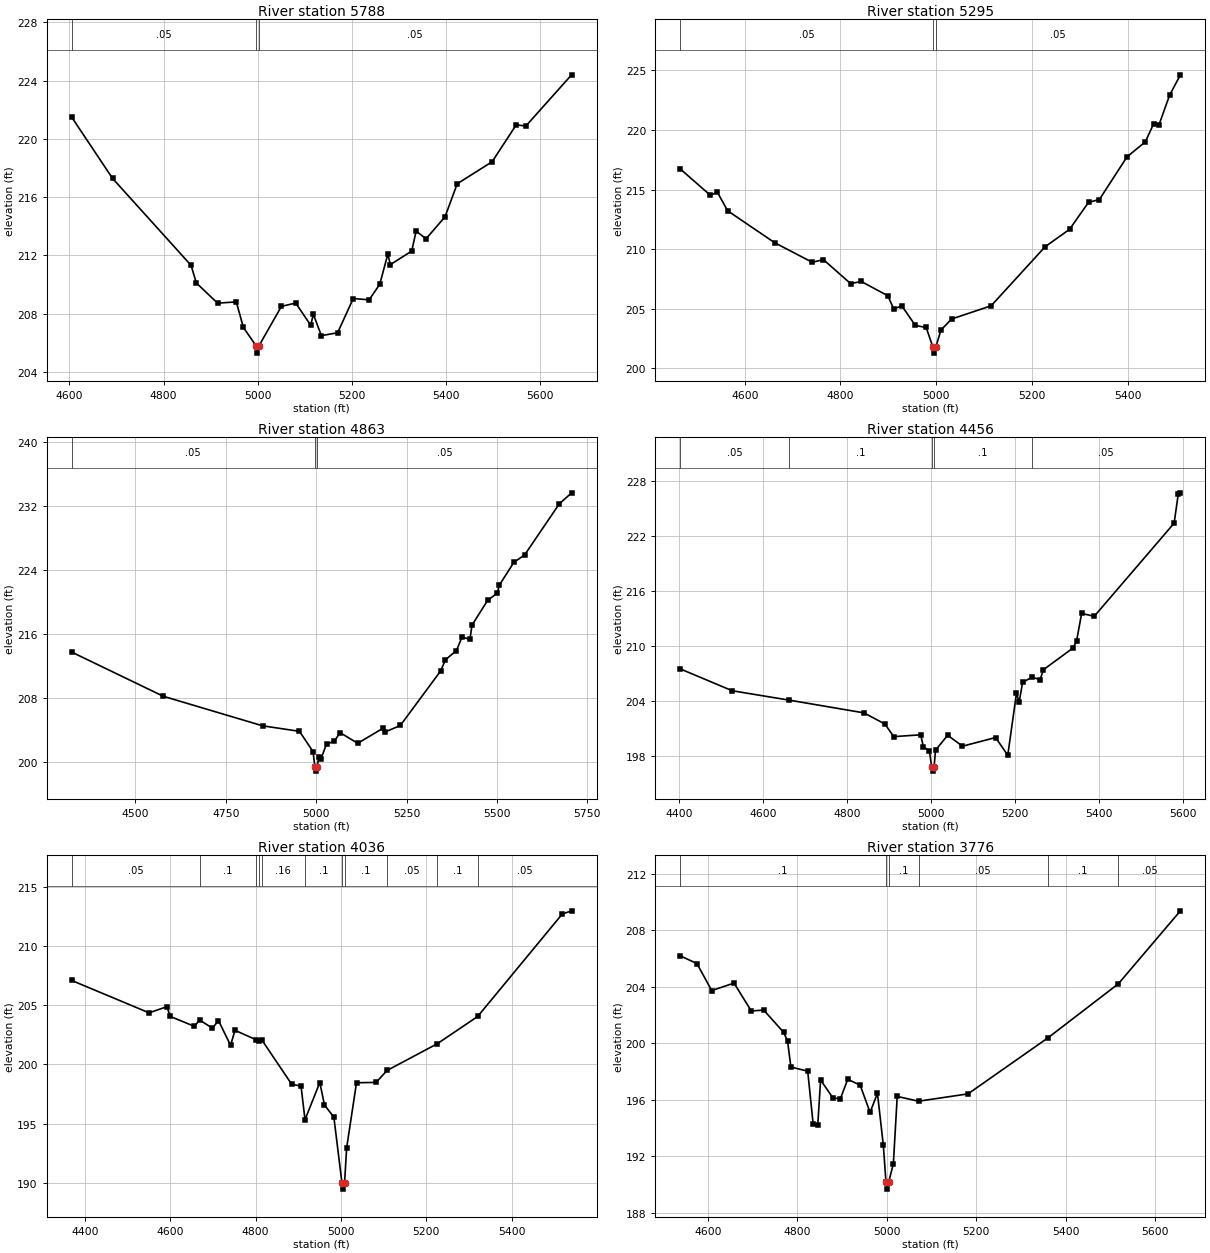
Type RM Length L Ch R = 1 ,5788    ,493,493,493
BEGIN DESCRIPTION:
UNT070 IN SUCR 12.0
END DESCRIPTION:
XS GIS Cut Line= 3
      2272955.81     13375628.56      2272632.88     13376295.25
       2272591.4     13376613.27
#Sta/Elev= 30
  4604.8  221.51  4691.8  217.29  4858.5  211.32  4869.7  210.11  4914.8  208.72
  4954.5  208.81  4969.6  207.05  4996.6  205.79  4999.4  205.29  5002.6  205.79
  5050.3   208.5  5080.7  208.73  5112.5   207.2  5118.1  207.96  5135.1  206.49
  5169.6  206.69  5202.8  209.04  5236.5  208.95  5259.1  210.02  5276.1  212.08
  5281.7  211.37  5326.9   212.3  5336.3  213.67  5357.3  213.14  5397.6  214.65
  5423.5  216.92  5497.5  218.43  5548.9  220.97  5569.1  220.88  5666.3   224.4
#Mann= 3 ,-1 , 0
  4604.8     .05       0  4996.6    .035       0  5002.6     .05       0
Bank Sta=4996.6,5002.6
XS Rating Curve= 0 ,0
Exp/Cntr=0.3,0.1

Type RM Length L Ch R = 1 ,5295    ,432,432,432
BEGIN DESCRIPTION:
UNT070 IN SUCR 11.0
END DESCRIPTION:
XS GIS Cut Line= 3
       2272702.3     13375472.36      2272490.52     13375663.31
      2272160.64     13376347.37
#Sta/Elev= 30
  4465.6  216.72  4528.5  214.51  4542.7  214.79  4564.3  213.22    4663  210.53
  4741.1   208.9  4764.5  209.12  4821.3  207.11  4843.5  207.29    4899  206.09
  4911.3  204.99  4928.3  205.24  4956.5   203.6  4979.1  203.43  4993.2  201.78
  4995.9  201.28  4999.2  201.78    5010  203.22  5032.2  204.14  5114.8  205.25
  5227.8  210.21  5278.6  211.66  5318.3  213.93  5340.9  214.16  5398.6  217.74
  5436.9     219    5454  220.49  5465.2   220.4  5487.7  222.92  5510.2  224.62
#Mann= 3 ,-1 , 0
  4465.6     .05       0  4993.2    .035       0  4999.2     .05       0
Bank Sta=4993.2,4999.2
XS Rating Curve= 0 ,0
Exp/Cntr=0.3,0.1

Type RM Length L Ch R = 1 ,4863    ,407,407,407
BEGIN DESCRIPTION:
UNT070 IN SUCR 10.0
END DESCRIPTION:
XS GIS Cut Line= 4
      2272580.76     13375323.04      2272212.74     13375434.14
      2271816.91     13376121.64      2271823.85      13376326.5
#Sta/Elev= 30
  4323.6  213.76  4577.5  208.24  4851.9  204.56  4953.9  203.87  4991.3  201.35
  4996.6  199.41  4999.4  198.91  5002.6  199.41    5007  200.62  5012.8  200.38
  5028.6  202.29  5050.2  202.63    5066  203.71    5115  202.38  5183.8  204.23
  5189.5  203.77  5232.7   204.6  5344.7  211.43  5357.3  212.79  5387.8  213.94
  5403.5  215.64  5425.2  215.33  5430.9  217.11  5474.1   220.2  5501.3  221.12
  5506.5  222.11  5546.6  224.93  5576.6  225.88  5672.2  232.23  5706.3  233.61
#Mann= 3 ,-1 , 0
  4323.6     .05       0  4996.6    .035       0  5002.6     .05       0
Bank Sta=4996.6,5002.6
XS Rating Curve= 0 ,0
Exp/Cntr=0.3,0.1

Type RM Length L Ch R = 1 ,4456    ,420,420,420
BEGIN DESCRIPTION:
UNT070 IN SUCR 9.0
END DESCRIPTION:
XS GIS Cut Line= 4
      2272278.67     13375305.68      2271848.16     13375434.14
      2271542.61     13375829.97      2271528.78     13376071.86
#Sta/Elev= 30
  4402.5  207.48  4526.3   205.1  4661.7  204.08  4840.2  202.69  4890.1  201.47
  4910.9   200.1  4975.2   200.3  4981.5  199.02    4996  198.52  5001.2  196.84
    5004  196.34  5007.2  196.84  5010.5  198.62  5039.5  200.25  5074.8  199.06
  5153.7     200  5182.7  198.07  5203.5  204.85  5209.8  203.84    5218  206.01
  5240.5  206.59  5259.6  206.31  5267.8   207.4  5338.4  209.77  5346.6  210.52
  5358.7  213.53  5388.8  213.22  5579.1  223.37  5589.1  226.58  5594.1  226.68
#Mann= 5 ,-1 , 0
  4402.5     .05       0  4661.7      .1       0  5001.2     .07       0
  5007.2      .1       0  5240.5     .05       0
Bank Sta=5001.2,5007.2
XS Rating Curve= 0 ,0
Exp/Cntr=0.3,0.1

Type RM Length L Ch R = 1 ,4036    ,260,260,260
BEGIN DESCRIPTION:
UNT070 IN SUCR 8.0
END DESCRIPTION:
XS GIS Cut Line= 4
      2271889.83     13374812.62      2271612.05      13375076.5
      2271414.13     13375510.53       2271372.6     13375818.58
#Sta/Elev= 30
  4369.2   207.1  4550.7  204.36  4592.8  204.88    4600  204.06  4656.7  203.22
  4669.3  203.75  4699.1  203.06  4713.3  203.71  4741.6  201.61  4751.9  202.88
  4801.7  202.08  4808.9  201.98  4814.4  202.09  4884.6  198.33  4906.6  198.16
  4915.9  195.33  4950.6  198.47  4961.5  196.57  4983.5  195.54  5002.5  189.96
  5005.3  189.46  5008.5  189.96  5013.4  192.94  5036.5  198.45  5082.4  198.48
  5108.1  199.49  5225.3  201.74  5320.2  204.05  5518.3  212.71  5540.2  212.98
#Mann= 11 ,-1 , 0
  4369.2     .05       0  4669.3      .1       0  4801.7     .05       0
  4808.9      .1       0  4814.4     .16       0  4915.9      .1       0
  5002.5     .07       0  5008.5      .1       0  5108.1     .05       0
  5225.3      .1       0  5320.2     .05       0
Bank Sta=5002.5,5008.5
XS Rating Curve= 0 ,0
Exp/Cntr=0.3,0.1

Type RM Length L Ch R = 1 ,3776    ,565,565,565
BEGIN DESCRIPTION:
UNT070 IN SUCR 7.0
END DESCRIPTION:
XS GIS Cut Line= 3
      2271577.33     13374684.13      2271289.13      13375239.7
      2271337.75     13375729.32
#Sta/Elev= 30
  4538.6  206.19  4575.7  205.64  4608.7  203.73  4658.6  204.26  4697.2  202.28
  4724.9  202.35  4769.2  200.78  4778.2  200.17  4785.7  198.31  4823.3  198.02
  4835.6  194.24  4845.8  194.21  4852.1  197.39  4879.8  196.12  4896.3  196.06
  4912.8  197.44  4940.5  197.03  4962.7   195.1  4979.2  196.45  4992.3  192.79
  4998.3  190.16    5001  189.66  5004.3  190.16  5014.8  191.46  5023.4  196.23
    5071  195.89  5181.7  196.41  5360.4  200.38  5517.8  204.21  5656.5  209.38
#Mann= 6 ,-1 , 0
  4538.6      .1       0  4998.3     .07       0  5004.3      .1       0
    5071     .05       0  5360.4      .1       0  5517.8     .05       0
Bank Sta=4998.3,5004.3
XS Rating Curve= 0 ,0
Exp/Cntr=0.3,0.1

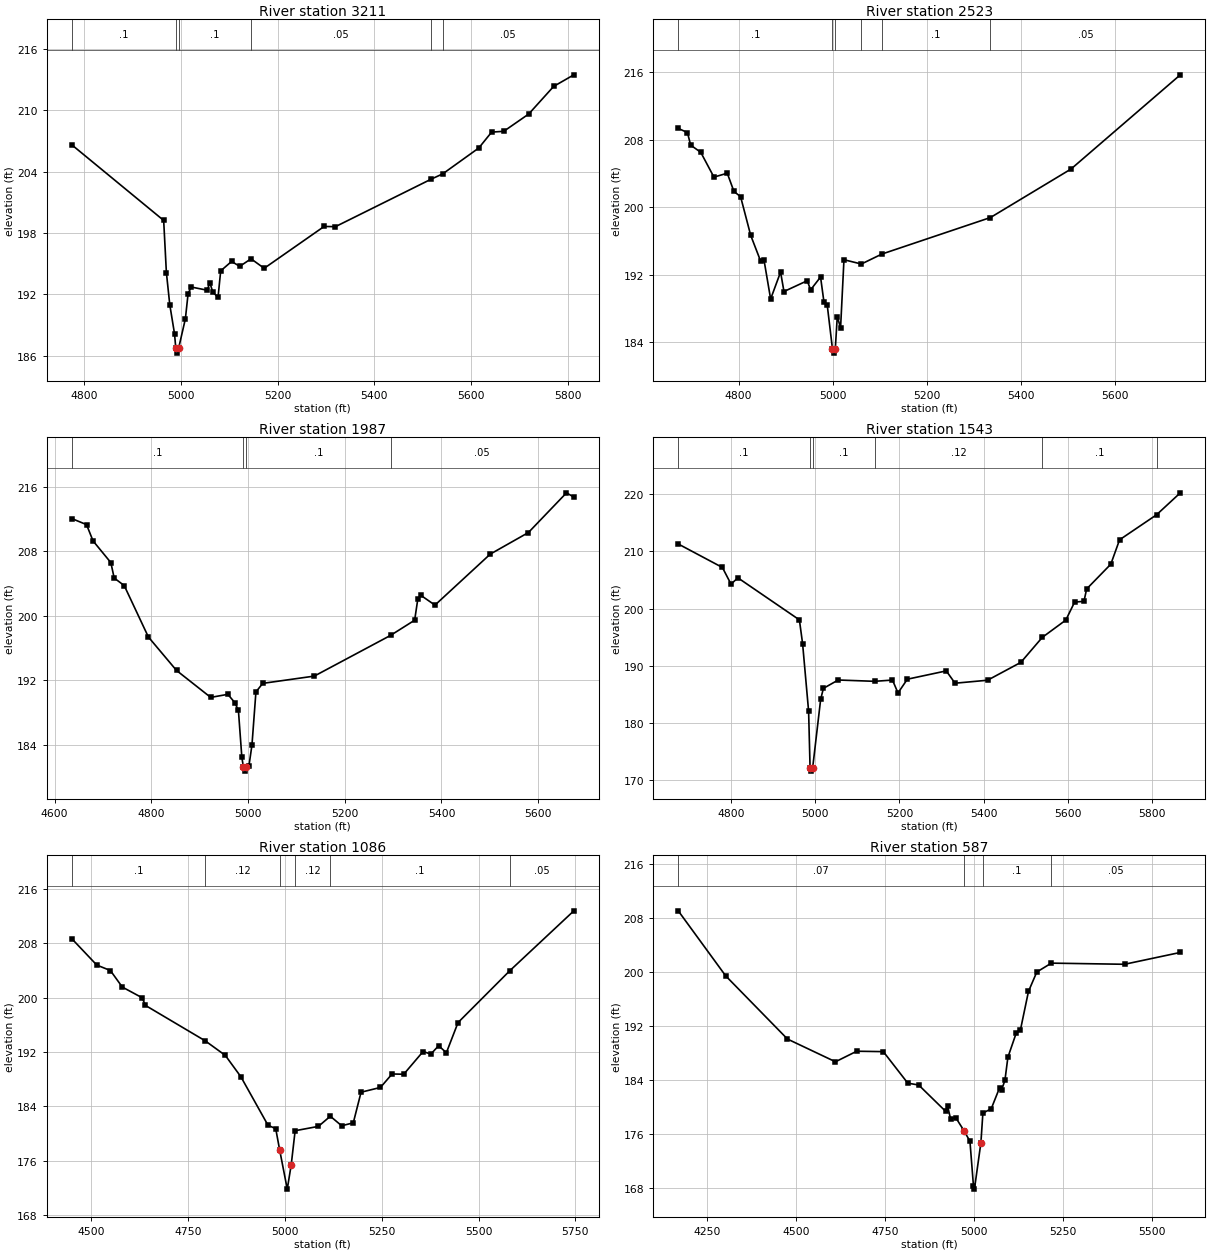
Type RM Length L Ch R = 1 ,3211    ,688,688,688
BEGIN DESCRIPTION:
UNT070 IN SUCR 6.0
END DESCRIPTION:
XS GIS Cut Line= 3
      2270987.04     13374875.09      2271195.38     13375298.72
      2271334.27     13375847.32
#Sta/Elev= 30
  4774.3  206.62  4964.3  199.23  4969.9  194.14  4976.9     191  4986.8  188.13
  4989.3  186.76  4992.1  186.26  4995.3  186.76  5009.2  189.62  5014.8  192.08
  5021.4  192.72  5054.2  192.41  5059.8  193.14    5066   192.2  5076.7  191.73
  5082.2   194.3  5104.7  195.22  5121.6  194.74  5144.9  195.48  5172.1  194.55
    5296  198.64  5319.4  198.62  5517.6  203.27  5541.2  203.78  5615.8  206.31
  5642.3  207.86  5667.4  207.94    5719  209.63  5770.6  212.33  5812.3  213.46
#Mann= 6 ,-1 , 0
  4774.3      .1       0  4989.3     .07       0  4995.3      .1       0
  5144.9     .05       0  5517.6      .1       0  5541.2     .05       0
Bank Sta=4989.3,4995.3
XS Rating Curve= 0 ,0
Exp/Cntr=0.3,0.1

Type RM Length L Ch R = 1 ,2523    ,536,536,536
BEGIN DESCRIPTION:
UNT070 IN SUCR 5.0
END DESCRIPTION:
XS GIS Cut Line= 3
      2270594.69     13375142.48      2270980.11     13375541.78
      2271309.02     13375933.02
#Sta/Elev= 30
    4672  209.32  4691.5  208.83  4698.4  207.34  4719.8  206.49  4747.8  203.55
  4776.1  204.01  4790.3  201.85  4804.4  201.23  4825.8  196.66  4846.9   193.6
  4854.1  193.73  4868.2   189.1  4889.3   192.3  4896.5  189.99  4945.9  191.27
  4953.1  190.19  4974.2  191.71  4981.4  188.75  4988.4  188.37  4999.5  183.19
  5002.3  182.69  5005.5  183.19  5009.7  187.03  5016.7  185.68  5023.9  193.76
  5060.8  193.25  5104.4  194.43    5335  198.76  5506.1  204.51  5738.1  215.67
#Mann= 6 ,-1 , 0
    4672      .1       0  4999.5     .07       0  5005.5      .1       0
  5060.8     .05       0  5104.4      .1       0    5335     .05       0
Bank Sta=4999.5,5005.5
XS Rating Curve= 0 ,0
Exp/Cntr=0.3,0.1

Type RM Length L Ch R = 1 ,1987    ,444,444,444
BEGIN DESCRIPTION:
UNT070 IN SUCR 4.0
END DESCRIPTION:
XS GIS Cut Line= 2
      2270313.42     13375458.43      2271139.79     13376086.89
#Sta/Elev= 30
  4635.5  212.03    4666  211.28  4679.5  209.26  4716.3  206.57  4723.2  204.66
    4744  203.72  4793.9  197.35  4852.1   193.2  4922.8  189.86  4958.2  190.24
  4972.7  189.21  4980.1  188.24  4987.2  182.42  4990.5  181.22  4993.3  180.72
  4996.5  181.22  5001.8  181.35  5008.1  183.95  5016.3  190.54  5030.4   191.6
    5137   192.5  5294.8  197.55  5344.5  199.43  5351.1  202.07  5357.4  202.51
  5386.5   201.3  5500.8  207.62  5579.8   210.3  5658.5  215.22  5673.7  214.69
#Mann= 4 ,-1 , 0
  4635.5      .1       0  4990.5     .07       0  4996.5      .1       0
  5294.8     .05       0
Bank Sta=4990.5,4996.5
XS Rating Curve= 0 ,0
Exp/Cntr=0.3,0.1

Type RM Length L Ch R = 1 ,1543    ,457,457,457
BEGIN DESCRIPTION:
UNT070 IN SUCR 3.0
END DESCRIPTION:
XS GIS Cut Line= 3
      2270212.75     13375524.37      2270164.13     13375750.11
      2270903.23      13376364.3
#Sta/Elev= 30
  4674.8  211.28  4779.6  207.18  4800.1  204.27  4816.4  205.37  4962.4  198.03
    4970   193.9  4984.3  182.08  4987.8  172.12  4990.5  171.62  4993.8  172.12
  5012.9  184.15  5019.4  186.07  5054.6  187.53    5141   187.3  5183.4  187.52
  5196.5  185.27  5218.7  187.67  5311.1  189.12  5331.9  186.97  5409.1  187.49
  5488.2  190.61    5539  194.97  5594.9  197.99  5615.8  201.14  5637.9  201.26
  5644.4  203.43  5701.7  207.75  5722.5  212.01  5810.2  216.37  5866.7  220.21
#Mann= 6 ,-1 , 0
  4674.8      .1       0  4987.8     .07       0  4993.8      .1       0
    5141     .12       0    5539      .1       0  5810.2     .05       0
Bank Sta=4987.8,4993.8
XS Rating Curve= 0 ,0
Exp/Cntr=0.3,0.1

Type RM Length L Ch R = 1 ,1086    ,499,499,499
BEGIN DESCRIPTION:
UNT070 IN SUCR 2.0
END DESCRIPTION:
XS GIS Cut Line= 4
      2270098.16     13375579.98       2270018.3     13375909.84
      2270056.49      13376576.5      2270108.58     13376861.23
#Sta/Elev= 30
  4449.3  208.65  4513.9  204.77    4549  203.97  4579.8  201.54  4631.3  199.96
  4639.4  198.85  4793.9  193.64  4845.8   191.5  4885.9  188.37    4956  181.24
    4976  180.73    4986  177.66  5005.8  171.85  5016.1  175.46  5026.1  180.43
  5086.2  181.07    5117  182.56  5146.3  181.16  5176.3  181.59  5196.4  186.09
  5246.5  186.79  5276.5  188.77  5306.6  188.73  5356.6  192.07  5376.7  191.69
  5396.7  192.92  5416.7  191.89  5446.8  196.32  5580.5  203.94  5745.9  212.74
#Mann= 6 ,-1 , 0
  4449.3      .1       0  4793.9     .12       0    4986     .07       0
  5026.1     .12       0    5117      .1       0  5580.5     .05       0
Bank Sta=4986,5016.1
XS Rating Curve= 0 ,0
Exp/Cntr=0.3,0.1

Type RM Length L Ch R = 1 ,587     ,523,523,523
BEGIN DESCRIPTION:
Mapping XS 29004ef0
END DESCRIPTION:
XS GIS Cut Line= 4
       2270028.7     13375573.05      2269737.05     13376000.11
      2269500.94     13376541.78       2269421.3     13376832.64
#Sta/Elev= 30
    4169  209.03  4302.2  199.42  4475.7  190.08  4610.4  186.72  4670.1  188.28
  4744.8  188.22  4813.5  183.56    4844  183.29  4919.7   179.4  4925.1   180.2
  4933.5   178.3  4948.6  178.43    4972  176.47    4988  174.97  4997.8   168.4
  5000.6   167.9  5018.8  174.79  5024.3  179.14  5047.7  179.77  5071.1  182.87
  5076.6  182.53  5086.2  183.98  5094.5  187.38    5118  190.98  5129.9  191.47
  5152.3  197.12  5175.7  199.99  5216.6   201.3    5422  201.13  5578.6  202.88
#Mann= 4 ,-1 , 0
    4169     .07       0    4972     .07       0  5024.3      .1       0
  5216.6     .05       0
Bank Sta=4972,5018.8
XS Rating Curve= 0 ,0
Exp/Cntr=0.3,0.1

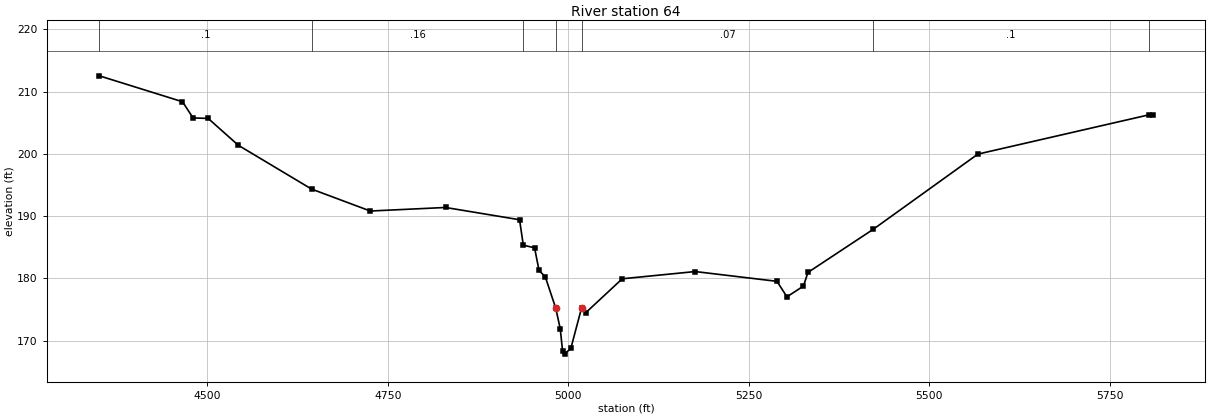
Type RM Length L Ch R = 1 ,64      ,0,0,0
BEGIN DESCRIPTION:
UNT070 IN SUCR 1.0
END DESCRIPTION:
XS GIS Cut Line= 5
      2270011.37     13375430.64      2269865.52     13375635.53
      2269636.36     13375757.06      2269400.24      13375927.2
      2269005.58     13376453.42
#Sta/Elev= 30
  4350.2  212.52  4465.4  208.36  4480.1  205.76    4501  205.68  4542.8  201.37
  4644.2  194.34  4725.7  190.81  4829.9  191.38  4932.5  189.41  4937.7  185.33
  4953.3   184.9  4959.5  181.26  4968.1  180.26  4982.7  175.19  4988.9  171.89
  4992.1  168.33  4994.8  167.83  5003.6  168.77  5018.4  175.24  5024.5  174.51
  5074.8  179.93  5175.9  181.09  5289.2  179.52    5303  177.03  5325.9  178.76
  5332.1  180.95  5422.4  187.86  5567.6  199.95  5805.1  206.27  5809.9  206.24
#Mann= 7 ,-1 , 0
  4350.2      .1       0  4644.2     .16       0  4937.7     .07       0
  4982.7     .03       0  5018.4     .07       0  5422.4      .1       0
  5805.1     .05       0
Bank Sta=4982.7,5018.4
XS Rating Curve= 0 ,0
Exp/Cntr=0.3,0.1

Chan Stop Cuts=-1
Use User Specified Reach Order=0
Composite Channel Slope=5