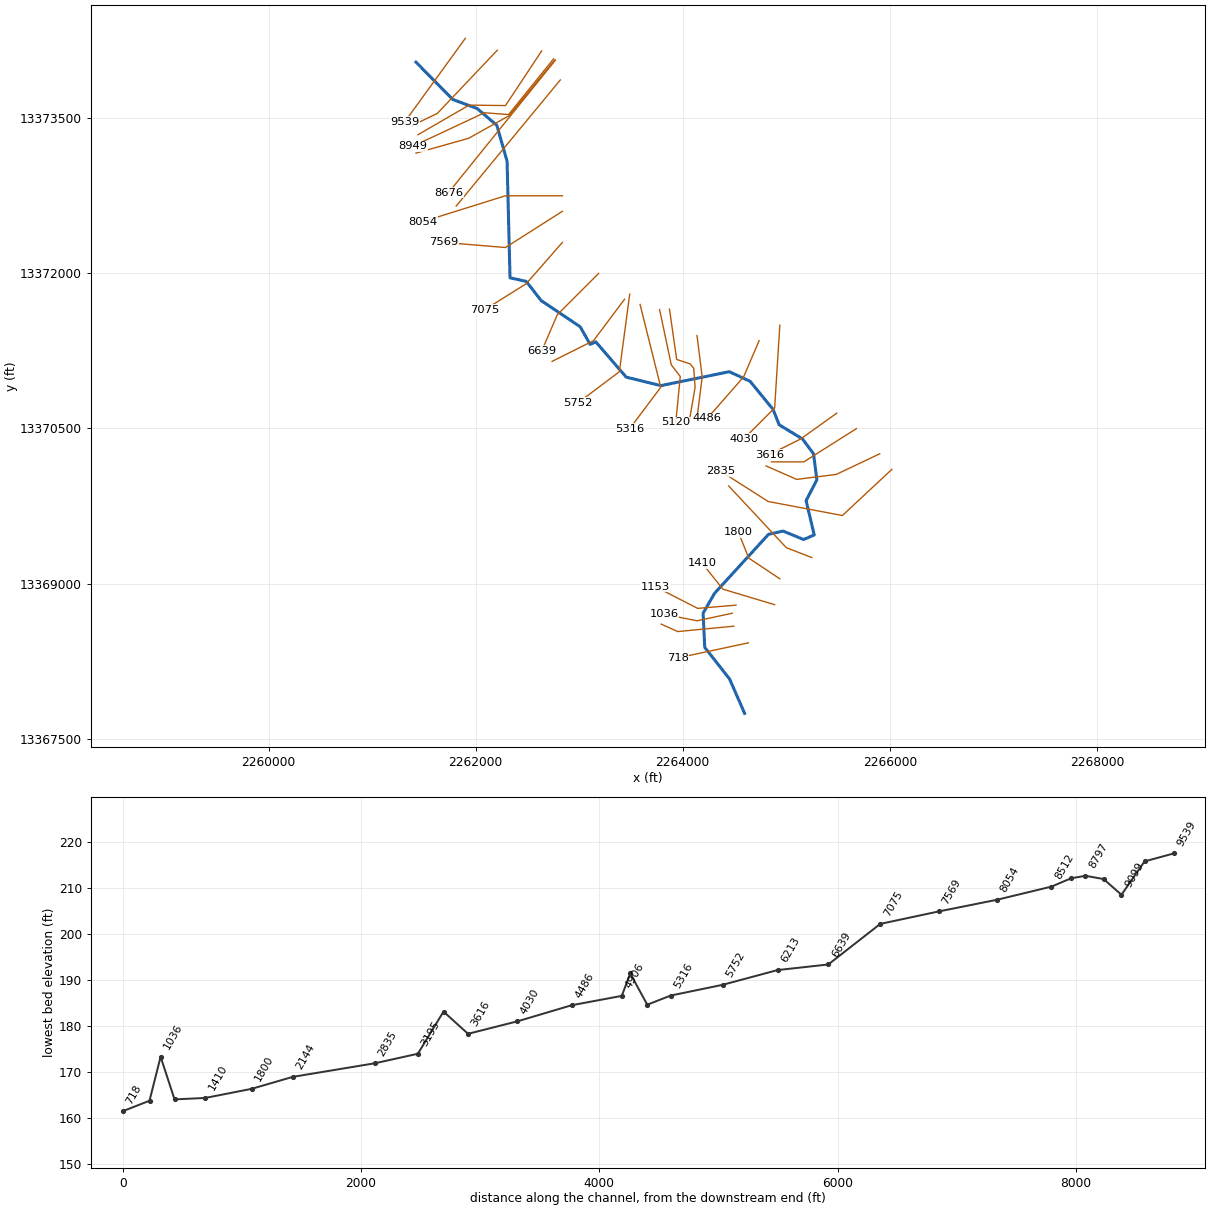
--- UNT071 IN SUCR.prj (project) ---

Proj Title=UNT071 IN SUCR Base Level Engineering
Current Plan=p01
Default Exp/Contr=0.3,0.1
English Units
Geom File=g01
Flow File=f01
Plan File=p01
BEGIN DESCRIPTION:
UNT071 IN SUCR
END DESCRIPTION:

--- UNT071 IN SUCR.p01 (plan) ---

Plan Title=Multiple Run
Short Identifier=Multiple
Geom File=g01
Flow File=f01
Subcritical Flow
K Sum by GR= 0
Std Step Tol= 0.01
Critical Tol= 0.01
Num of Std Step Trials= 20
Max Error Tol= 0.3
Flow Tol Ratio= 0.001
Split Flow NTrial= 30
Split Flow Tol= 0.02
Split Flow Ratio= 0.02
Log Output Level= 0
Friction Slope Method= 1
Unsteady Friction Slope Method= 2
Unsteady Bridges Friction Slope Method= 1
Parabolic Critical Depth
Global Vel Dist=  1 , 1 , 1
Global Log Level= 0
CheckData=True
Encroach Param= -1, 0, 0, 0
BEGIN DESCRIPTION:
Multiple Run
END DESCRIPTION:

--- UNT071 IN SUCR.f01 (steady flow) ---

Flow Title=Multiple
Number of Profiles=7
Profile Names=10-year,25-year,50-year,1pct_min,100-year,1pct_plu,500-year
River Rch & RM= UNT071 IN SUCR,Reach-1,9539
     185     253     309     277     375     507     562
River Rch & RM= UNT071 IN SUCR,Reach-1,8512
     323     455     566     518     700     947    1089
Boundary for River Rch & Prof#=UNT071 IN SUCR,Reach-1,1
Up Type=0
Dn Type=3
Dn Slope=0.005
Boundary for River Rch & Prof#=UNT071 IN SUCR,Reach-1,2
Up Type=0
Dn Type=3
Dn Slope=0.005
Boundary for River Rch & Prof#=UNT071 IN SUCR,Reach-1,3
Up Type=0
Dn Type=3
Dn Slope=0.005
Boundary for River Rch & Prof#=UNT071 IN SUCR,Reach-1,4
Up Type=0
Dn Type=3
Dn Slope=0.005
Boundary for River Rch & Prof#=UNT071 IN SUCR,Reach-1,5
Up Type=0
Dn Type=3
Dn Slope=0.005
Boundary for River Rch & Prof#=UNT071 IN SUCR,Reach-1,6
Up Type=0
Dn Type=3
Dn Slope=0.005
Boundary for River Rch & Prof#=UNT071 IN SUCR,Reach-1,7
Up Type=0
Dn Type=3
Dn Slope=0.005

--- UNT071 IN SUCR.g01 (geometry) ---

Geom Title=Existing Conditions

River Reach=UNT071 IN SUCR,Reach-1
Reach XY= 30
      2261422.67     13374037.82      2261777.83     13373677.38
      2262014.94     13373588.92      2262204.25     13373427.45
      2262303.12     13373080.66      2262331.55     13371954.35
      2262488.82     13371919.73      2262631.81     13371734.66
      2263009.23     13371481.30      2263105.88     13371310.73
      2263159.72     13371335.95      2263453.82     13370994.76
      2263789.23     13370912.81      2264449.55     13371047.40
      2264650.44     13370954.80      2264873.00     13370682.86
      2264931.42     13370534.17      2265157.11     13370397.45
      2265263.45     13370254.22      2265295.65     13370002.62
      2265191.53     13369801.79      2265270.15     13369470.37
      2265167.76     13369426.34      2264969.40     13369507.91
      2264828.77     13369476.66      2264306.20     13368905.48
      2264196.83     13368714.50      2264212.45     13368384.64
      2264452.28     13368079.09      2264597.72     13367746.85

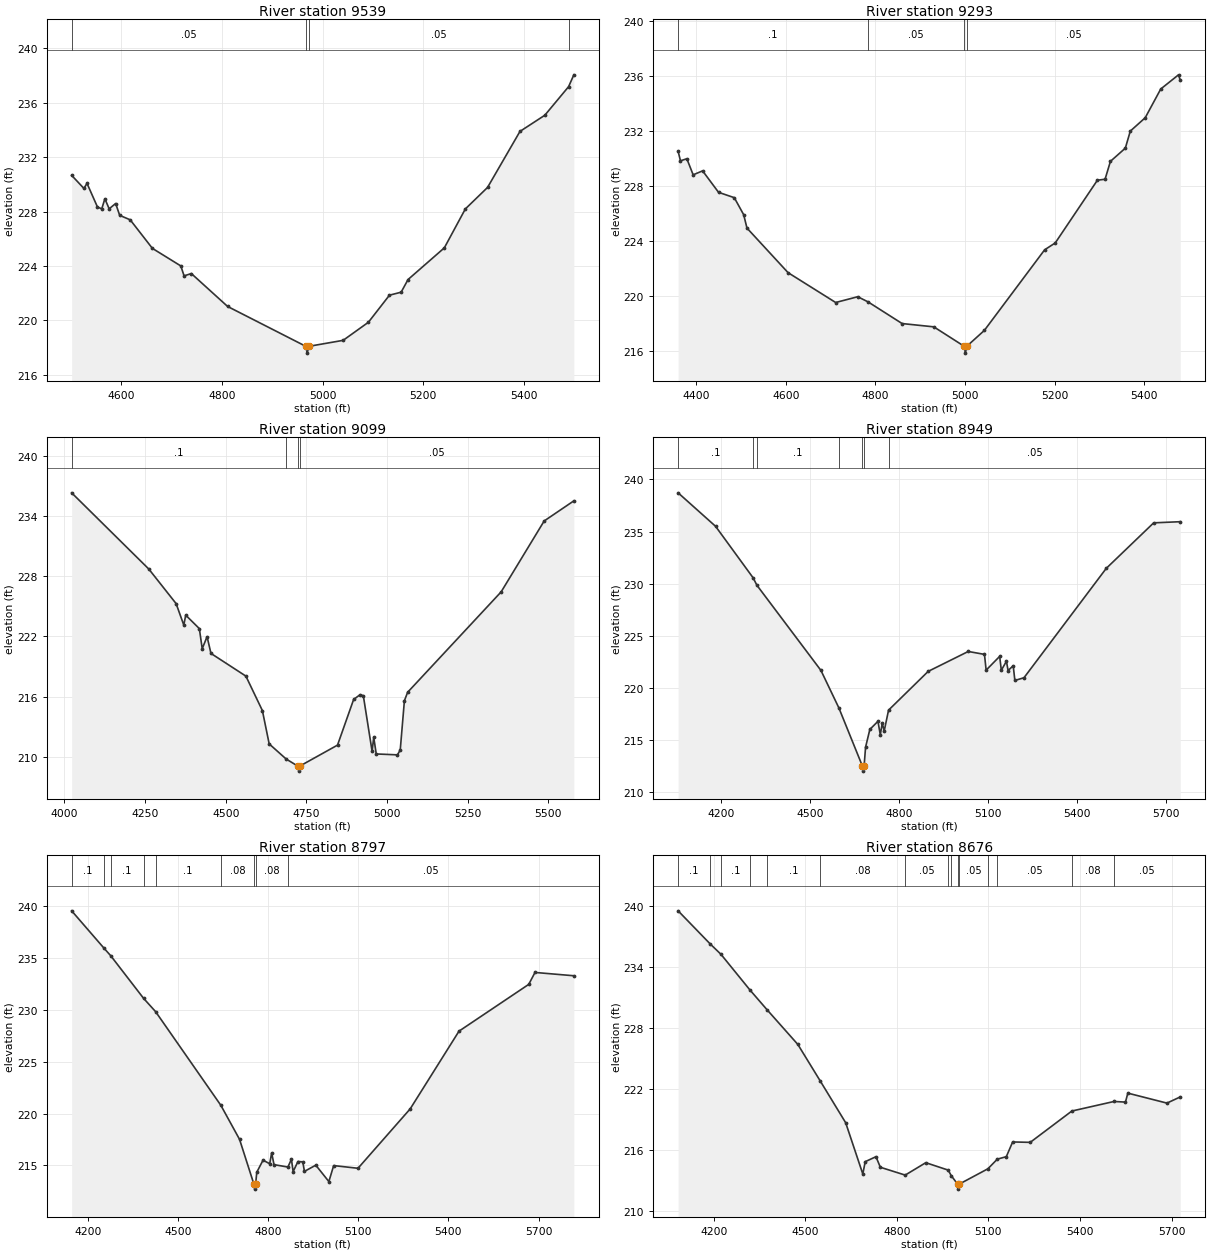
Type RM Length L Ch R = 1,9539,246,246,246
BEGIN DESCRIPTION:
UNT071 IN SUCR 19.0
END DESCRIPTION:
XS GIS Cut Line= 2
      2261899.79     13374267.64      2261314.17     13373460.25
#Sta/Elev= 30
  4501.7  230.67  4526.0  229.71  4532.2  230.08  4553.0  228.34  4561.5  228.21
  4567.7  228.95  4576.2  228.21  4589.1  228.60  4597.1  227.73  4618.0  227.40
  4662.1  225.30  4718.5  224.01  4725.0  223.28  4739.4  223.45  4811.5  221.03
  4966.8  218.10  4969.5  217.60  4972.8  218.10  5040.9  218.54  5091.1  219.87
  5132.9  221.86  5156.1  222.08  5169.8  223.01  5241.9  225.34  5283.6  228.20
  5327.7  229.78  5392.1  233.90  5441.5  235.09  5488.7  237.19  5499.1  238.06
#Mann=4,-1,0
  4501.7    0.05       0  4966.8    0.03       0  4972.8    0.05       0
  5488.7    0.08       0
Bank Sta=4966.8,4972.8
Exp/Cntr=0.3,0.1

Type RM Length L Ch R = 1,9293,194,194,194
BEGIN DESCRIPTION:
Mapping XS ae48030a
END DESCRIPTION:
XS GIS Cut Line= 3
      2262208.86     13374153.10      2261628.98     13373541.98
      2261377.00     13373421.16
#Sta/Elev= 30
  4359.1  230.53  4364.4  229.84  4378.6  229.99  4392.7  228.82  4413.8  229.11
  4449.4  227.55  4484.6  227.16  4505.6  225.92  4512.9  224.95  4604.7  221.71
  4711.1  219.54  4760.4  219.96  4783.7  219.58  4859.5  218.01  4930.3  217.77
  4998.1  216.36  5000.8  215.86  5004.1  216.36  5043.2  217.51  5177.9  223.37
  5201.6  223.87  5295.8  228.43  5312.9  228.50  5324.9  229.80  5358.2  230.76
  5369.3  232.00  5402.6  232.97  5437.3  235.06  5477.0  236.09  5481.0  235.69
#Mann=4,-1,0
  4359.1     0.1       0  4783.7    0.05       0  4998.1    0.03       0
  5004.1    0.05       0
Bank Sta=4998.1,5004.1
Exp/Cntr=0.3,0.1

Type RM Length L Ch R = 1,9099,150,150,150
BEGIN DESCRIPTION:
UNT071 IN SUCR 18.0
END DESCRIPTION:
XS GIS Cut Line= 4
      2262637.74     13374146.89      2262287.74     13373618.16
      2261936.17     13373622.50      2261442.07     13373336.44
#Sta/Elev= 30
  4022.2  236.30  4261.4  228.71  4346.0  225.27  4369.8  223.13  4375.8  224.12
  4418.0  222.78  4426.9  220.78  4442.0  221.98  4454.0  220.31  4562.3  218.05
  4613.4  214.62  4634.5  211.30  4687.3  209.79  4723.3  209.09  4726.1  208.59
  4729.3  209.09  4846.3  211.18  4896.3  215.73  4916.3  216.20  4926.3  216.10
  4953.5  210.56  4958.5  211.97  4966.3  210.30  5032.0  210.21  5040.7  210.69
  5053.6  215.60  5063.6  216.44  5353.5  226.44  5486.9  233.50  5578.8  235.50
#Mann=4,-1,0
  4022.2     0.1       0  4687.3    0.05       0  4723.3    0.03       0
  4729.3    0.05       0
Bank Sta=4723.3,4729.3
Exp/Cntr=0.3,0.1

Type RM Length L Ch R = 1,8949,152,152,152
BEGIN DESCRIPTION:
Mapping XS 2b23ee68
END DESCRIPTION:
XS GIS Cut Line= 4
      2262752.18     13374069.58      2262318.12     13373531.35
      2262083.74     13373548.71      2261391.04     13373224.01
#Sta/Elev= 30
  4056.6  238.72  4182.7  235.51  4309.6  230.55  4321.8  229.86  4537.7  221.68
  4598.0  218.09  4677.1  212.52  4679.8  212.02  4683.1  212.52  4688.0  214.32
  4702.4  216.02  4729.7  216.80  4737.6  215.51  4744.1  216.61  4750.8  215.88
  4765.4  217.87  4898.9  221.59  5033.9  223.50  5088.5  223.22  5094.1  221.71
  5139.7  223.03  5145.2  221.70  5162.5  222.56  5168.0  221.67  5185.3  222.13
  5190.9  220.72  5221.6  220.98  5498.6  231.47  5658.4  235.84  5748.1  235.95
#Mann=7,-1,0
  4056.6     0.1       0  4309.6    0.08       0  4321.8     0.1       0
  4598.0    0.08       0  4677.1    0.03       0  4683.1    0.08       0
  4765.4    0.05       0
Bank Sta=4677.1,4683.1
Exp/Cntr=0.3,0.1

Type RM Length L Ch R = 1,8797,121,121,121
BEGIN DESCRIPTION:
Mapping XS 698524d4
END DESCRIPTION:
XS GIS Cut Line= 4
      2262763.42     13374058.25      2262322.46     13373520.07
      2261930.10     13373301.32      2261423.19     13373158.97
#Sta/Elev= 30
  4145.9  239.55  4254.4  235.92  4275.7  235.23  4385.1  231.12  4425.3  229.83
  4642.5  220.80  4704.7  217.52  4752.3  213.22  4755.1  212.72  4758.3  213.22
  4762.1  214.35  4782.9  215.51  4805.1  215.17  4811.6  216.21  4819.5  215.08
  4865.7  214.85  4877.4  215.60  4883.1  214.41  4899.1  215.38  4915.1  215.35
  4920.8  214.43  4958.5  215.03  5002.0  213.45  5018.0  214.99  5099.0  214.73
  5272.8  220.46  5435.2  227.95  5667.3  232.46  5688.1  233.61  5817.4  233.29
#Mann=9,-1,0
  4145.9     0.1       0  4254.4    0.08       0  4275.7     0.1       0
  4385.1    0.08       0  4425.3     0.1       0  4642.5    0.08       0
  4752.3    0.03       0  4758.3    0.08       0  4865.7    0.05       0
Bank Sta=4752.3,4758.3
Exp/Cntr=0.3,0.1

Type RM Length L Ch R = 1,8676,164,164,164
BEGIN DESCRIPTION:
Mapping XS dc02b65a
END DESCRIPTION:
XS GIS Cut Line= 2
      2262769.49     13374056.51      2261736.52     13372776.14
#Sta/Elev= 30
  4083.6  239.55  4188.8  236.29  4223.8  235.28  4318.8  231.77  4374.7  229.83
  4475.8  226.41  4548.3  222.86  4632.5  218.71  4688.6  213.67  4696.5  214.88
  4731.7  215.37  4746.1  214.33  4827.5  213.56  4894.9  214.78  4968.4  214.05
  4978.4  213.50  4999.0  212.68  5001.7  212.18  5005.0  212.68  5098.4  214.18
  5129.3  215.13  5158.7  215.37  5179.5  216.82  5237.1  216.78  5373.4  219.86
  5511.5  220.80  5549.0  220.74  5556.9  221.62  5684.9  220.64  5728.7  221.25
#Mann=15,-1,0
  4083.6     0.1       0  4188.8    0.08       0  4223.8     0.1       0
  4318.8    0.08       0  4374.7     0.1       0  4548.3    0.08       0
  4827.5    0.05       0  4968.4    0.08       0  4978.4    0.05       0
  4999.0    0.03       0  5005.0    0.05       0  5098.4    0.08       0
  5129.3    0.05       0  5373.4    0.08       0  5511.5    0.05       0
Bank Sta=4999,5005
Exp/Cntr=0.3,0.1

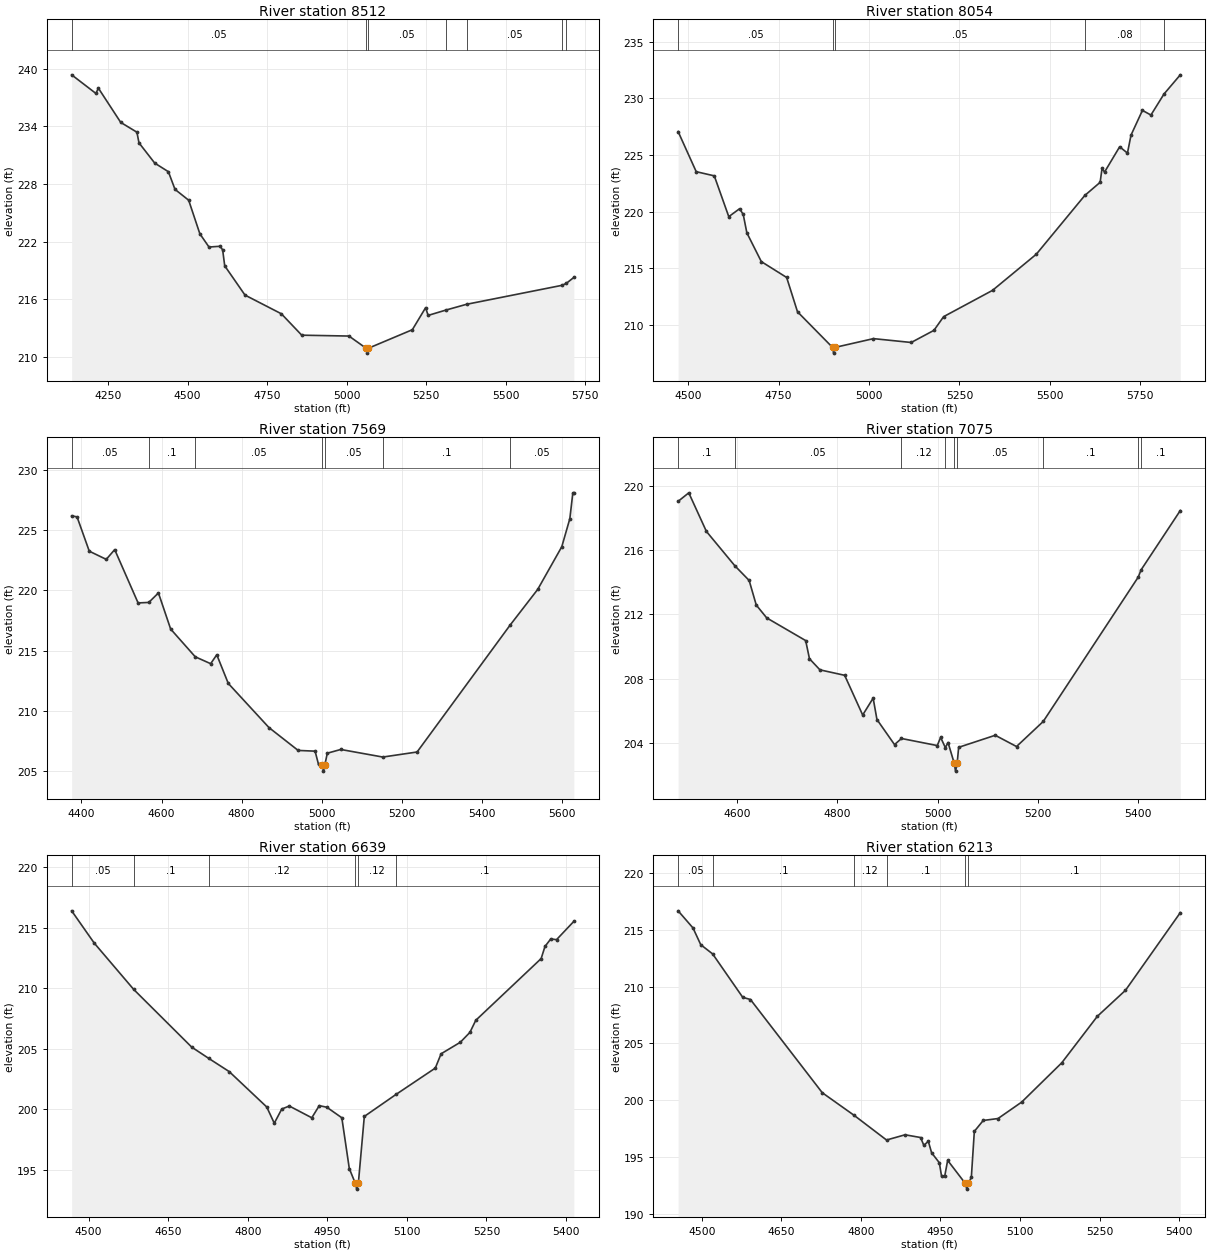
Type RM Length L Ch R = 1,8512,458,458,458
BEGIN DESCRIPTION:
UNT071 IN SUCR 17.0
END DESCRIPTION:
XS GIS Cut Line= 2
      2262817.25     13373865.55      2261811.50     13372647.38
#Sta/Elev= 30
  4135.0  239.38  4211.3  237.44  4219.1  237.99  4289.4  234.42  4340.3  233.40
  4346.8  232.29  4396.3  230.18  4439.3  229.28  4460.1  227.44  4503.1  226.31
  4538.3  222.81  4567.0  221.43  4602.1  221.51  4610.0  221.13  4616.5  219.47
  4680.3  216.42  4794.7  214.47  4858.8  212.24  5007.3  212.15  5061.7  210.87
  5064.4  210.37  5067.7  210.87  5206.7  212.81  5248.5  215.11  5256.2  214.30
  5311.4  214.85  5377.2  215.46  5677.8  217.44  5691.3  217.65  5714.7  218.26
#Mann=7,-1,0
  4135.0    0.05       0  5061.7    0.03       0  5067.7    0.05       0
  5311.4    0.08       0  5377.2    0.05       0  5677.8    0.08       0
  5691.3    0.05       0
Bank Sta=5061.7,5067.7
Exp/Cntr=0.3,0.1

Type RM Length L Ch R = 1,8054,485,485,485
BEGIN DESCRIPTION:
UNT071 IN SUCR 16.0
END DESCRIPTION:
XS GIS Cut Line= 3
      2262837.70     13372746.85      2262287.72     13372746.85
      2261487.75     13372496.87
#Sta/Elev= 30
  4472.5  227.06  4522.5  223.52  4572.5  223.15  4612.5  219.55  4642.5  220.25
  4652.5  219.74  4662.5  218.12  4702.5  215.58  4772.5  214.18  4802.5  211.15
  4899.5  208.00  4902.2  207.50  4905.5  208.00  5012.5  208.78  5116.8  208.44
  5179.6  209.51  5206.4  210.72  5341.5  213.04  5462.5  216.23  5596.6  221.42
  5639.0  222.58  5644.3  223.82  5651.1  223.48  5693.0  225.72  5714.5  225.16
  5724.4  226.75  5755.9  228.93  5779.4  228.52  5815.6  230.38  5860.6  232.07
#Mann=5,-1,0
  4472.5    0.05       0  4899.5   0.035       0  4905.5    0.05       0
  5596.6    0.08       0  5815.6    0.05       0
Bank Sta=4899.5,4905.5
Exp/Cntr=0.3,0.1

Type RM Length L Ch R = 1,7569,494,494,494
BEGIN DESCRIPTION:
UNT071 IN SUCR 15.0
END DESCRIPTION:
XS GIS Cut Line= 3
      2262837.72     13372596.85      2262287.72     13372246.85
      2261687.72     13372296.86
#Sta/Elev= 30
  4375.6  226.20  4389.1  226.11  4419.6  223.26  4462.0  222.58  4483.1  223.39
  4541.5  218.96  4568.2  219.00  4592.3  219.79  4622.8  216.79  4684.3  214.48
  4722.7  213.91  4738.0  214.65  4766.7  212.27  4868.3  208.60  4941.2  206.70
  4983.5  206.64  4992.0  205.54  5001.7  205.48  5004.4  204.98  5007.7  205.48
  5014.0  206.47  5047.6  206.78  5152.6  206.15  5238.2  206.57  5470.1  217.10
  5539.3  220.08  5599.5  223.63  5619.6  225.96  5627.1  228.11  5629.6  228.11
#Mann=7,-1,0
  4375.6    0.05       0  4568.2     0.1       0  4684.3    0.05       0
  5001.7    0.03       0  5007.7    0.05       0  5152.6     0.1       0
  5470.1    0.05       0
Bank Sta=5001.7,5007.7
Exp/Cntr=0.3,0.1

Type RM Length L Ch R = 1,7075,436,436,436
BEGIN DESCRIPTION:
UNT071 IN SUCR 14.0
END DESCRIPTION:
XS GIS Cut Line= 3
      2262837.71     13372296.84      2262487.72     13371896.85
      2262087.71     13371646.85
#Sta/Elev= 30
  4481.8  219.03  4503.1  219.56  4538.3  217.16  4595.2  215.02  4623.7  214.11
  4637.9  212.58  4658.8  211.78  4736.6  210.37  4744.2  209.24  4765.1  208.55
  4814.5  208.21  4850.5  205.74  4871.4  206.79  4879.0  205.46  4914.1  203.90
  4928.0  204.28  4999.5  203.84  5006.2  204.35  5015.6  203.71  5021.0  204.03
  5033.3  202.75  5036.0  202.25  5039.3  202.75  5042.2  203.73  5115.3  204.48
  5157.8  203.78  5211.2  205.34  5401.0  214.32  5406.7  214.77  5485.0  218.46
#Mann=9,-1,0
  4481.8     0.1       0  4595.2    0.05       0  4928.0    0.12       0
  5015.6    0.05       0  5033.3    0.07       0  5039.3    0.05       0
  5211.2     0.1       0  5401.0    0.05       0  5406.7     0.1       0
Bank Sta=5033.3,5039.3
Exp/Cntr=0.3,0.1

Type RM Length L Ch R = 1,6639,426,426,426
BEGIN DESCRIPTION:
UNT071 IN SUCR 13.0
END DESCRIPTION:
XS GIS Cut Line= 3
      2263187.75     13371996.88      2262787.72     13371596.85
      2262637.72     13371246.87
#Sta/Elev= 30
  4468.2  216.38  4510.7  213.72  4585.2  209.89  4694.5  205.13  4726.6  204.20
  4765.2  203.11  4835.9  200.19  4850.1  198.85  4864.2  200.02  4878.4  200.27
  4920.8  199.30  4934.9  200.30  4949.1  200.17  4977.4  199.30  4991.5  195.11
  5002.6  193.91  5005.4  193.41  5008.6  193.91  5019.8  199.41  5079.7  201.23
  5153.6  203.40  5164.5  204.58  5200.7  205.53  5218.9  206.35  5229.8  207.34
  5353.1  212.44  5360.3  213.44  5371.2  214.06  5382.1  214.00  5414.7  215.51
#Mann=6,-1,0
  4468.2    0.05       0  4585.2     0.1       0  4726.6    0.12       0
  5002.6    0.07       0  5008.6    0.12       0  5079.7     0.1       0
Bank Sta=5002.6,5008.6
Exp/Cntr=0.3,0.1

Type RM Length L Ch R = 1,6213,461,461,461
BEGIN DESCRIPTION:
UNT071 IN SUCR 12.0
END DESCRIPTION:
XS GIS Cut Line= 3
      2263437.71     13371746.85      2263137.72     13371346.85
      2262737.72     13371146.86
#Sta/Elev= 30
  4455.2  216.67  4483.3  215.16  4497.9  213.69  4520.3  212.88  4577.1  209.06
  4591.6  208.87  4727.1  200.67  4787.2  198.68  4848.3  196.51  4883.3  196.97
  4912.5  196.73  4918.7  196.04  4927.1  196.40  4933.3  195.39  4947.9  194.51
  4952.1  193.32  4958.0  193.32  4963.6  194.72  4996.9  192.69  4999.7  192.19
  5002.9  192.69  5008.3  193.25  5013.9  197.27  5030.7  198.23  5058.6  198.40
  5103.3  199.85  5178.8  203.30  5245.9  207.39  5299.0  209.68  5402.4  216.51
#Mann=6,-1,0
  4455.2    0.05       0  4520.3     0.1       0  4787.2    0.12       0
  4848.3     0.1       0  4996.9    0.07       0  5002.9     0.1       0
Bank Sta=4996.9,5002.9
Exp/Cntr=0.3,0.1

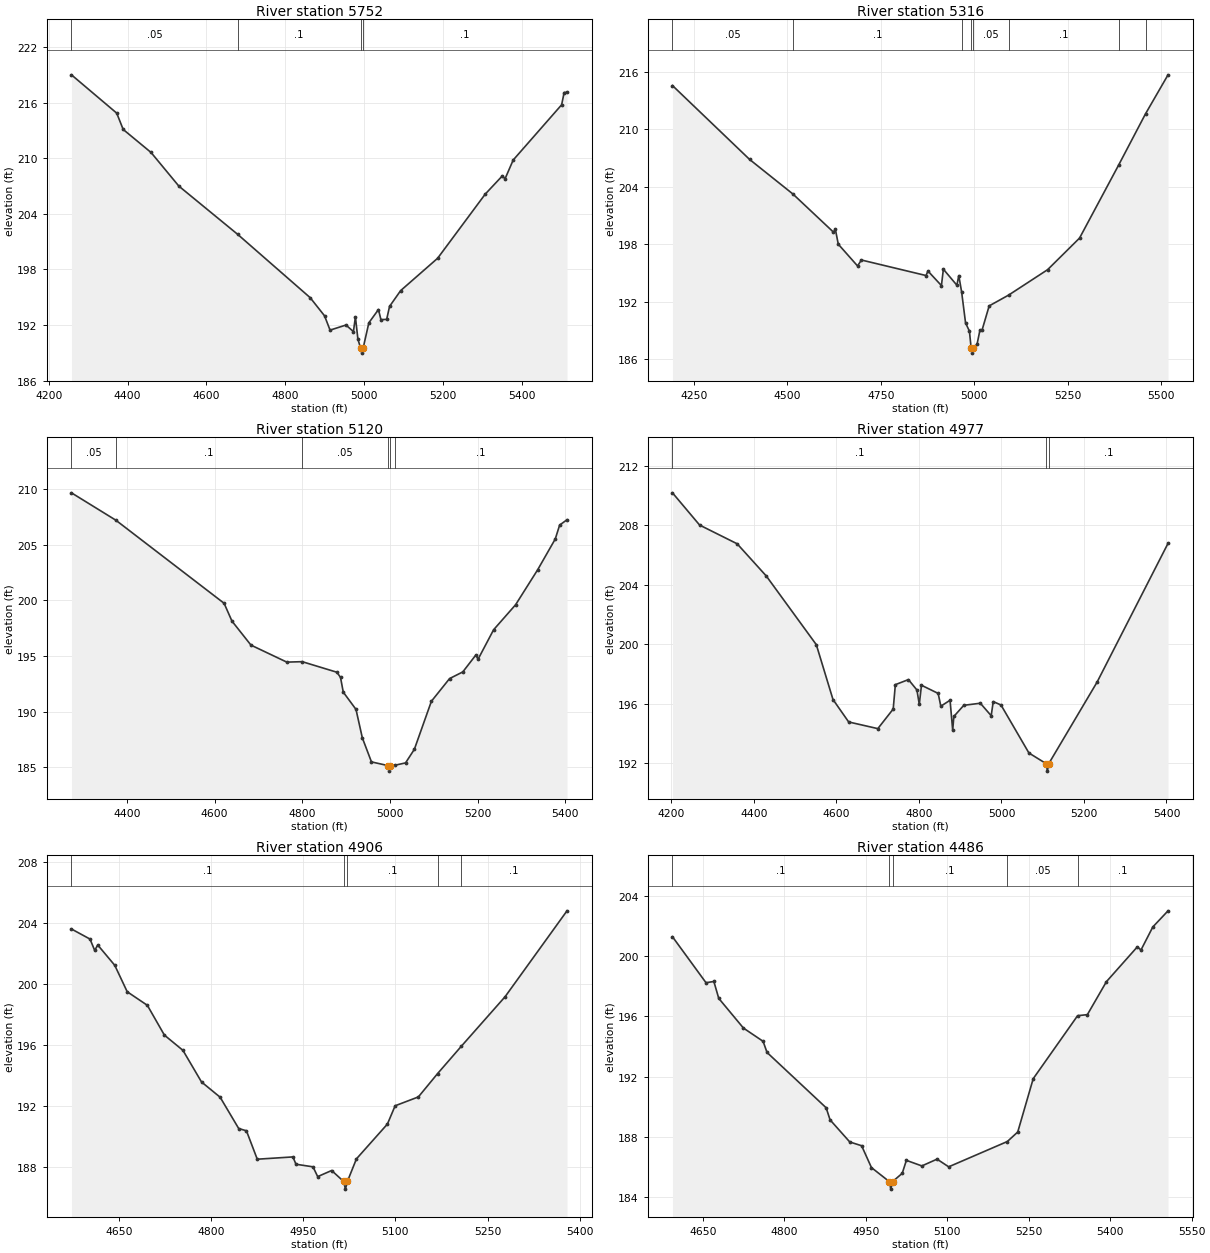
Type RM Length L Ch R = 1,5752,436,436,436
BEGIN DESCRIPTION:
UNT071 IN SUCR 11.0
END DESCRIPTION:
XS GIS Cut Line= 3
      2263487.73     13371796.90      2263387.72     13371046.85
      2262987.71     13370746.85
#Sta/Elev= 30
  4257.8  218.99  4372.6  214.86  4389.0  213.10  4459.6  210.62  4530.2  206.99
  4679.3  201.79  4863.2  194.96  4899.7  193.00  4913.6  191.46  4954.0  192.01
  4972.9  191.30  4977.9  192.89  4984.2  190.50  4991.3  189.48  4994.1  188.98
  4997.3  189.48  5012.0  192.25  5036.4  193.68  5042.6  192.59  5057.2  192.62
  5064.5  194.02  5092.6  195.72  5186.4  199.21  5307.2  206.13  5350.9  208.11
  5357.2  207.76  5378.0  209.80  5500.9  215.76  5507.2  217.08  5514.5  217.11
#Mann=4,-1,0
  4257.8    0.05       0  4679.3     0.1       0  4991.3    0.07       0
  4997.3     0.1       0
Bank Sta=4991.3,4997.3
Exp/Cntr=0.3,0.1

Type RM Length L Ch R = 1,5316,196,196,196
BEGIN DESCRIPTION:
UNT071 IN SUCR 10.0
END DESCRIPTION:
XS GIS Cut Line= 3
      2263587.73     13371696.82      2263787.72     13370896.85
      2263487.71     13370496.84
#Sta/Elev= 30
  4193.4  214.57  4399.5  206.86  4515.3  203.25  4623.7  199.27  4628.9  199.55
  4636.6  198.01  4688.1  195.74  4698.4  196.36  4871.1  194.74  4876.3  195.21
  4912.3  193.69  4917.5  195.40  4953.6  193.73  4958.7  194.73  4966.3  193.03
  4976.8  189.79  4987.1  188.94  4991.8  187.14  4994.5  186.64  4997.8  187.14
  5007.7  187.60  5015.4  189.07  5021.1  189.07  5039.9  191.57  5092.0  192.70
  5196.1  195.35  5281.5  198.65  5386.5  206.31  5457.8  211.62  5518.0  215.69
#Mann=8,-1,0
  4193.4    0.05       0  4515.3     0.1       0  4966.3    0.05       0
  4991.8   0.035       0  4997.8    0.05       0  5092.0     0.1       0
  5386.5    0.08       0  5457.8     0.1       0
Bank Sta=4991.8,4997.8
Exp/Cntr=0.3,0.1

Type RM Length L Ch R = 1,5120,143,143,143
BEGIN DESCRIPTION:
Mapping XS d77940e0
END DESCRIPTION:
XS GIS Cut Line= 4
      2263776.44     13371647.71      2263889.30     13371113.82
      2263976.11     13371000.97      2263932.89     13370560.14
#Sta/Elev= 30
  4273.1  209.67  4374.4  207.21  4621.5  199.74  4639.4  198.14  4682.8  195.98
  4764.6  194.45  4799.7  194.49  4879.0  193.54  4887.2  193.07  4893.5  191.75
  4922.5  190.20  4937.0  187.64  4957.8  185.48  4995.2  185.15  4997.9  184.65
  5001.2  185.15  5011.5  185.18  5035.6  185.39  5055.7  186.61  5094.6  190.93
  5136.1  192.97  5166.3  193.57  5196.1  195.09  5201.1  194.71  5236.6  197.36
  5286.8  199.61  5337.1  202.75  5377.3  205.52  5387.3  206.77  5404.1  207.25
#Mann=6,-1,0
  4273.1    0.05       0  4374.4     0.1       0  4799.7    0.05       0
  4995.2   0.035       0  5001.2    0.05       0  5011.5     0.1       0
Bank Sta=4995.2,5001.2
Exp/Cntr=0.3,0.1

Type RM Length L Ch R = 1,4977,71,71,71
BEGIN DESCRIPTION:
Mapping XS 570e18d2
END DESCRIPTION:
XS GIS Cut Line= 6
      2263871.93     13371652.04      2263941.38     13371165.90
      2264071.59     13371122.50      2264106.31     13371079.10
      2264119.33     13370896.80      2264062.91     13370566.96
#Sta/Elev= 30
  4202.5  210.18  4268.3  208.01  4359.3  206.75  4430.0  204.58  4551.2  199.96
  4591.6  196.27  4629.6  194.76  4700.3  194.31  4737.6  195.63  4742.8  197.27
  4774.5  197.61  4795.1  196.91  4800.8  195.94  4806.1  197.23  4846.6  196.68
  4853.0  195.82  4875.4  196.22  4881.8  194.20  4884.6  195.13  4908.7  195.88
  4948.8  196.02  4975.1  195.18  4980.1  196.13  4998.9  195.90  5066.6  192.67
  5108.6  191.95  5111.3  191.45  5114.6  191.95  5231.8  197.44  5403.8  206.78
#Mann=3,-1,0
  4202.5     0.1       0  5108.6    0.07       0  5114.6     0.1       0
Bank Sta=5108.6,5114.6
Exp/Cntr=0.3,0.1

Type RM Length L Ch R = 1,4906,420,420,420
BEGIN DESCRIPTION:
UNT071 IN SUCR 9.0
END DESCRIPTION:
XS GIS Cut Line= 3
      2264137.72     13371396.85      2264187.72     13370996.85
      2264137.72     13370596.88
#Sta/Elev= 30
  4573.1  203.61  4603.3  202.95  4610.9  202.21  4615.9  202.56  4643.6  201.23
  4663.8  199.50  4696.6  198.61  4724.3  196.66  4754.5  195.66  4784.7  193.59
  4815.0  192.59  4845.2  190.54  4857.8  190.39  4875.4  188.53  4933.4  188.68
  4938.4  188.20  4966.1  188.03  4973.7  187.39  4996.4  187.79  5016.0  187.07
  5018.8  186.57  5022.0  187.07  5036.7  188.55  5087.1  190.83  5099.7  192.03
  5137.5  192.61  5168.8  194.14  5207.4  195.93  5278.5  199.17  5379.3  204.80
#Mann=5,-1,0
  4573.1     0.1       0  5016.0    0.07       0  5022.0     0.1       0
  5168.8    0.05       0  5207.4     0.1       0
Bank Sta=5016,5022
Exp/Cntr=0.3,0.1

Type RM Length L Ch R = 1,4486,456,456,456
BEGIN DESCRIPTION:
UNT071 IN SUCR 8.0
END DESCRIPTION:
XS GIS Cut Line= 3
      2264737.73     13371346.87      2264587.72     13370996.85
      2264237.73     13370596.86
#Sta/Elev= 30
  4594.2  201.29  4655.9  198.24  4670.4  198.32  4679.4  197.20  4724.8  195.23
  4761.0  194.35  4768.3  193.61  4877.1  189.94  4884.3  189.14  4920.6  187.67
  4942.4  187.42  4960.5  185.97  4993.4  185.04  4996.1  184.54  4999.4  185.04
  5017.2  185.59  5024.8  186.45  5053.3  186.08  5081.3  186.53  5102.7  186.02
  5210.7  187.70  5229.8  188.33  5258.3  191.87  5340.0  196.05  5358.0  196.12
  5393.1  198.31  5450.0  200.62  5456.7  200.41  5478.5  201.94  5506.5  203.01
#Mann=5,-1,0
  4594.2     0.1       0  4993.4    0.07       0  4999.4     0.1       0
  5210.7    0.05       0  5340.0     0.1       0
Bank Sta=4993.4,4999.4
Exp/Cntr=0.3,0.1

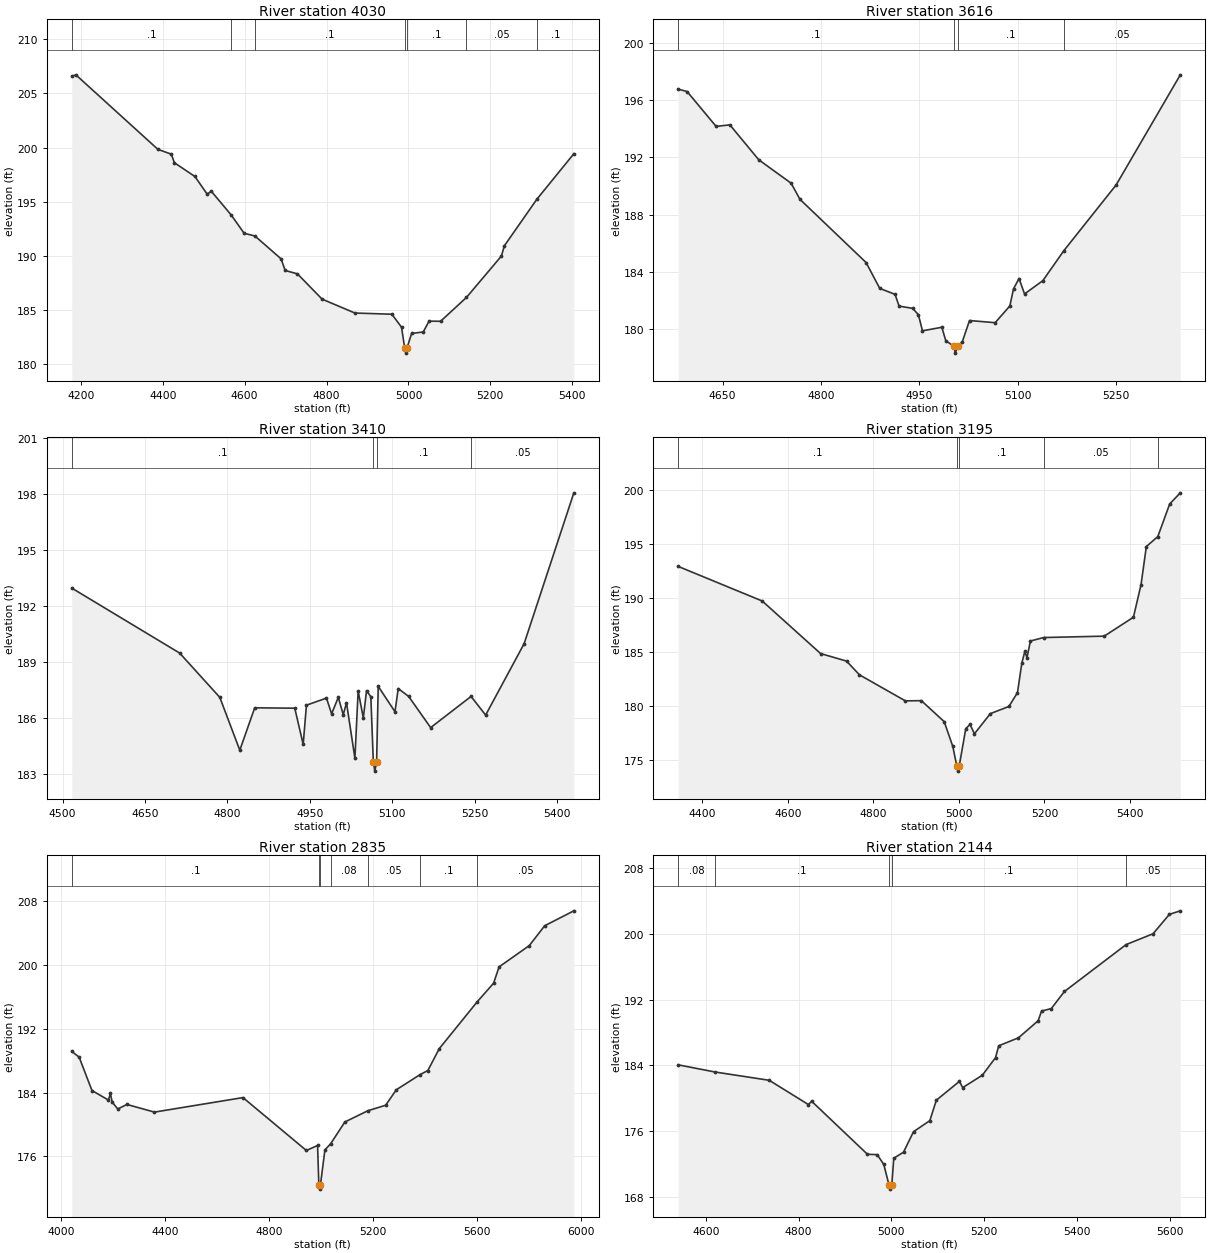
Type RM Length L Ch R = 1,4030,414,414,414
BEGIN DESCRIPTION:
UNT071 IN SUCR 7.0
END DESCRIPTION:
XS GIS Cut Line= 3
      2264937.72     13371496.83      2264887.72     13370696.85
      2264587.72     13370396.86
#Sta/Elev= 30
  4178.0  206.57  4188.0  206.71  4388.4  199.83  4421.0  199.39  4428.5  198.60
  4478.6  197.33  4508.6  195.70  4518.6  195.97  4567.2  193.78  4598.8  192.09
  4625.2  191.84  4689.0  189.73  4699.0  188.66  4729.1  188.34  4789.2  186.01
  4869.3  184.73  4959.5  184.62  4983.1  183.42  4990.7  181.53  4993.4  181.03
  4996.7  181.53  5007.8  182.85  5036.1  182.98  5050.3  183.98  5078.5  183.97
  5141.6  186.17  5227.0  189.99  5234.1  190.93  5313.7  195.24  5403.8  199.43
#Mann=7,-1,0
  4178.0     0.1       0  4567.2    0.05       0  4625.2     0.1       0
  4990.7    0.07       0  4996.7     0.1       0  5141.6    0.05       0
  5313.7     0.1       0
Bank Sta=4990.7,4996.7
Exp/Cntr=0.3,0.1

Type RM Length L Ch R = 1,3616,206,206,206
BEGIN DESCRIPTION:
UNT071 IN SUCR 6.0
END DESCRIPTION:
XS GIS Cut Line= 3
      2265487.74     13370646.87      2265137.72     13370396.85
      2264837.76     13370246.88
#Sta/Elev= 30
  4582.4  196.78  4595.9  196.61  4640.2  194.17  4661.1  194.28  4705.3  191.83
  4754.5  190.20  4768.0  189.07  4868.8  184.65  4889.6  182.84  4913.0  182.42
  4919.1  181.60  4940.0  181.44  4948.6  180.99  4954.8  179.87  4984.3  180.12
  4990.4  179.17  5002.2  178.81  5004.9  178.31  5008.2  178.81  5015.3  179.08
  5026.5  180.59  5065.6  180.44  5088.0  181.61  5093.6  182.81  5102.0  183.53
  5110.4  182.45  5138.3  183.38  5170.2  185.47  5250.1  190.08  5347.9  197.78
#Mann=4,-1,0
  4582.4     0.1       0  5002.2    0.07       0  5008.2     0.1       0
  5170.2    0.05       0
Bank Sta=5002.2,5008.2
Exp/Cntr=0.3,0.1

Type RM Length L Ch R = 1,3410,215,215,215
BEGIN DESCRIPTION:
Mapping XS 9acb7b10
END DESCRIPTION:
XS GIS Cut Line= 3
      2265677.53     13370497.52      2265169.68     13370176.32
      2264857.19     13370176.32
#Sta/Elev= 30
  4516.8  192.95  4713.1  189.47  4786.1  187.10  4822.5  184.27  4849.6  186.54
  4922.5  186.52  4937.8  184.58  4943.7  186.68  4980.2  187.06  4989.5  186.22
  5001.7  187.10  5010.7  186.17  5016.6  186.81  5031.9  183.84  5037.8  187.44
  5047.2  186.00  5053.1  187.46  5060.9  187.13  5065.4  183.65  5068.1  183.15
  5071.4  183.65  5074.3  187.69  5104.8  186.33  5110.7  187.57  5129.7  187.15
  5169.7  185.48  5243.2  187.15  5269.7  186.15  5339.7  189.97  5430.2  198.05
#Mann=4,-1,0
  4516.8     0.1       0  5065.4    0.07       0  5071.4     0.1       0
  5243.2    0.05       0
Bank Sta=5065.4,5071.4
Exp/Cntr=0.3,0.1

Type RM Length L Ch R = 1,3195,360,360,360
BEGIN DESCRIPTION:
UNT071 IN SUCR 5.0
END DESCRIPTION:
XS GIS Cut Line= 4
      2265903.20     13370254.45      2265482.18     13370054.79
      2265100.24     13370007.05      2264805.06     13370137.27
#Sta/Elev= 30
  4344.1  192.91  4540.4  189.71  4676.8  184.85  4737.5  184.15  4767.7  182.88
  4875.0  180.47  4912.3  180.49  4965.7  178.55  4985.9  176.25  4995.0  174.47
  4997.7  173.97  5001.0  174.47  5016.1  177.89  5026.2  178.30  5036.3  177.42
  5073.6  179.29  5116.9  179.95  5137.0  181.23  5147.1  183.95  5154.2  185.05
  5159.2  184.47  5167.3  186.01  5198.0  186.33  5339.8  186.46  5408.0  188.21
  5425.8  191.22  5438.2  194.75  5465.0  195.67  5492.8  198.69  5517.6  199.72
#Mann=5,-1,0
  4344.1     0.1       0  4995.0    0.07       0  5001.0     0.1       0
  5198.0    0.05       0  5465.0     0.1       0
Bank Sta=4995,5001
Exp/Cntr=0.3,0.1

Type RM Length L Ch R = 1,2835,691,691,691
BEGIN DESCRIPTION:
Mapping XS 5f77af34
END DESCRIPTION:
XS GIS Cut Line= 4
      2266020.24     13370104.31      2265542.22     13369658.16
      2264825.18     13369793.60      2264363.10     13370088.37
#Sta/Elev= 30
  4039.8  189.16  4068.2  188.43  4117.6  184.25  4181.1  183.06  4188.4  183.90
  4195.3  182.80  4216.8  181.94  4251.9  182.51  4357.9  181.55  4698.5  183.37
  4942.5  176.74  4985.6  177.37  4990.4  172.40  4993.1  171.90  4996.4  172.40
  5013.7  176.81  5035.7  177.58  5090.4  180.31  5178.8  181.72  5247.5  182.41
  5288.5  184.35  5379.9  186.25  5409.8  186.76  5453.7  189.50  5599.9  195.38
  5662.7  197.70  5683.9  199.75  5800.0  202.41  5859.3  204.90  5971.5  206.77
#Mann=7,-1,0
  4039.8     0.1       0  4990.4    0.07       0  4996.4     0.1       0
  5035.7    0.08       0  5178.8    0.05       0  5379.9     0.1       0
  5599.9    0.05       0
Bank Sta=4990.4,4996.4
Exp/Cntr=0.3,0.1

Type RM Length L Ch R = 1,2144,344,344,344
BEGIN DESCRIPTION:
Mapping XS e1196619
END DESCRIPTION:
XS GIS Cut Line= 3
      2265247.47     13369251.82      2265000.45     13369347.44
      2264442.78     13369944.94
#Sta/Elev= 30
  4540.6  184.06  4619.8  183.19  4736.7  182.18  4821.0  179.23  4828.3  179.62
  4948.5  173.17  4969.5  173.13  4983.7  171.93  4994.9  169.43  4997.6  168.93
  5000.9  169.43  5005.2  172.69  5026.2  173.43  5047.7  175.92  5082.9  177.27
  5097.0  179.76  5146.7  182.05  5153.7  181.29  5196.2  182.80  5224.5  184.94
  5231.4  186.38  5273.9  187.35  5316.4  189.43  5323.7  190.61  5344.7  190.91
  5373.0  192.99  5506.0  198.70  5564.1  200.02  5599.2  202.38  5622.8  202.81
#Mann=5,-1,0
  4540.6    0.08       0  4619.8     0.1       0  4994.9    0.07       0
  5000.9     0.1       0  5506.0    0.05       0
Bank Sta=4994.9,5000.9
Exp/Cntr=0.3,0.1

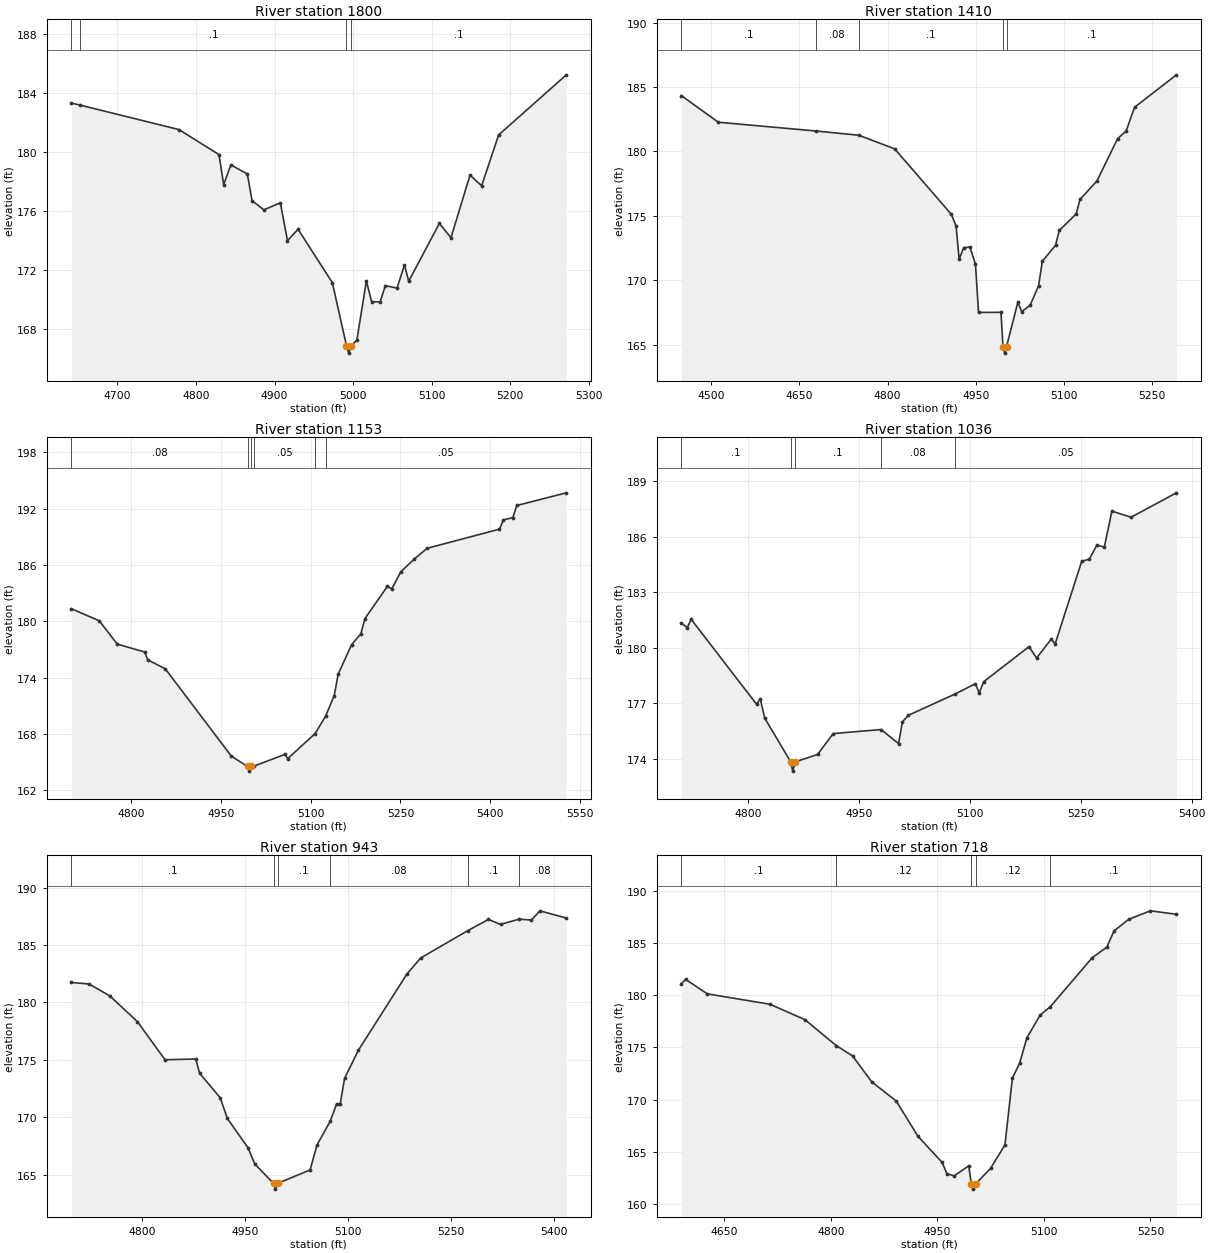
Type RM Length L Ch R = 1,1800,390,390,390
BEGIN DESCRIPTION:
UNT071 IN SUCR 4.0
END DESCRIPTION:
XS GIS Cut Line= 3
      2264937.75     13369046.83      2264637.72     13369246.85
      2264537.70     13369496.90
#Sta/Elev= 30
  4641.5  183.33  4652.7  183.19  4778.2  181.53  4829.3  179.83  4835.3  177.78
  4844.4  179.13  4865.4  178.51  4871.4  176.70  4886.4  176.07  4907.4  176.55
  4916.5  173.98  4930.0  174.75  4973.6  171.12  4991.6  166.83  4994.3  166.33
  4997.6  166.83  5004.8  167.21  5016.9  171.24  5023.6  169.83  5034.4  169.81
  5041.1  170.92  5055.9  170.75  5065.4  172.32  5070.8  171.22  5109.8  175.15
  5124.6  174.18  5148.8  178.43  5163.6  177.71  5185.2  181.16  5271.4  185.25
#Mann=4,-1,0
  4641.5    0.08       0  4652.7     0.1       0  4991.6    0.07       0
  4997.6     0.1       0
Bank Sta=4991.6,4997.6
Exp/Cntr=0.3,0.1

Type RM Length L Ch R = 1,1410,257,257,257
BEGIN DESCRIPTION:
UNT071 IN SUCR 3.0
END DESCRIPTION:
XS GIS Cut Line= 3
      2264887.68     13368796.87      2264387.72     13368946.85
      2264187.74     13369196.84
#Sta/Elev= 30
  4449.4  184.33  4512.0  182.27  4677.8  181.59  4751.1  181.26  4812.2  180.20
  4908.7  175.11  4916.6  174.21  4921.8  171.65  4929.6  172.52  4940.0  172.58
  4949.6  171.26  4954.8  167.50  4993.0  167.51  4996.4  164.84  4999.1  164.34
  5002.4  164.84  5021.8  168.31  5028.2  167.55  5042.6  168.06  5057.0  169.57
  5063.4  171.48  5085.8  172.71  5092.2  173.87  5121.0  175.15  5127.4  176.27
  5156.3  177.71  5191.5  181.00  5205.9  181.58  5220.3  183.43  5291.5  185.95
#Mann=5,-1,0
  4449.4     0.1       0  4677.8    0.08       0  4751.1     0.1       0
  4996.4    0.07       0  5002.4     0.1       0
Bank Sta=4996.4,5002.4
Exp/Cntr=0.3,0.1

Type RM Length L Ch R = 1,1153,117,117,117
BEGIN DESCRIPTION:
Mapping XS 4d426e24
END DESCRIPTION:
XS GIS Cut Line= 3
      2264514.13     13368792.24      2264144.36     13368761.00
      2263738.15     13368969.31
#Sta/Elev= 30
  4699.9  181.33  4746.5  180.05  4776.6  177.56  4822.5  176.72  4827.5  175.89
  4856.9  174.93  4967.3  165.63  4994.4  164.53  4997.1  164.03  5000.4  164.53
  5004.6  164.55  5056.7  165.81  5061.7  165.37  5107.4  168.03  5124.9  169.88
  5139.4  172.08  5145.9  174.35  5168.4  177.50  5183.8  178.65  5190.8  180.29
  5228.2  183.71  5235.8  183.47  5250.4  185.24  5272.6  186.60  5294.8  187.77
  5415.6  189.81  5422.4  190.80  5438.1  191.04  5444.6  192.33  5527.5  193.68
#Mann=6,-1,0
  4699.9    0.08       0  4994.4    0.07       0  5000.4    0.08       0
  5004.6    0.05       0  5107.4     0.1       0  5124.9    0.05       0
Bank Sta=4994.4,5000.4
Exp/Cntr=0.3,0.1

Type RM Length L Ch R = 1,1036,93,93,93
BEGIN DESCRIPTION:
Mapping XS 33e9f775
END DESCRIPTION:
XS GIS Cut Line= 3
      2264477.71     13368714.12      2264139.15     13368641.20
      2263822.05     13368703.58
#Sta/Elev= 30
  4709.9  181.32  4717.8  181.08  4723.0  181.53  4811.4  176.94  4816.5  177.23
  4822.4  176.19  4857.7  173.82  4860.4  173.32  4863.7  173.82  4894.0  174.22
  4915.1  175.35  4979.9  175.57  5003.5  174.81  5008.7  175.98  5016.8  176.34
  5080.0  177.49  5107.5  178.05  5112.6  177.55  5118.8  178.16  5180.0  180.05
  5190.2  179.44  5210.2  180.46  5215.3  180.19  5251.3  184.67  5261.5  184.78
  5271.8  185.54  5281.9  185.44  5292.1  187.38  5318.1  187.05  5379.4  188.37
#Mann=5,-1,0
  4709.9     0.1       0  4857.7    0.07       0  4863.7     0.1       0
  4979.9    0.08       0  5080.0    0.05       0
Bank Sta=4857.7,4863.7
Exp/Cntr=0.3,0.1

Type RM Length L Ch R = 1,943,225,225,225
BEGIN DESCRIPTION:
UNT071 IN SUCR 2.0
END DESCRIPTION:
XS GIS Cut Line= 3
      2264493.34     13368589.12      2263951.65     13368537.04
      2263791.42     13368609.40
#Sta/Elev= 30
  4697.4  181.74  4723.1  181.61  4753.3  180.57  4793.5  178.32  4833.6  175.01
  4878.3  175.07  4883.9  173.83  4914.0  171.69  4924.1  169.91  4954.2  167.35
  4964.2  165.93  4991.4  164.24  4994.1  163.74  4997.4  164.24  5044.6  165.41
  5054.7  167.59  5073.9  169.65  5083.3  171.18  5088.3  171.12  5094.8  173.39
  5114.9  175.84  5185.3  182.46  5205.4  183.87  5273.9  186.25  5304.1  187.23
  5321.7  186.80  5348.4  187.25  5366.6  187.18  5378.9  187.98  5417.4  187.35
#Mann=6,-1,0
  4697.4     0.1       0  4991.4    0.07       0  4997.4     0.1       0
  5073.9    0.08       0  5273.9     0.1       0  5348.4    0.08       0
Bank Sta=4991.4,4997.4
Exp/Cntr=0.3,0.1

Type RM Length L Ch R = 1,718,0,0,0
BEGIN DESCRIPTION:
UNT071 IN SUCR 1.0
END DESCRIPTION:
XS GIS Cut Line= 2
      2264633.33     13368428.10      2263951.82     13368282.44
#Sta/Elev= 30
  4589.7  181.09  4595.4  181.51  4626.1  180.12  4714.2  179.13  4763.6  177.65
  4807.5  175.18  4830.6  174.19  4857.5  171.71  4892.0  169.88  4922.7  166.50
  4956.5  164.02  4963.6  162.91  4973.8  162.72  4994.2  163.68  4997.8  161.95
  5000.6  161.45  5003.8  161.95  5024.9  163.43  5045.2  165.68  5055.6  172.05
  5065.8  173.49  5076.1  175.92  5094.7  178.09  5109.0  178.89  5168.1  183.58
  5188.5  184.58  5198.8  186.14  5219.2  187.24  5249.9  188.06  5286.6  187.73
#Mann=5,-1,0
  4589.7     0.1       0  4807.5    0.12       0  4997.8    0.07       0
  5003.8    0.12       0  5109.0     0.1       0
Bank Sta=4997.8,5003.8
Exp/Cntr=0.3,0.1

Chan Stop Cuts=-1