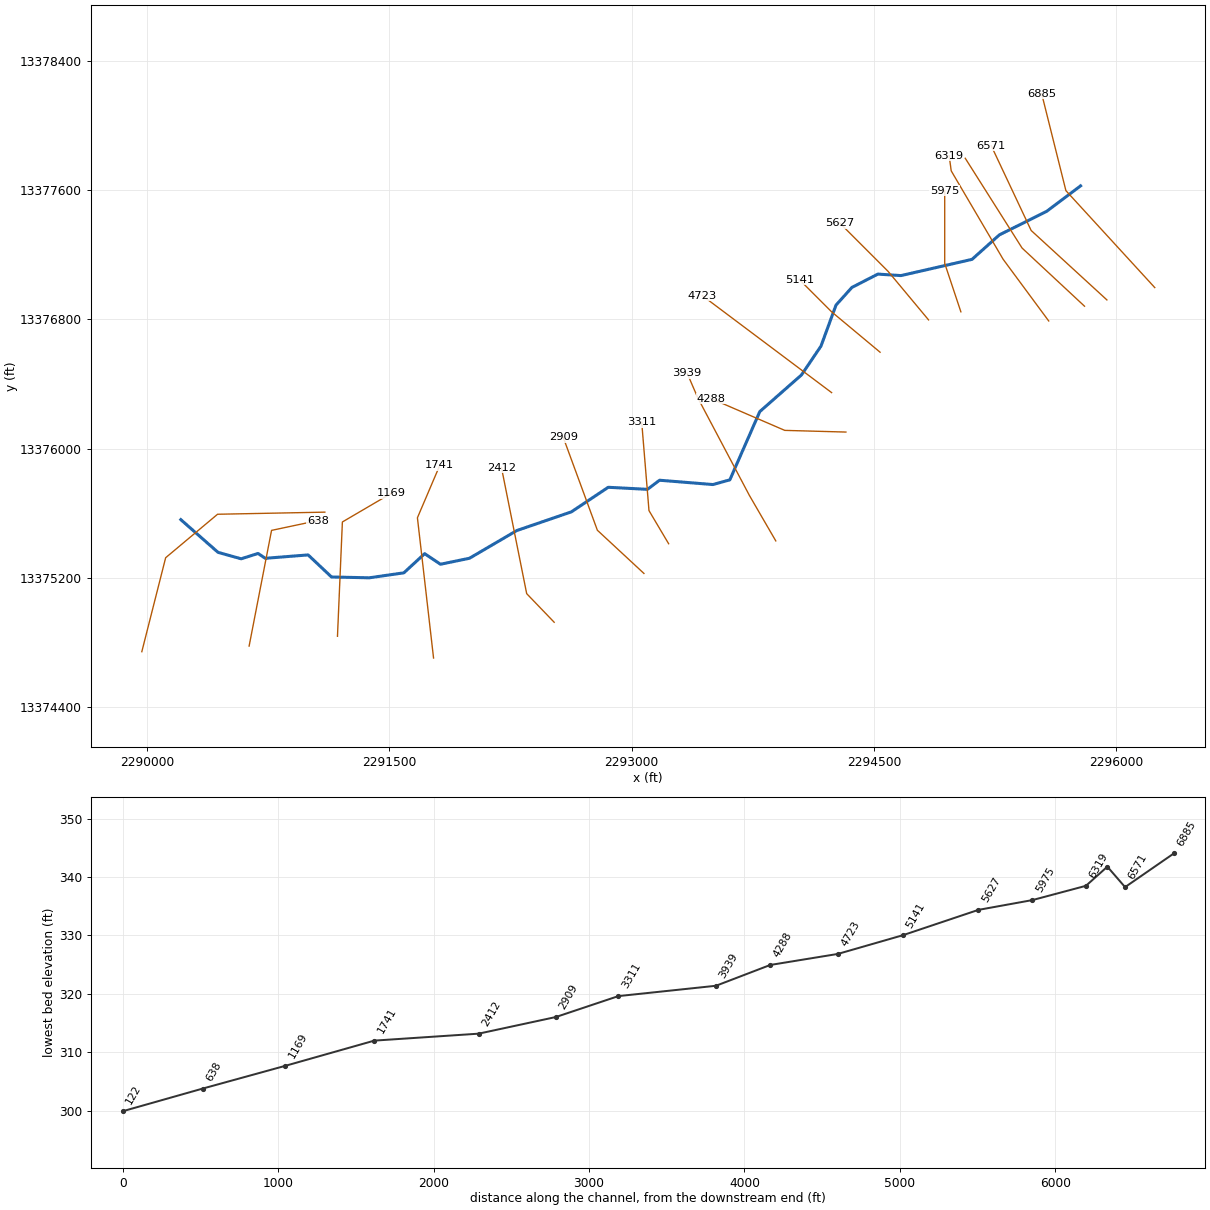
--- UNT073 IN SUCR.prj (project) ---

Proj Title=UNT073 IN SUCR Base Level Engineering
Current Plan=p01
Default Exp/Contr=0.3,0.1
English Units
Geom File=g01
Flow File=f01
Plan File=p01
Y Axis Title=Elevation
X Axis Title(PF)=Main Channel Distance
X Axis Title(XS)=Station
BEGIN DESCRIPTION:
UNT073 IN SUCR
END DESCRIPTION:
DSS Export Rating Curves= 0
DSS Export Rating Curve Sorted= 0
DSS Export Volume Flow Curves= 0
DXF OffsetX= 0
DXF OffsetY= 0
DXF ScaleX= 1
DXF ScaleY= 10

--- UNT073 IN SUCR.p01 (plan) ---

Plan Title=Multiple Run
Short Identifier=Multiple
Geom File=g01
Flow File=f01
Subcritical Flow
K Sum by GR= 0
Std Step Tol= 0.01
Critical Tol= 0.01
Num of Std Step Trials= 20
Max Error Tol= 0.3
Flow Tol Ratio= 0.001
Split Flow NTrial= 30
Split Flow Tol= 0.02
Split Flow Ratio= 0.02
Log Output Level= 0
Friction Slope Method= 1
Unsteady Friction Slope Method= 2
Unsteady Bridges Friction Slope Method= 1
Parabolic Critical Depth
Global Vel Dist=  1 , 1 , 1
Global Log Level= 0
CheckData=True
Encroach Param= -1, 0, 0, 0
BEGIN DESCRIPTION:
Multiple Run
END DESCRIPTION:

--- UNT073 IN SUCR.f01 (steady flow) ---

Flow Title=Multiple
Program Version=4.10
Number of Profiles= 7
Profile Names=10-year,25-year,50-year,1pct_min,100-year,1pct_plu,500-year
River Rch & RM=UNT073 IN SUCR,Reach-1         ,6885
     382     530     652     586     793    1073    1179
River Rch & RM=UNT073 IN SUCR,Reach-1         ,3939
     644     919    1152    1054    1426    1928    2195
River Rch & RM=UNT073 IN SUCR,Reach-1         ,3311
     644     919    1152    1054    1426    1928    2195
Boundary for River Rch & Prof#=UNT073 IN SUCR,Reach-1         , 1
Up Type= 0
Dn Type= 3
Dn Slope=0.005
Boundary for River Rch & Prof#=UNT073 IN SUCR,Reach-1         , 2
Up Type= 0
Dn Type= 3
Dn Slope=0.005
Boundary for River Rch & Prof#=UNT073 IN SUCR,Reach-1         , 3
Up Type= 0
Dn Type= 3
Dn Slope=0.005
Boundary for River Rch & Prof#=UNT073 IN SUCR,Reach-1         , 4
Up Type= 0
Dn Type= 3
Dn Slope=0.005
Boundary for River Rch & Prof#=UNT073 IN SUCR,Reach-1         , 5
Up Type= 0
Dn Type= 3
Dn Slope=0.005
Boundary for River Rch & Prof#=UNT073 IN SUCR,Reach-1         , 6
Up Type= 0
Dn Type= 3
Dn Slope=0.005
Boundary for River Rch & Prof#=UNT073 IN SUCR,Reach-1         , 7
Up Type= 0
Dn Type= 3
Dn Slope=0.005
DSS Import GetInterval= 0
DSS Import GetPeak= 0
DSS Import FillOption= 0

--- UNT073 IN SUCR.g01 (geometry) ---

Geom Title=Existing Conditions

River Reach=UNT073 IN SUCR,Reach-1
Reach XY= 30
      2295778.47     13377626.49      2295568.70     13377468.77
      2295275.73     13377322.94      2295106.82     13377171.58
      2294667.02     13377071.15      2294524.18     13377080.40
      2294363.32     13376997.93      2294264.85     13376888.34
      2294171.90     13376634.74      2294051.10     13376456.15
      2293793.23     13376229.45      2293607.72     13375806.85
      2293502.76     13375777.91      2293172.84     13375804.59
      2293097.85     13375748.22      2292855.33     13375760.92
      2292626.98     13375608.79      2292289.39     13375493.21
      2291996.58     13375321.74      2291817.05     13375284.58
      2291718.88     13375350.04      2291590.28     13375231.48
      2291376.17     13375200.74      2291142.62     13375205.75
      2290997.83     13375342.37      2290732.84     13375321.45
      2290687.68     13375351.34      2290583.38     13375318.30
      2290440.19     13375358.26      2290209.97     13375560.67

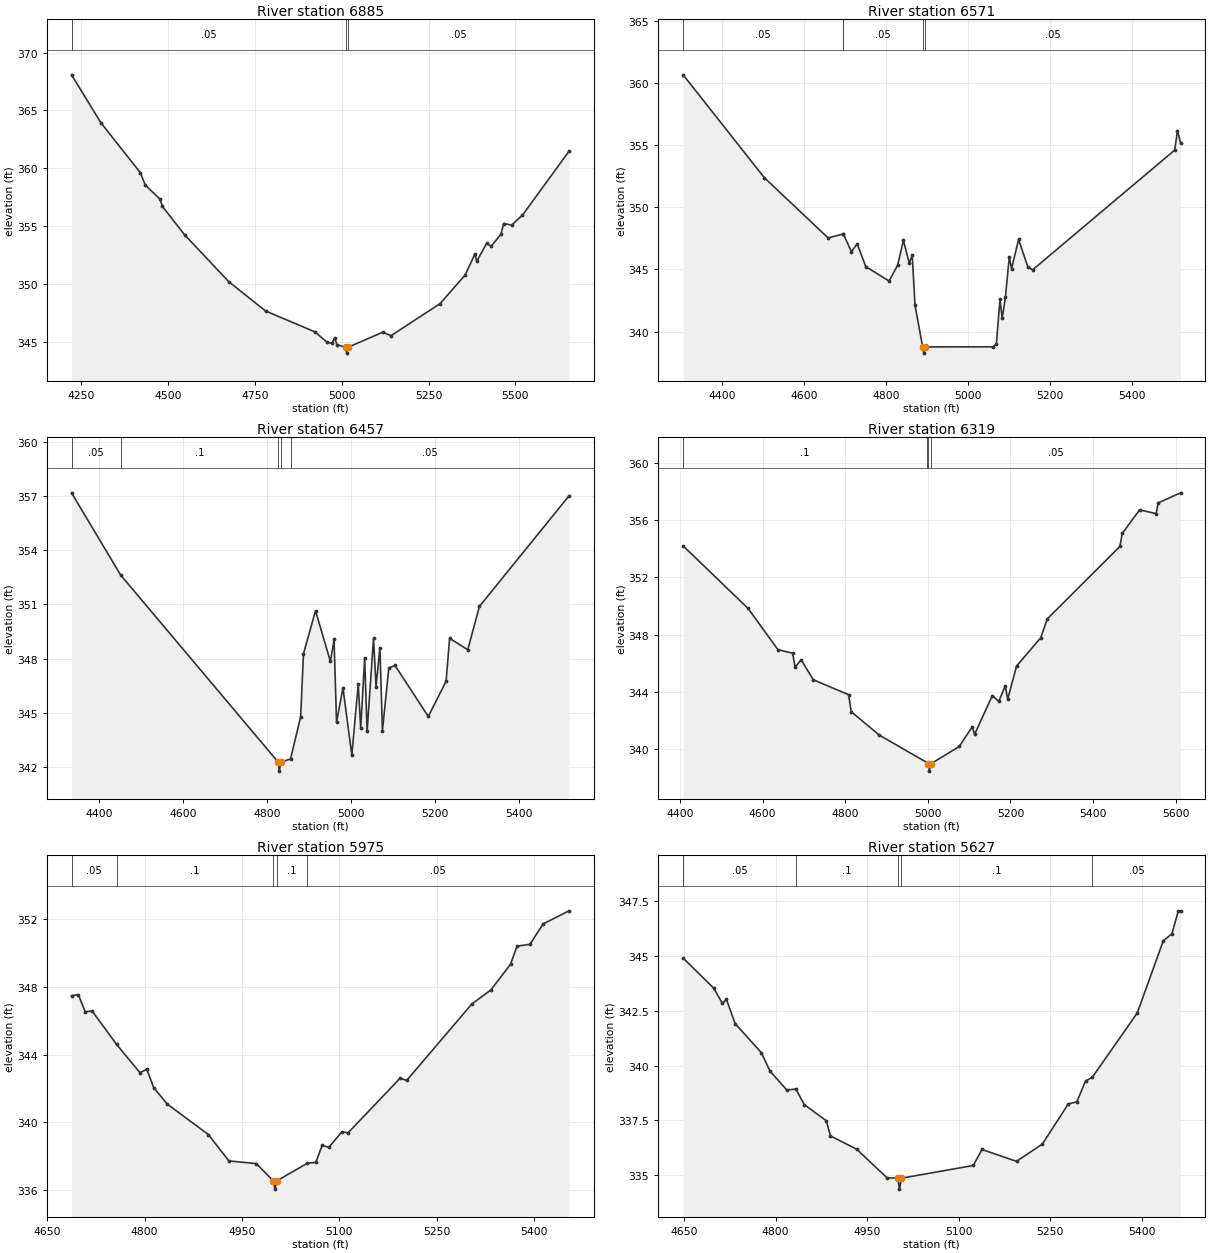
Type RM Length L Ch R = 1,6885,314,314,314
BEGIN DESCRIPTION:
UNT073 IN SUCR 13.0
END DESCRIPTION:
XS GIS Cut Line= 3
      2296237.70     13376996.88      2295687.72     13377596.85
      2295537.71     13378196.88
#Sta/Elev= 30
  4222.0  368.08  4306.8  363.93  4420.2  359.62  4434.4  358.55  4476.9  357.34
  4483.7  356.71  4547.5  354.26  4674.9  350.20  4780.9  347.67  4922.8  345.87
  4957.9  344.97  4972.1  344.88  4979.5  345.35  4986.3  344.77  5011.6  344.53
  5014.4  344.03  5017.6  344.53  5118.4  345.84  5141.6  345.53  5283.3  348.31
  5355.4  350.78  5383.8  352.61  5388.9  351.96  5417.3  353.52  5430.2  353.26
  5458.5  354.30  5466.3  355.23  5489.4  355.10  5520.4  355.95  5654.4  361.47
#Mann=3,-1,0
  4222.0    0.05       0  5011.6    0.03       0  5017.6    0.05       0
Bank Sta=5011.6,5017.6
Exp/Cntr=0.3,0.1

Type RM Length L Ch R = 1,6571,114,114,114
BEGIN DESCRIPTION:
Mapping XS 7f0aa641
END DESCRIPTION:
XS GIS Cut Line= 3
      2295941.51     13376920.54      2295472.75     13377350.24
      2295226.18     13377873.66
#Sta/Elev= 30
  4304.1  360.68  4502.2  352.40  4658.2  347.54  4695.2  347.86  4695.4  347.86
  4714.9  346.44  4729.1  347.06  4750.1  345.23  4806.8  344.07  4827.8  345.34
  4842.0  347.35  4856.1  345.52  4863.5  346.14  4870.3  342.12  4888.9  338.76
  4891.6  338.26  4894.9  338.76  5060.4  338.77  5068.9  339.00  5077.7  342.59
  5083.2  341.07  5091.0  342.76  5100.4  346.01  5106.0  345.06  5123.2  347.42
  5146.0  345.18  5157.4  344.97  5504.4  354.62  5511.1  356.19  5518.6  355.18
#Mann=5,-1,0
  4304.1    0.05       0  4695.2     0.1       0  4695.4    0.05       0
  4888.9    0.03       0  4894.9    0.05       0
Bank Sta=4888.9,4894.9
Exp/Cntr=0.3,0.1

Type RM Length L Ch R = 1,6457,138,138,138
BEGIN DESCRIPTION:
UNT073 IN SUCR 12.0
END DESCRIPTION:
XS GIS Cut Line= 3
      2295802.88     13376881.70      2295416.33     13377241.73
      2295064.76     13377797.29
#Sta/Elev= 30
  4334.2  357.19  4451.0  352.64  4826.8  342.26  4829.6  341.76  4832.8  342.26
  4856.2  342.43  4880.3  344.77  4887.1  348.27  4915.8  350.65  4951.3  347.84
  4960.0  349.06  4965.9  344.46  4981.2  346.38  5002.3  342.64  5017.6  346.59
  5023.5  344.14  5032.9  348.02  5038.8  343.97  5054.1  349.15  5060.0  346.45
  5069.3  348.60  5075.3  344.01  5090.5  347.48  5105.2  347.62  5184.6  344.79
  5227.0  346.74  5235.4  349.12  5278.7  348.49  5306.4  350.89  5519.9  357.02
#Mann=5,-1,0
  4334.2    0.05       0  4451.0     0.1       0  4826.8    0.03       0
  4832.8     0.1       0  4856.2    0.05       0
Bank Sta=4826.8,4832.8
Exp/Cntr=0.3,0.1

Type RM Length L Ch R = 1,6319,344,344,344
BEGIN DESCRIPTION:
Mapping XS 6cf507d6
END DESCRIPTION:
XS GIS Cut Line= 4
      2295581.25     13376790.35      2295299.14     13377172.29
      2294977.96     13377719.16      2294965.13     13377813.24
#Sta/Elev= 30
  4407.8  354.20  4565.1  349.83  4637.2  346.96  4672.7  346.71  4678.9  345.74
  4693.5  346.25  4722.8  344.86  4808.4  343.81  4814.6  342.63  4882.4  341.00
  4997.8  339.08  5000.9  338.98  5003.7  338.48  5006.9  338.98  5076.2  340.20
  5107.5  341.57  5113.3  341.05  5156.2  343.75  5171.9  343.35  5187.6  344.43
  5193.4  343.49  5214.8  345.81  5273.5  347.79  5289.1  349.10  5465.0  354.16
  5470.8  355.07  5512.6  356.71  5552.7  356.45  5557.8  357.20  5611.8  357.90
#Mann=4,-1,0
  4407.8     0.1       0  4997.8    0.05       0  5000.9    0.03       0
  5006.9    0.05       0
Bank Sta=5000.9,5006.9
Exp/Cntr=0.3,0.1

Type RM Length L Ch R = 1,5975,348,348,348
BEGIN DESCRIPTION:
UNT073 IN SUCR 11.0
END DESCRIPTION:
XS GIS Cut Line= 3
      2295037.71     13376846.88      2294937.72     13377146.85
      2294937.72     13377596.86
#Sta/Elev= 30
  4687.4  347.49  4697.9  347.55  4708.5  346.53  4719.0  346.59  4756.9  344.60
  4792.8  342.93  4803.3  343.14  4813.9  342.05  4834.9  341.07  4898.2  339.27
  4929.8  337.71  4972.0  337.55  4998.0  336.54  5000.7  336.04  5004.0  336.54
  5050.6  337.57  5063.6  337.62  5073.6  338.64  5083.6  338.51  5103.6  339.42
  5113.6  339.38  5193.6  342.61  5203.6  342.47  5303.6  346.98  5333.6  347.84
  5363.6  349.35  5373.6  350.42  5393.6  350.53  5413.6  351.73  5453.6  352.51
#Mann=5,-1,0
  4687.4    0.05       0  4756.9     0.1       0  4998.0    0.07       0
  5004.0     0.1       0  5050.6    0.05       0
Bank Sta=4998,5004
Exp/Cntr=0.3,0.1

Type RM Length L Ch R = 1,5627,486,486,486
BEGIN DESCRIPTION:
UNT073 IN SUCR 10.0
END DESCRIPTION:
XS GIS Cut Line= 3
      2294837.70     13376796.87      2294587.72     13377096.85
      2294287.69     13377396.89
#Sta/Elev= 30
  4648.6  344.91  4698.7  343.54  4713.0  342.84  4719.5  343.03  4733.8  341.92
  4776.8  340.59  4791.1  339.74  4818.4  338.89  4833.2  338.93  4847.1  338.22
  4882.9  337.49  4890.0  336.79  4933.0  336.18  4982.5  334.88  5000.3  334.86
  5003.0  334.36  5006.3  334.86  5123.9  335.44  5138.1  336.17  5194.7  335.63
  5237.1  336.42  5279.5  338.25  5293.6  338.35  5307.8  339.30  5318.9  339.47
  5392.6  342.41  5435.1  345.70  5449.2  346.02  5459.8  347.07  5463.4  347.07
#Mann=5,-1,0
  4648.6    0.05       0  4833.2     0.1       0  5000.3    0.07       0
  5006.3     0.1       0  5318.9    0.05       0
Bank Sta=5000.3,5006.3
Exp/Cntr=0.3,0.1

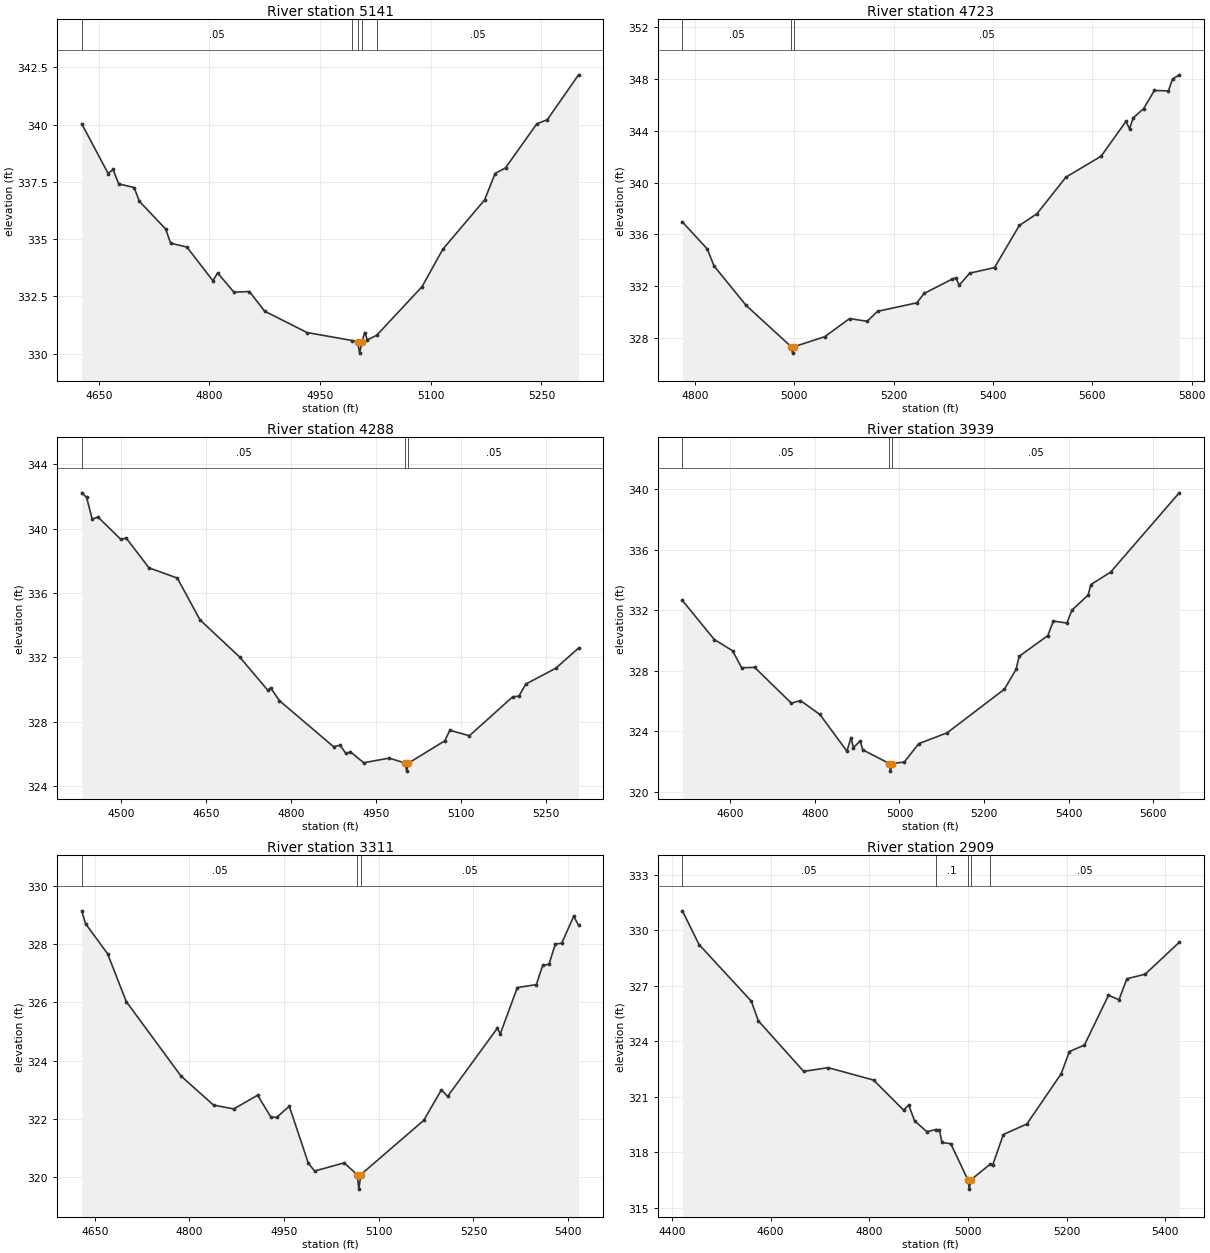
Type RM Length L Ch R = 1,5141,418,418,418
BEGIN DESCRIPTION:
UNT073 IN SUCR 9.0
END DESCRIPTION:
XS GIS Cut Line= 3
      2294537.74     13376596.84      2294237.72     13376846.85
      2294037.71     13377046.87
#Sta/Elev= 30
  4626.9  340.03  4662.7  337.86  4669.2  338.04  4677.0  337.41  4697.9  337.25
  4705.0  336.65  4740.8  335.43  4747.3  334.82  4769.5  334.65  4804.6  333.18
  4811.1  333.52  4833.2  332.68  4854.1  332.71  4874.9  331.85  4932.2  330.92
  4993.5  330.57  5000.8  330.52  5003.5  330.02  5006.8  330.52  5010.3  330.92
  5014.2  330.60  5026.7  330.80  5088.1  332.92  5116.4  334.56  5173.0  336.71
  5187.1  337.86  5201.3  338.11  5243.7  340.03  5257.9  340.21  5300.3  342.17
#Mann=5,-1,0
  4626.9    0.05       0  4993.5     0.1       0  5000.8    0.07       0
  5006.8     0.1       0  5026.7    0.05       0
Bank Sta=5000.8,5006.8
Exp/Cntr=0.3,0.1

Type RM Length L Ch R = 1,4723,435,435,435
BEGIN DESCRIPTION:
UNT073 IN SUCR 8.0
END DESCRIPTION:
XS GIS Cut Line= 3
      2294237.76     13376346.83      2294037.72     13376496.85
      2293437.76     13376946.83
#Sta/Elev= 30
  4775.0  336.96  4825.0  334.87  4838.6  333.56  4903.2  330.51  4993.9  327.32
  4996.7  326.82  4999.9  327.32  5061.5  328.09  5111.5  329.49  5146.9  329.28
  5167.8  330.05  5246.9  330.71  5261.5  331.43  5317.8  332.54  5325.0  332.64
  5332.3  332.08  5353.2  333.00  5403.2  333.43  5453.2  336.69  5488.6  337.59
  5546.9  340.42  5617.8  342.04  5667.8  344.73  5675.0  344.16  5682.3  345.00
  5703.2  345.71  5725.0  347.12  5753.2  347.09  5761.5  348.00  5775.0  348.33
#Mann=3,-1,0
  4775.0    0.05       0  4993.9    0.03       0  4999.9    0.05       0
Bank Sta=4993.9,4999.9
Exp/Cntr=0.3,0.1

Type RM Length L Ch R = 1,4288,349,349,349
BEGIN DESCRIPTION:
UNT073 IN SUCR 7.0
END DESCRIPTION:
XS GIS Cut Line= 3
      2294326.20     13376102.71      2293947.69     13376113.13
      2293491.00     13376310.33
#Sta/Elev= 30
  4430.7  342.23  4439.2  341.95  4449.2  340.59  4459.2  340.73  4499.2  339.35
  4509.2  339.41  4549.2  337.57  4599.2  336.93  4639.3  334.33  4709.3  332.02
  4758.7  329.96  4763.7  330.11  4779.3  329.31  4874.7  326.45  4886.4  326.54
  4896.5  326.03  4904.5  326.13  4928.0  325.45  4972.7  325.74  5000.9  325.43
  5003.7  324.93  5006.9  325.43  5070.7  326.81  5079.9  327.47  5114.3  327.13
  5190.6  329.55  5201.5  329.59  5213.8  330.34  5266.8  331.33  5306.8  332.58
#Mann=3,-1,0
  4430.7    0.05       0  5000.9    0.03       0  5006.9    0.05       0
Bank Sta=5000.9,5006.9
Exp/Cntr=0.3,0.1

Type RM Length L Ch R = 1,3939,628,628,628
BEGIN DESCRIPTION:
UNT073 IN SUCR 6.0
END DESCRIPTION:
XS GIS Cut Line= 4
      2293892.13     13375429.11      2293728.94     13375710.35
      2293409.49     13376314.52      2293343.52     13376467.30
#Sta/Elev= 30
  4486.6  332.64  4562.1  330.06  4605.2  329.32  4626.7  328.20  4657.4  328.22
  4744.3  325.86  4765.8  326.03  4811.8  325.11  4875.7  322.69  4885.3  323.59
  4890.9  322.92  4907.3  323.37  4913.0  322.78  4976.0  321.87  4978.7  321.37
  4982.0  321.87  5011.4  321.97  5045.4  323.18  5113.2  323.91  5248.1  326.78
  5275.8  328.09  5282.9  328.95  5350.8  330.32  5363.8  331.28  5396.0  331.15
  5407.8  332.00  5446.2  333.00  5452.6  333.69  5499.2  334.51  5661.6  339.75
#Mann=3,-1,0
  4486.6    0.05       0  4976.0    0.03       0  4982.0    0.05       0
Bank Sta=4976,4982
Exp/Cntr=0.3,0.1

Type RM Length L Ch R = 1,3311,402,402,402
BEGIN DESCRIPTION:
UNT073 IN SUCR 5.0
END DESCRIPTION:
XS GIS Cut Line= 3
      2293228.96     13375411.70      2293107.41     13375616.60
      2293062.41     13376163.51
#Sta/Elev= 30
  4629.5  329.14  4635.5  328.70  4670.4  327.67  4700.0  326.03  4786.6  323.48
  4838.3  322.48  4870.4  322.35  4908.1  322.82  4929.1  322.07  4938.2  322.06
  4958.3  322.44  4988.4  320.49  4998.4  320.22  5045.2  320.50  5065.7  320.10
  5068.4  319.60  5071.7  320.10  5171.4  321.96  5199.1  323.00  5209.1  322.78
  5287.6  325.11  5292.6  324.93  5319.5  326.51  5349.6  326.61  5359.7  327.27
  5369.7  327.31  5379.7  328.00  5389.8  328.03  5408.8  328.95  5416.5  328.65
#Mann=3,-1,0
  4629.5    0.05       0  5065.7    0.03       0  5071.7    0.05       0
Bank Sta=5065.7,5071.7
Exp/Cntr=0.3,0.1

Type RM Length L Ch R = 1,2909,497,497,497
BEGIN DESCRIPTION:
UNT073 IN SUCR 4.0
END DESCRIPTION:
XS GIS Cut Line= 3
      2293076.15     13375227.73      2292787.96     13375495.07
      2292576.15     13376071.49
#Sta/Elev= 30
  4421.3  331.05  4455.0  329.23  4561.0  326.17  4575.2  325.11  4667.1  322.38
  4716.9  322.58  4808.8  321.91  4869.6  320.29  4880.2  320.56  4891.9  319.71
  4917.0  319.12  4935.3  319.24  4942.2  319.22  4947.5  318.54  4965.4  318.47
  5000.1  316.52  5002.9  316.02  5006.1  316.52  5044.9  317.36  5050.7  317.35
  5072.0  318.97  5119.7  319.54  5189.2  322.25  5205.8  323.45  5236.3  323.80
  5285.1  326.49  5306.4  326.25  5322.4  327.38  5359.6  327.63  5428.5  329.35
#Mann=5,-1,0
  4421.3    0.05       0  4935.3     0.1       0  5000.1    0.07       0
  5006.1     0.1       0  5044.9    0.05       0
Bank Sta=5000.1,5006.1
Exp/Cntr=0.3,0.1

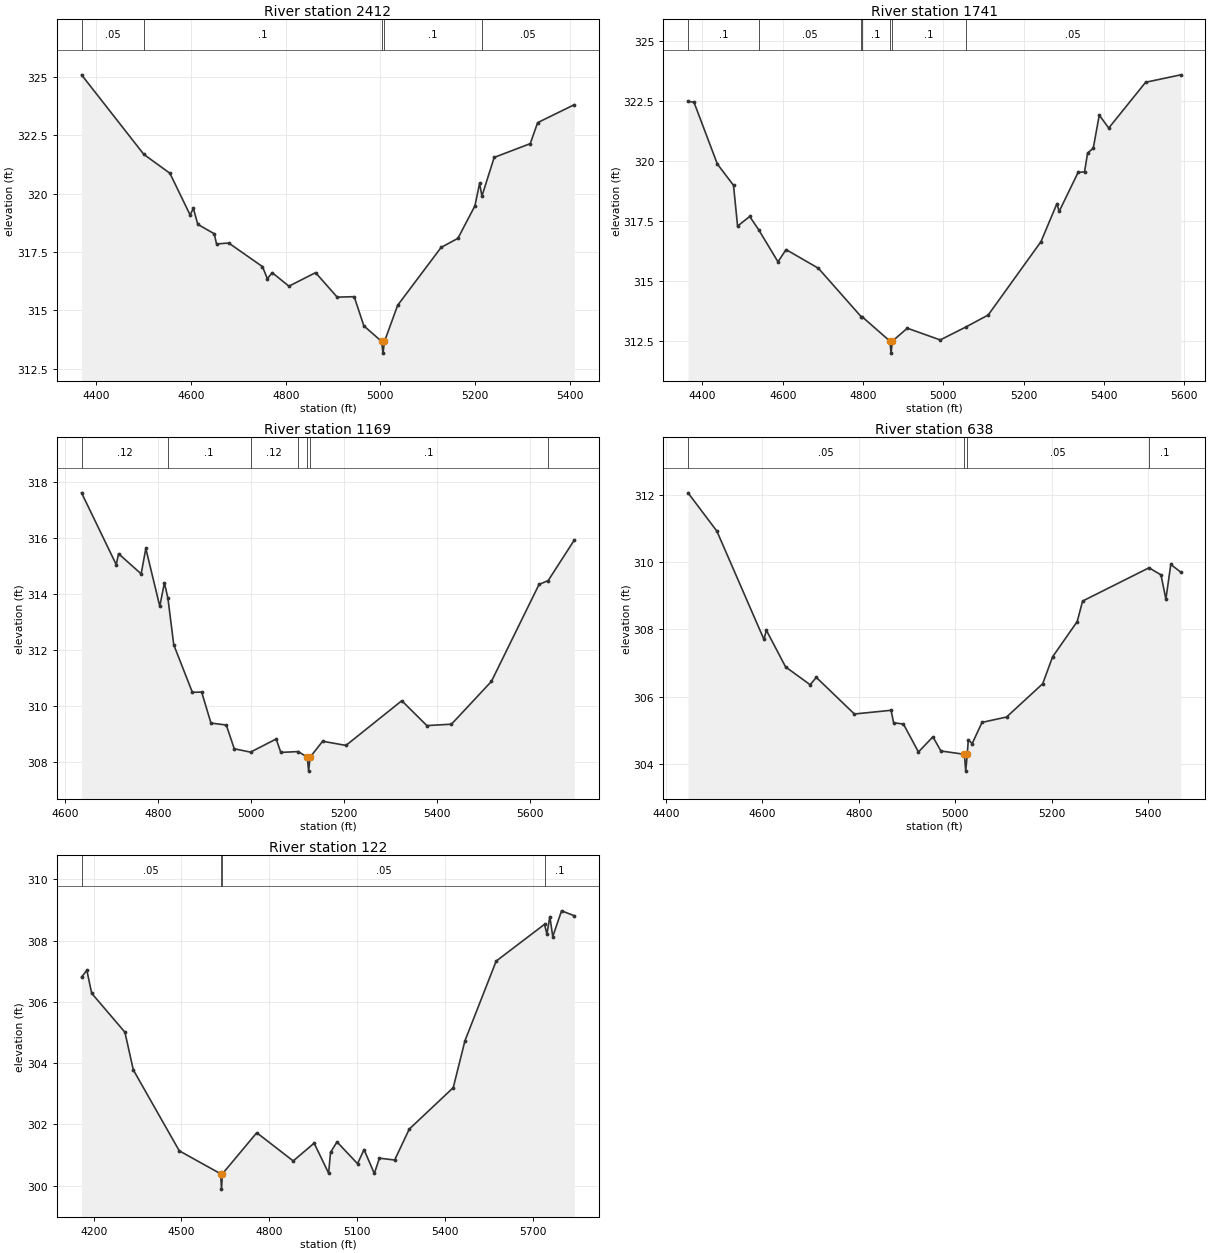
Type RM Length L Ch R = 1,2412,671,671,671
BEGIN DESCRIPTION:
UNT073 IN SUCR 3.0
END DESCRIPTION:
XS GIS Cut Line= 3
      2292520.60     13374925.63      2292350.46     13375102.71
      2292194.43     13375882.90
#Sta/Elev= 30
  4368.6  325.10  4500.2  321.69  4555.3  320.88  4597.8  319.10  4605.0  319.37
  4614.2  318.69  4648.8  318.29  4653.9  317.85  4679.6  317.89  4750.8  316.88
  4761.2  316.36  4771.4  316.62  4806.8  316.04  4863.1  316.62  4908.8  315.57
  4944.7  315.59  4965.1  314.34  5002.7  313.67  5005.5  313.17  5008.7  313.67
  5036.5  315.22  5128.3  317.70  5163.8  318.09  5199.7  319.48  5209.7  320.45
  5214.6  319.90  5240.5  321.56  5316.7  322.15  5332.3  323.05  5409.8  323.82
#Mann=5,-1,0
  4368.6    0.05       0  4500.2     0.1       0  5002.7    0.07       0
  5008.7     0.1       0  5214.6    0.05       0
Bank Sta=5002.7,5008.7
Exp/Cntr=0.3,0.1

Type RM Length L Ch R = 1,1741,572,572,572
BEGIN DESCRIPTION:
UNT073 IN SUCR 2.0
END DESCRIPTION:
XS GIS Cut Line= 3
      2291774.07     13374704.29      2291674.25     13375572.33
      2291812.91     13375897.32
#Sta/Elev= 30
  4364.1  322.48  4378.9  322.45  4437.1  319.87  4477.4  318.98  4487.5  317.28
  4517.7  317.68  4540.0  317.13  4588.1  315.79  4608.3  316.30  4688.8  315.52
  4795.3  313.50  4798.2  313.49  4867.0  312.48  4869.7  311.98  4873.0  312.48
  4910.2  313.02  4992.2  312.53  5055.9  313.07  5111.6  313.57  5243.0  316.63
  5282.9  318.22  5288.3  317.89  5335.5  319.52  5351.5  319.54  5359.2  320.33
  5373.3  320.53  5388.2  321.91  5411.8  321.37  5503.7  323.28  5591.2  323.59
#Mann=7,-1,0
  4364.1     0.1       0  4540.0    0.05       0  4795.3    0.12       0
  4798.2     0.1       0  4867.0    0.07       0  4873.0     0.1       0
  5055.9    0.05       0
Bank Sta=4867,4873
Exp/Cntr=0.3,0.1

Type RM Length L Ch R = 1,1169,531,531,531
BEGIN DESCRIPTION:
Mapping XS 0cacc3d6
END DESCRIPTION:
XS GIS Cut Line= 3
      2291179.46     13374838.78      2291209.84     13375546.29
      2291513.18     13375723.96
#Sta/Elev= 30
  4635.5  317.63  4710.1  315.06  4715.1  315.45  4763.7  314.73  4773.7  315.64
  4803.7  313.57  4813.7  314.41  4821.3  313.85  4833.8  312.19  4873.8  310.49
  4893.8  310.50  4913.8  309.39  4946.8  309.32  4963.9  308.47  4998.9  308.35
  5054.0  308.82  5064.0  308.34  5101.4  308.37  5121.0  308.17  5123.8  307.67
  5127.0  308.17  5154.0  308.74  5204.1  308.59  5324.2  310.19  5378.1  309.30
  5431.0  309.35  5516.9  310.88  5619.3  314.35  5639.0  314.49  5695.2  315.94
#Mann=7,-1,0
  4635.5    0.12       0  4821.3     0.1       0  4998.9    0.12       0
  5101.4     0.1       0  5121.0    0.07       0  5127.0     0.1       0
  5639.0    0.05       0
Bank Sta=5121,5127
Exp/Cntr=0.3,0.1

Type RM Length L Ch R = 1,638,516,516,516
BEGIN DESCRIPTION:
Mapping XS d89c62b4
END DESCRIPTION:
XS GIS Cut Line= 3
      2290632.57     13374778.01      2290771.47     13375494.21
      2291057.96     13375554.98
#Sta/Elev= 30
  4445.8  312.06  4505.7  310.92  4603.3  307.70  4608.4  307.97  4648.3  306.88
  4699.3  306.35  4711.9  306.57  4791.0  305.48  4867.1  305.59  4872.4  305.22
  4892.8  305.18  4923.9  304.35  4953.9  304.80  4970.5  304.38  5019.2  304.28
  5022.0  303.78  5025.2  304.28  5027.3  304.71  5035.4  304.60  5055.8  305.23
  5106.7  305.39  5181.7  306.38  5202.2  307.18  5253.3  308.23  5264.5  308.84
  5402.3  309.83  5427.1  309.62  5437.3  308.90  5447.5  309.93  5468.2  309.70
#Mann=4,-1,0
  4445.8    0.05       0  5019.2    0.03       0  5025.2    0.05       0
  5402.3     0.1       0
Bank Sta=5019.2,5025.2
Exp/Cntr=0.3,0.1

Type RM Length L Ch R = 1,122,0,0,0
BEGIN DESCRIPTION:
UNT073 IN SUCR 1.0
END DESCRIPTION:
XS GIS Cut Line= 4
      2289968.52     13374743.32      2290116.09     13375324.94
      2290437.27     13375594.03      2291101.29     13375607.05
#Sta/Elev= 30
  4158.7  306.81  4176.8  307.03  4193.3  306.28  4306.8  305.01  4335.5  303.78
  4492.5  301.14  4633.9  300.39  4636.7  299.89  4639.9  300.39  4757.2  301.73
  4881.7  300.81  4953.2  301.39  5002.7  300.41  5009.2  301.09  5031.3  301.43
  5101.5  300.72  5123.6  301.18  5158.8  300.40  5176.1  300.90  5228.2  300.84
  5278.2  301.85  5428.3  303.20  5468.3  304.73  5575.0  307.33  5740.1  308.53
  5748.3  308.21  5758.3  308.78  5768.3  308.13  5798.3  308.97  5841.9  308.81
#Mann=4,-1,0
  4158.7    0.05       0  4633.9    0.03       0  4639.9    0.05       0
  5740.1     0.1       0
Bank Sta=4633.9,4639.9
Exp/Cntr=0.3,0.1

Chan Stop Cuts=-1