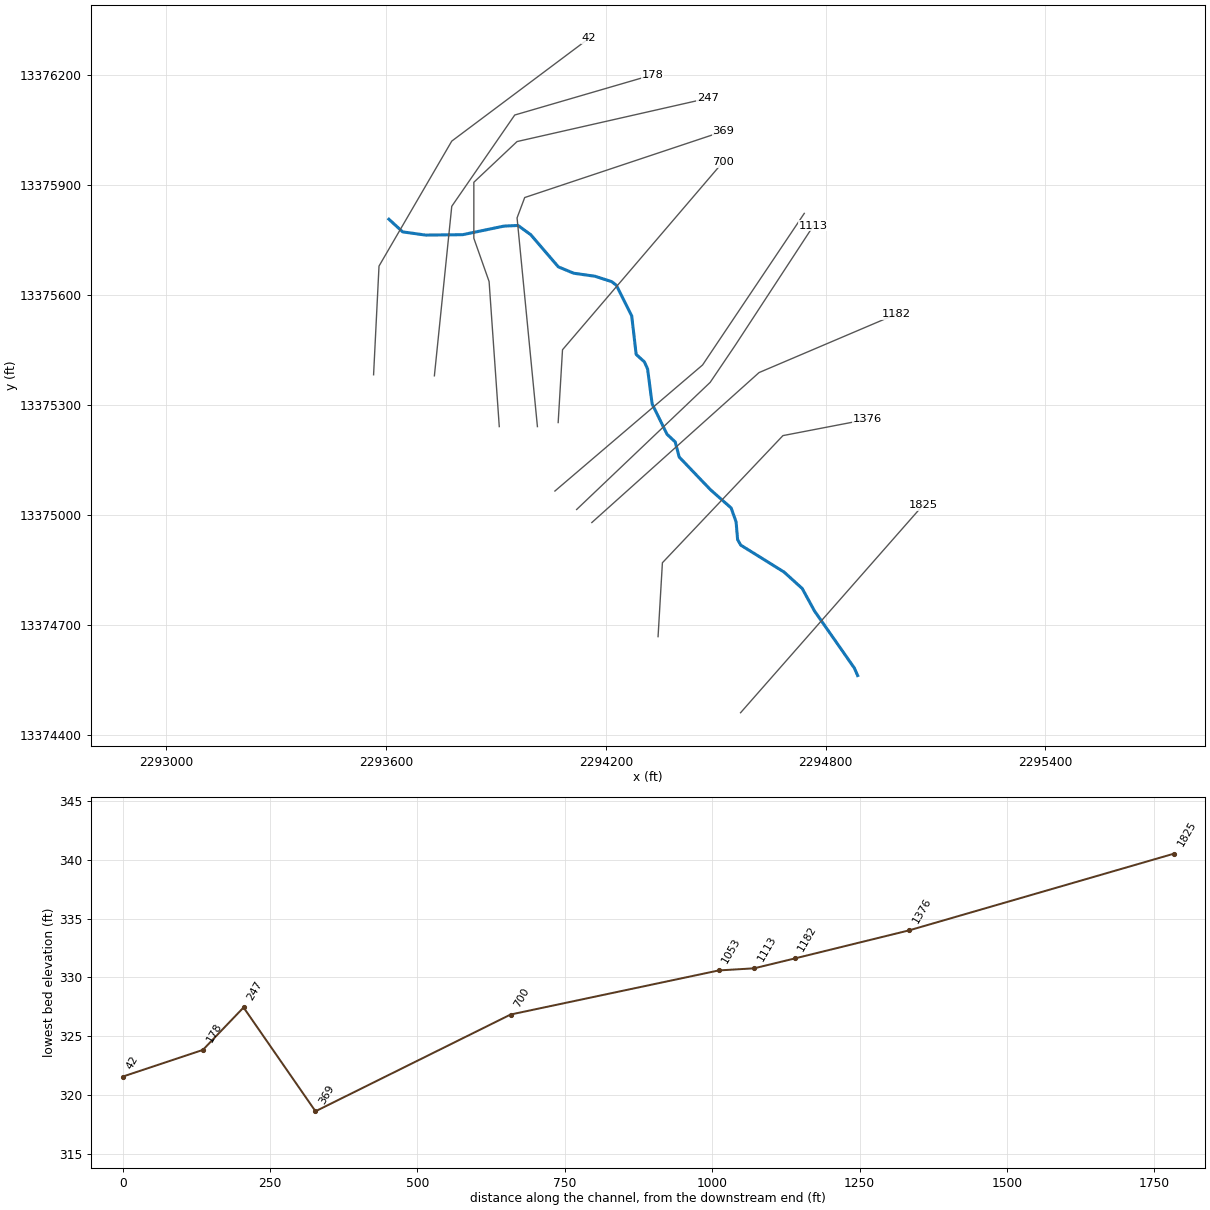
--- UNT074 IN SUCR.prj (project) ---

Proj Title=UNT074 IN SUCR Base Level Engineering
Current Plan=p01
Default Exp/Contr=0.3,0.1
English Units
Geom File=g01
Flow File=f01
Plan File=p01
BEGIN DESCRIPTION:
UNT074 IN SUCR
END DESCRIPTION:

--- UNT074 IN SUCR.p01 (plan) ---

Plan Title=Multiple Run
Short Identifier=Multiple
Geom File=g01
Flow File=f01
Subcritical Flow
K Sum by GR= 0
Std Step Tol= 0.01
Critical Tol= 0.01
Num of Std Step Trials= 20
Max Error Tol= 0.3
Flow Tol Ratio= 0.001
Split Flow NTrial= 30
Split Flow Tol= 0.02
Split Flow Ratio= 0.02
Log Output Level= 0
Friction Slope Method= 1
Unsteady Friction Slope Method= 2
Unsteady Bridges Friction Slope Method= 1
Parabolic Critical Depth
Global Vel Dist=  1 , 1 , 1
Global Log Level= 0
CheckData=True
Encroach Param= -1, 0, 0, 0
BEGIN DESCRIPTION:
Multiple Run
END DESCRIPTION:

--- UNT074 IN SUCR.f01 (steady flow) ---

Flow Title=Multiple
Number of Profiles=7
Profile Names=10-year,25-year,50-year,1pct_min,100-year,1pct_plu,500-year
River Rch & RM= UNT074 IN SUCR,Reach-1,1825
     319     440     539     485     655     886     970
Boundary for River Rch & Prof#=UNT074 IN SUCR,Reach-1,1
Up Type=0
Dn Type=3
Dn Slope=0.005
Boundary for River Rch & Prof#=UNT074 IN SUCR,Reach-1,2
Up Type=0
Dn Type=3
Dn Slope=0.005
Boundary for River Rch & Prof#=UNT074 IN SUCR,Reach-1,3
Up Type=0
Dn Type=3
Dn Slope=0.005
Boundary for River Rch & Prof#=UNT074 IN SUCR,Reach-1,4
Up Type=0
Dn Type=3
Dn Slope=0.005
Boundary for River Rch & Prof#=UNT074 IN SUCR,Reach-1,5
Up Type=0
Dn Type=3
Dn Slope=0.005
Boundary for River Rch & Prof#=UNT074 IN SUCR,Reach-1,6
Up Type=0
Dn Type=3
Dn Slope=0.005
Boundary for River Rch & Prof#=UNT074 IN SUCR,Reach-1,7
Up Type=0
Dn Type=3
Dn Slope=0.005

--- UNT074 IN SUCR.g01 (geometry) ---

Geom Title=Existing Conditions

River Reach=UNT074 IN SUCR,Reach-1
Reach XY= 30
      2294887.72     13374561.86      2294878.79     13374582.23
      2294770.05     13374737.81      2294736.31     13374799.38
      2294686.69     13374844.33      2294568.58     13374917.69
      2294559.98     13374932.67      2294555.79     13374981.06
      2294542.28     13375019.11      2294486.01     13375068.65
      2294400.42     13375158.08      2294389.54     13375199.29
      2294367.32     13375220.01      2294326.52     13375302.96
      2294314.19     13375398.05      2294305.51     13375417.59
      2294282.94     13375437.98      2294270.79     13375543.02
      2294228.74     13375626.90      2294215.84     13375636.65
      2294170.70     13375651.24      2294112.37     13375659.57
      2294070.47     13375676.90      2293994.96     13375764.74
      2293960.24     13375789.91      2293922.05     13375788.17
      2293809.20     13375764.74      2293707.97     13375763.62
      2293645.30     13375772.39      2293607.72     13375806.85

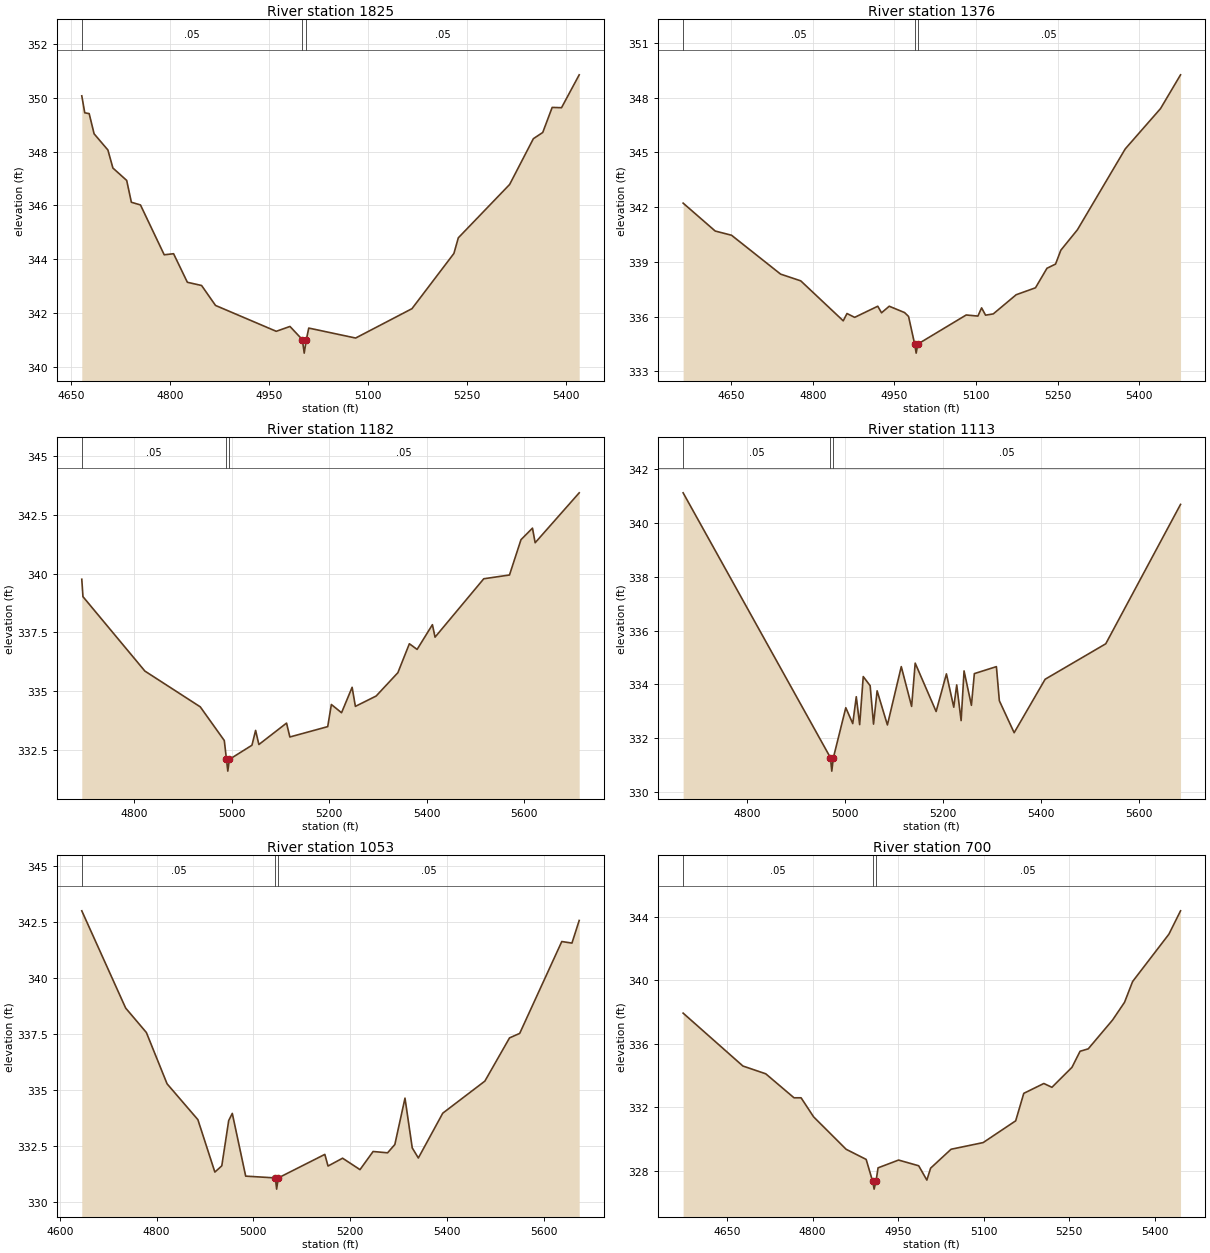
Type RM Length L Ch R = 1,1825,449,449,449
BEGIN DESCRIPTION:
UNT074 IN SUCR 3.0
END DESCRIPTION:
XS GIS Cut Line= 2
      2294568.05     13374460.39      2295066.22     13375026.77
#Sta/Elev= 30
  4665.8  350.07  4670.3  349.44  4677.0  349.41  4684.5  348.66  4705.4  348.06
  4713.0  347.39  4733.9  346.93  4741.0  346.12  4754.8  346.02  4790.8  344.17
  4805.0  344.21  4825.9  343.15  4847.5  343.03  4868.6  342.29  4960.7  341.33
  4981.5  341.51  5000.3  341.02  5003.1  340.52  5006.3  341.02  5010.0  341.45
  5081.1  341.08  5166.5  342.17  5230.1  344.22  5236.8  344.80  5314.6  346.78
  5350.6  348.48  5364.8  348.71  5379.1  349.64  5393.3  349.63  5420.1  350.85
#Mann=3,-1,0
  4665.8    0.05       0  5000.3    0.03       0  5006.3    0.05       0
Bank Sta=5000.3,5006.3
Exp/Cntr=0.3,0.1

Type RM Length L Ch R = 1,1376,194,194,194
BEGIN DESCRIPTION:
Mapping XS 15f08f02
END DESCRIPTION:
XS GIS Cut Line= 4
      2294342.72     13374667.96      2294354.58     13374869.61
      2294683.71     13375216.53      2294913.89     13375260.79
#Sta/Elev= 30
  4561.6  342.22  4620.6  340.69  4650.6  340.46  4740.8  338.33  4777.9  337.96
  4856.0  335.77  4862.9  336.17  4877.0  335.96  4919.5  336.57  4926.4  336.21
  4940.6  336.57  4968.9  336.22  4976.1  336.01  4987.3  334.50  4990.1  334.00
  4993.3  334.50  5082.1  336.09  5103.6  336.03  5110.4  336.48  5117.7  336.08
  5131.9  336.15  5174.0  337.20  5209.5  337.58  5230.6  338.65  5246.4  338.88
  5256.1  339.64  5286.6  340.76  5374.5  345.19  5439.4  347.40  5476.2  349.25
#Mann=3,-1,0
  4561.6    0.05       0  4987.3    0.03       0  4993.3    0.05       0
Bank Sta=4987.3,4993.3
Exp/Cntr=0.3,0.1

Type RM Length L Ch R = 1,1182,69,69,69
BEGIN DESCRIPTION:
Mapping XS 0dbf6c9d
END DESCRIPTION:
XS GIS Cut Line= 3
      2294161.89     13374979.35      2294618.48     13375388.51
      2294993.86     13375548.12
#Sta/Elev= 30
  4692.0  339.76  4694.4  339.02  4821.5  335.86  4935.2  334.34  4984.5  332.91
  4989.0  332.11  4991.7  331.61  4995.0  332.11  5041.3  332.71  5048.8  333.34
  5055.5  332.74  5112.3  333.65  5119.1  333.06  5196.8  333.50  5204.3  334.44
  5225.2  334.09  5246.9  335.17  5253.6  334.36  5296.2  334.80  5340.8  335.79
  5364.4  337.02  5380.3  336.78  5411.7  337.83  5417.1  337.30  5517.1  339.78
  5569.9  339.94  5593.5  341.44  5617.1  341.93  5622.6  341.31  5713.0  343.43
#Mann=3,-1,0
  4692.0    0.05       0  4989.0    0.03       0  4995.0    0.05       0
Bank Sta=4989,4995
Exp/Cntr=0.3,0.1

Type RM Length L Ch R = 1,1113,60,60,60
BEGIN DESCRIPTION:
UNT074 IN SUCR 2.0
END DESCRIPTION:
XS GIS Cut Line= 4
      2294120.35     13375014.91      2294485.05     13375361.82
      2294553.25     13375462.63      2294766.75     13375788.82
#Sta/Elev= 30
  4669.9  341.13  4970.5  331.27  4973.2  330.77  4976.5  331.27  5001.8  333.13
  5016.0  332.54  5023.2  333.54  5030.1  332.50  5037.4  334.29  5051.5  333.95
  5058.4  332.52  5065.7  333.76  5086.7  332.49  5115.0  334.66  5136.1  333.18
  5143.4  334.79  5186.1  332.99  5207.1  334.39  5222.1  333.15  5228.1  333.98
  5237.1  332.65  5243.1  334.50  5258.1  333.22  5264.1  334.40  5309.1  334.66
  5315.1  333.39  5345.3  332.20  5408.5  334.19  5532.2  335.51  5684.8  340.70
#Mann=3,-1,0
  4669.9    0.05       0  4970.5    0.03       0  4976.5    0.05       0
Bank Sta=4970.5,4976.5
Exp/Cntr=0.3,0.1

Type RM Length L Ch R = 1,1053,353,353,353
BEGIN DESCRIPTION:
Mapping XS f8055505
END DESCRIPTION:
XS GIS Cut Line= 3
      2294061.06     13375065.33      2294464.29     13375409.26
      2294742.01     13375822.88
#Sta/Elev= 30
  4645.5  343.01  4736.2  338.67  4779.0  337.58  4821.8  335.29  4885.5  333.69
  4920.6  331.35  4934.9  331.63  4949.2  333.65  4956.6  333.97  4984.3  331.17
  5045.6  331.09  5048.3  330.59  5051.6  331.09  5147.9  332.14  5154.5  331.62
  5184.6  331.97  5220.6  331.46  5247.7  332.27  5277.6  332.21  5292.6  332.58
  5313.6  334.65  5328.6  332.43  5341.2  331.98  5391.7  333.98  5478.7  335.41
  5529.7  337.34  5550.7  337.54  5637.7  341.64  5658.7  341.57  5673.7  342.58
#Mann=3,-1,0
  4645.5    0.05       0  5045.6    0.03       0  5051.6    0.05       0
Bank Sta=5045.6,5051.6
Exp/Cntr=0.3,0.1

Type RM Length L Ch R = 1,700,331,331,331
BEGIN DESCRIPTION:
Mapping XS 022b4252
END DESCRIPTION:
XS GIS Cut Line= 3
      2294069.93     13375252.10      2294081.79     13375450.77
      2294519.85     13375962.83
#Sta/Elev= 30
  4572.8  337.92  4677.7  334.59  4717.8  334.10  4767.4  332.59  4779.8  332.59
  4801.8  331.39  4858.8  329.35  4894.0  328.71  4905.3  327.34  4908.0  326.84
  4911.3  327.34  4914.9  328.18  4950.9  328.67  4986.2  328.31  5000.5  327.41
  5007.1  328.16  5043.0  329.35  5099.3  329.77  5156.4  331.14  5170.6  332.87
  5205.8  333.49  5220.0  333.25  5255.2  334.51  5269.4  335.52  5283.7  335.67
  5326.5  337.49  5347.4  338.60  5361.6  339.91  5425.3  342.89  5445.7  344.36
#Mann=3,-1,0
  4572.8    0.05       0  4905.3    0.03       0  4911.3    0.05       0
Bank Sta=4905.3,4911.3
Exp/Cntr=0.3,0.1

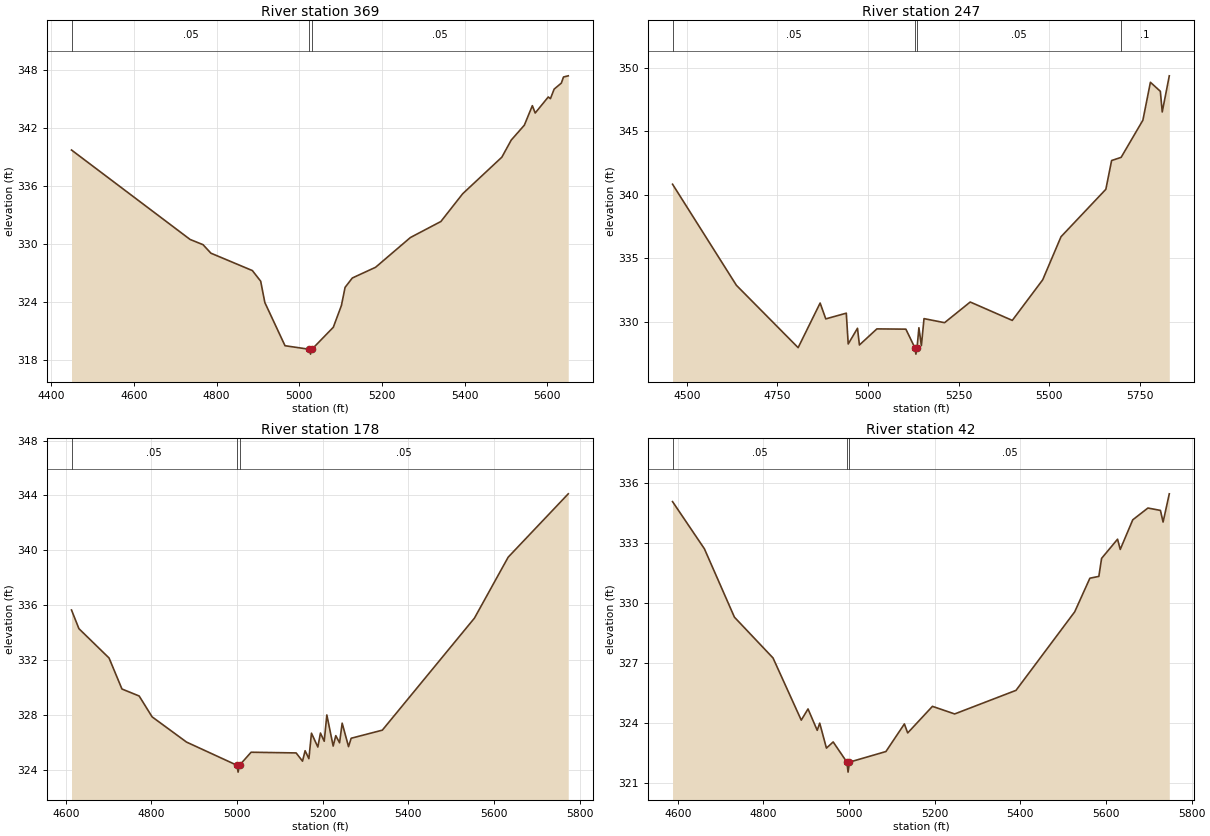
Type RM Length L Ch R = 1,369,122,122,122
BEGIN DESCRIPTION:
Mapping XS d801b225
END DESCRIPTION:
XS GIS Cut Line= 4
      2294013.26     13375241.09      2293957.70     13375810.53
      2293978.54     13375866.08      2294520.17     13376046.63
#Sta/Elev= 30
  4448.6  339.74  4735.7  330.48  4767.0  329.94  4786.0  329.06  4886.4  327.26
  4906.5  326.16  4916.6  323.95  4965.4  319.48  5024.5  319.11  5027.2  318.61
  5030.5  319.11  5082.3  321.39  5101.9  323.64  5110.8  325.52  5128.3  326.49
  5184.6  327.60  5268.9  330.68  5342.7  332.34  5395.4  335.21  5490.3  339.00
  5513.0  340.77  5544.7  342.31  5564.1  344.33  5571.0  343.57  5602.6  345.23
  5607.9  345.06  5616.8  346.04  5634.3  346.67  5639.5  347.30  5651.0  347.42
#Mann=3,-1,0
  4448.6    0.05       0  5024.5    0.03       0  5030.5    0.05       0
Bank Sta=5024.5,5030.5
Exp/Cntr=0.3,0.1

Type RM Length L Ch R = 1,247,69,69,69
BEGIN DESCRIPTION:
Mapping XS d638dccc
END DESCRIPTION:
XS GIS Cut Line= 6
      2293909.09     13375241.10      2293881.31     13375636.92
      2293839.65     13375754.97      2293839.65     13375907.75
      2293957.70     13376018.86      2294478.51     13376136.91
#Sta/Elev= 30
  4460.5  340.84  4636.7  332.87  4807.1  327.95  4867.8  331.47  4883.4  330.22
  4940.0  330.67  4945.3  328.24  4970.9  329.48  4976.2  328.16  5024.4  329.43
  5104.4  329.41  5129.3  327.94  5132.1  327.44  5135.3  327.94  5140.4  329.52
  5147.2  328.11  5154.5  330.24  5211.2  329.92  5282.0  331.55  5398.1  330.10
  5482.0  333.30  5532.6  336.70  5656.3  340.44  5672.2  342.71  5698.5  342.96
  5758.5  345.89  5779.3  348.88  5806.7  348.17  5811.9  346.54  5831.4  349.39
#Mann=4,-1,0
  4460.5    0.05       0  5129.3    0.03       0  5135.3    0.05       0
  5698.5     0.1       0
Bank Sta=5129.3,5135.3
Exp/Cntr=0.3,0.1

Type RM Length L Ch R = 1,178,136,136,136
BEGIN DESCRIPTION:
Mapping XS 2d93ba68
END DESCRIPTION:
XS GIS Cut Line= 4
      2293731.91     13375379.64      2293779.35     13375842.17
      2293951.33     13376091.24      2294327.93     13376200.96
#Sta/Elev= 30
  4613.3  335.65  4630.6  334.29  4701.0  332.15  4731.1  329.89  4771.3  329.38
  4801.5  327.86  4881.9  326.02  4999.6  324.33  5002.3  323.83  5005.6  324.33
  5032.7  325.28  5137.8  325.23  5152.7  324.63  5158.8  325.39  5167.6  324.81
  5173.6  326.67  5188.5  325.66  5194.6  326.68  5203.4  326.08  5209.5  328.00
  5224.3  325.73  5230.4  326.49  5239.2  325.97  5245.3  327.40  5260.2  325.69
  5266.3  326.30  5339.1  326.89  5554.2  335.06  5632.9  339.50  5773.2  344.12
#Mann=3,-1,0
  4613.3    0.05       0  4999.6    0.03       0  5005.6    0.05       0
Bank Sta=4999.6,5005.6
Exp/Cntr=0.3,0.1

Type RM Length L Ch R = 1,42,0,0,0
BEGIN DESCRIPTION:
UNT074 IN SUCR 1.0
END DESCRIPTION:
XS GIS Cut Line= 4
      2293565.86     13375382.53      2293580.69     13375679.09
      2293779.35     13376020.08      2294154.29     13376300.55
#Sta/Elev= 30
  4588.0  335.09  4662.4  332.73  4732.5  329.31  4822.6  327.27  4888.5  324.16
  4904.3  324.72  4925.8  323.65  4931.6  324.01  4947.3  322.76  4963.0  323.07
  4995.1  322.06  4997.8  321.56  5001.1  322.06  5086.2  322.59  5129.3  323.97
  5137.0  323.52  5194.8  324.85  5246.7  324.47  5389.9  325.65  5527.0  329.58
  5562.4  331.26  5583.3  331.35  5589.7  332.25  5627.0  333.21  5633.3  332.70
  5662.5  334.18  5697.9  334.77  5727.1  334.65  5733.3  334.07  5747.8  335.48
#Mann=3,-1,0
  4588.0    0.05       0  4995.1    0.03       0  5001.1    0.05       0
Bank Sta=4995.1,5001.1
Exp/Cntr=0.3,0.1

Chan Stop Cuts=-1