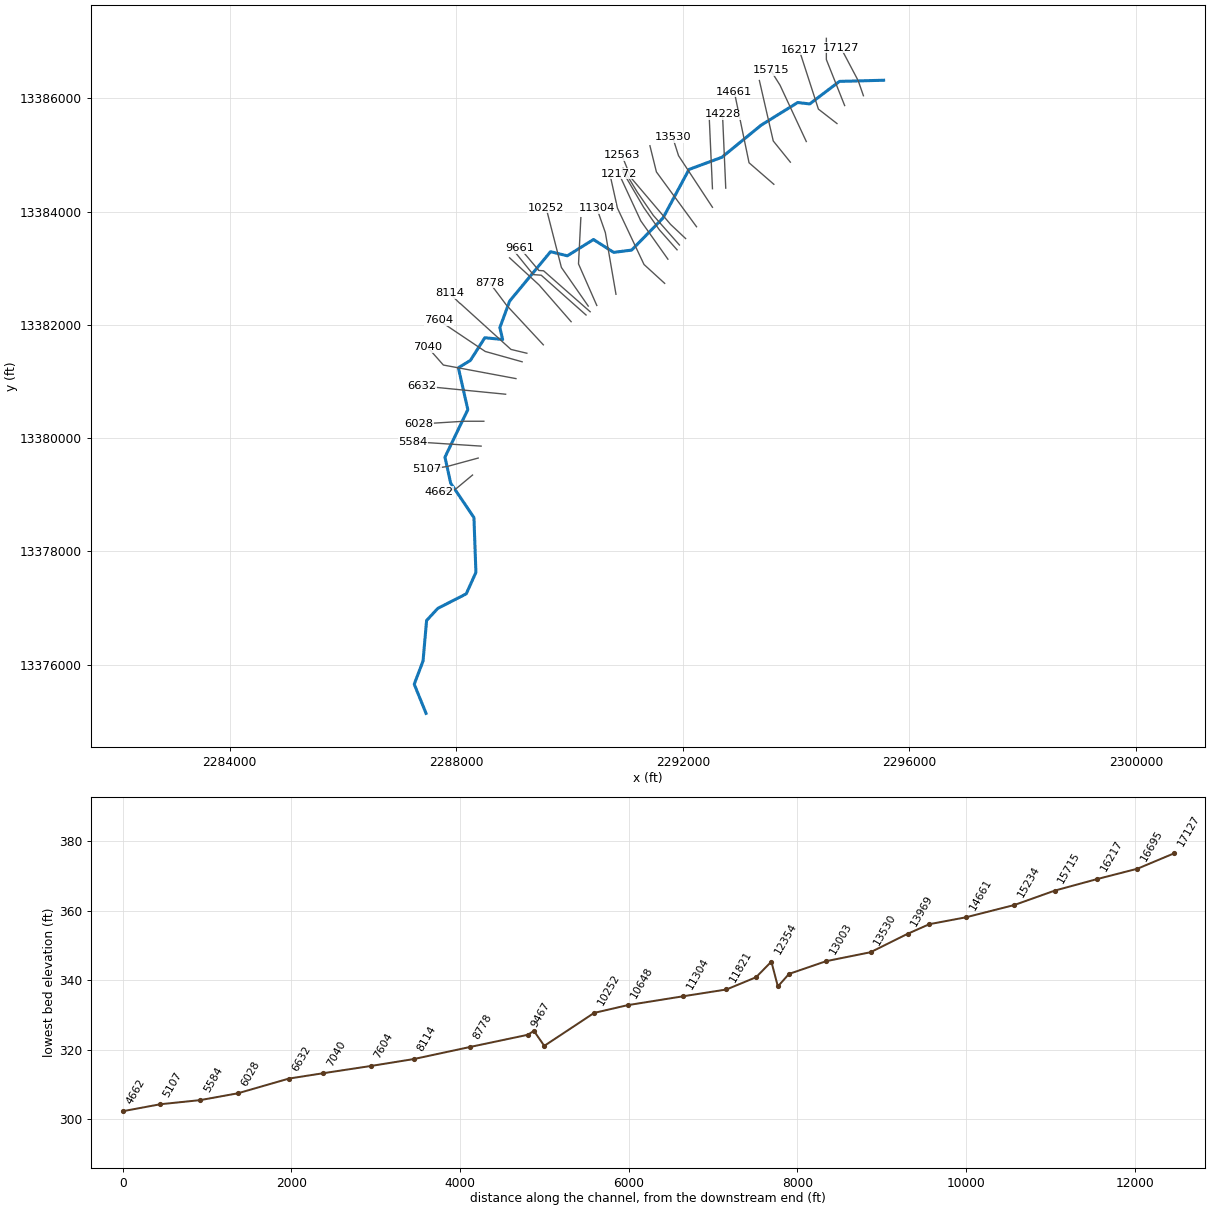
--- UNT075 IN SUCR.prj (project) ---

Proj Title=UNT075 IN SUCR Base Level Engineering
Current Plan=p01
Default Exp/Contr=0.3,0.1
English Units
Geom File=g01
Flow File=f01
Plan File=p01
Y Axis Title=Elevation
X Axis Title(PF)=Main Channel Distance
X Axis Title(XS)=Station
BEGIN DESCRIPTION:
UNT075 IN SUCR
END DESCRIPTION:
DSS Export Rating Curves= 0
DSS Export Rating Curve Sorted= 0
DSS Export Volume Flow Curves= 0
DXF OffsetX= 0
DXF OffsetY= 0
DXF ScaleX= 1
DXF ScaleY= 10

--- UNT075 IN SUCR.p01 (plan) ---

Plan Title=Multiple Run
Short Identifier=Multiple
Geom File=g01
Flow File=f01
Subcritical Flow
K Sum by GR= 0
Std Step Tol= 0.01
Critical Tol= 0.01
Num of Std Step Trials= 20
Max Error Tol= 0.3
Flow Tol Ratio= 0.001
Split Flow NTrial= 30
Split Flow Tol= 0.02
Split Flow Ratio= 0.02
Log Output Level= 0
Friction Slope Method= 1
Unsteady Friction Slope Method= 2
Unsteady Bridges Friction Slope Method= 1
Parabolic Critical Depth
Global Vel Dist=  1 , 1 , 1
Global Log Level= 0
CheckData=True
Encroach Param= -1, 0, 0, 0
BEGIN DESCRIPTION:
Multiple Run
END DESCRIPTION:

--- UNT075 IN SUCR.f01 (steady flow) ---

Flow Title=Multiple
Program Version=4.10
Number of Profiles= 7
Profile Names=10-year,25-year,50-year,1pct_min,100-year,1pct_plu,500-year
River Rch & RM=UNT075 IN SUCR,Reach-1         ,17127
     663     948    1189    1090    1475    1994    2277
River Rch & RM=UNT075 IN SUCR,Reach-1         ,14661
     682     976    1226    1124    1520    2056    2347
River Rch & RM=UNT075 IN SUCR,Reach-1         ,13969
     769    1105    1392    1279    1730    2340    2686
River Rch & RM=UNT075 IN SUCR,Reach-1         ,10252
     876    1272    1612    1492    2018    2729    3188
River Rch & RM=UNT075 IN SUCR,Reach-1         ,9661
     876    1272    1612    1492    2018    2729    3188
Boundary for River Rch & Prof#=UNT075 IN SUCR,Reach-1         , 1
Up Type= 0
Dn Type= 3
Dn Slope=0.01
Boundary for River Rch & Prof#=UNT075 IN SUCR,Reach-1         , 2
Up Type= 0
Dn Type= 3
Dn Slope=0.01
Boundary for River Rch & Prof#=UNT075 IN SUCR,Reach-1         , 3
Up Type= 0
Dn Type= 3
Dn Slope=0.01
Boundary for River Rch & Prof#=UNT075 IN SUCR,Reach-1         , 4
Up Type= 0
Dn Type= 3
Dn Slope=0.01
Boundary for River Rch & Prof#=UNT075 IN SUCR,Reach-1         , 5
Up Type= 0
Dn Type= 3
Dn Slope=0.01
Boundary for River Rch & Prof#=UNT075 IN SUCR,Reach-1         , 6
Up Type= 0
Dn Type= 3
Dn Slope=0.01
Boundary for River Rch & Prof#=UNT075 IN SUCR,Reach-1         , 7
Up Type= 0
Dn Type= 3
Dn Slope=0.01
DSS Import GetInterval= 0
DSS Import GetPeak= 0
DSS Import FillOption= 0

--- UNT075 IN SUCR.g01 (geometry) ---

Geom Title=Existing Conditions
Program Version=4.10

River Reach=UNT075 IN SUCR  ,Reach-1
Reach XY= 30
      2295544.09      13386320.3      2294764.98     13386300.31
      2294240.02     13385902.16      2294027.72     13385926.85
      2293384.02     13385528.23      2292689.12     13384959.82
      2292108.63     13384744.41      2291649.84     13383886.69
      2291096.35     13383320.21      2290778.94     13383279.77
      2290422.69     13383507.23      2289961.72     13383219.26
      2289664.78     13383291.76      2288942.91     13382419.48
       2288770.1     13381950.98      2288819.58     13381740.62
      2288505.08     13381772.14      2288249.88     13381371.04
      2288037.94     13381241.87       2288204.9     13380502.42
      2287801.24     13379662.22      2287902.15     13379203.98
      2288312.69     13378595.96      2288347.65     13377626.52
      2288176.77     13377247.97      2287675.09     13376991.84
      2287476.93      13376777.2      2287414.38     13376061.78
      2287258.79     13375651.89      2287467.72     13375136.85

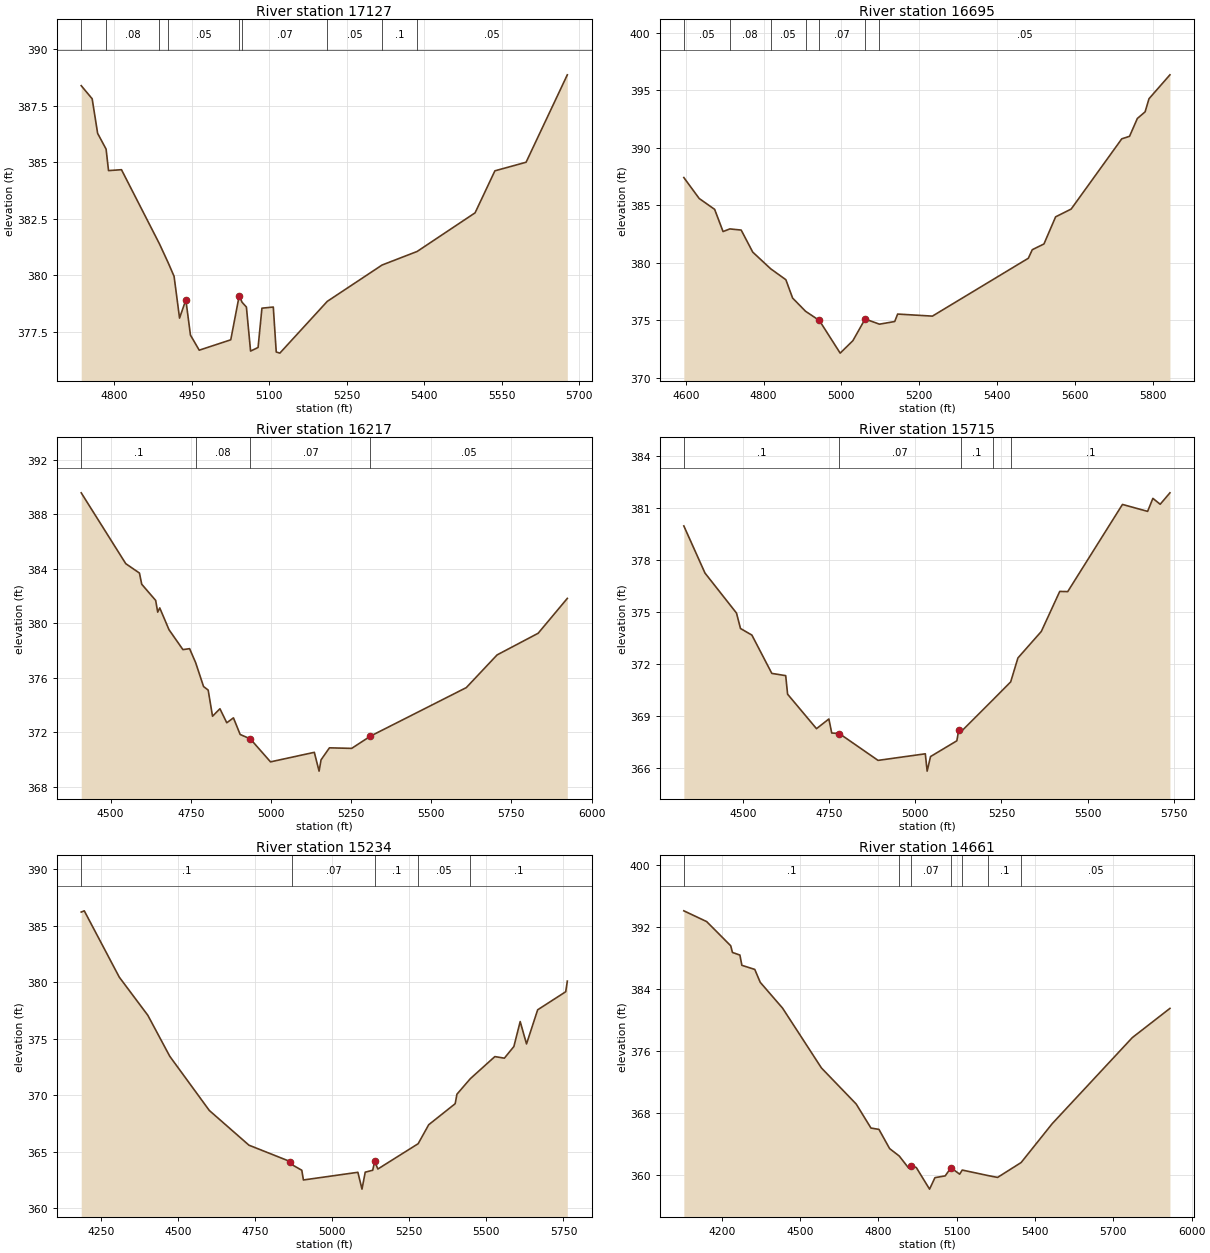
Type RM Length L Ch R = 1 ,17127   ,432,432,432
BEGIN DESCRIPTION:
UNT075 IN SUCR 35.0
END DESCRIPTION:
XS GIS Cut Line= 3
      2295187.72     13386046.84      2295096.35     13386311.32
      2294787.73     13386896.85
#Sta/Elev= 30
  4735.7  388.39  4756.9  387.81  4767.5  386.28  4783.9  385.58  4788.6  384.63
  4813.7  384.67  4887.2  381.39  4904.2  380.55  4915.6  379.95  4926.2   378.1
  4938.4  378.91  4947.3  377.35  4964.3  376.68  5025.4  377.14  5041.7  379.08
  5047.4   378.8  5055.7  378.59  5063.8  376.64  5078.3   376.8  5085.8  378.54
  5107.8  378.59  5113.5   376.6  5120.5  376.55  5212.3  378.84  5318.5  380.45
  5386.4  381.05  5498.7  382.76  5537.1  384.62  5597.5     385  5677.4  388.87
#Mann= 9 ,-1 , 0
  4735.7     .05       0  4783.9     .08       0  4887.2     .12       0
  4904.2     .05       0  5041.7     .12       0  5047.4     .07       0
  5212.3     .05       0  5318.5      .1       0  5386.4     .05       0
Bank Sta=4938.4,5041.7
XS Rating Curve= 0 ,0
Exp/Cntr=0.3,0.1

Type RM Length L Ch R = 1 ,16695   ,478,478,478
BEGIN DESCRIPTION:
UNT075 IN SUCR 34.0
END DESCRIPTION:
XS GIS Cut Line= 3
      2294856.49     13385873.21      2294533.58     13386685.71
      2294533.58     13387060.69
#Sta/Elev= 30
  4595.2  387.42  4634.6   385.6  4674.4  384.65    4696  382.72  4713.4  382.95
  4742.6  382.85  4772.3  380.93  4818.4  379.48  4857.4  378.53  4874.8  376.93
  4908.1  375.78  4943.5  374.98    4997  372.14  5029.6  373.22  5061.1  375.11
    5098  374.66  5137.2  374.89  5144.7  375.54    5234  375.36  5480.7   380.4
  5490.7  381.14  5520.7  381.64  5550.7     384  5590.7  384.68  5720.7  390.79
  5740.7  391.01  5760.7  392.56  5780.7  393.14  5790.7  394.28  5844.5  396.36
#Mann= 7 ,-1 , 0
  4595.2     .05       0  4713.4     .08       0  4818.4     .05       0
  4908.1     .12       0  4943.5     .07       0  5061.1     .12       0
    5098     .05       0
Bank Sta=4943.5,5061.1
XS Rating Curve= 0 ,0
Exp/Cntr=0.3,0.1

Type RM Length L Ch R = 1 ,16217   ,502,502,502
BEGIN DESCRIPTION:
UNT075 IN SUCR 33.0
END DESCRIPTION:
XS GIS Cut Line= 3
      2294721.06     13385555.51      2294392.95     13385810.71
      2294054.42     13386857.56
#Sta/Elev= 30
  4408.4  389.59  4547.3  384.39    4590   383.7  4597.1  382.88  4640.6  381.69
  4646.9  380.83  4653.3  381.14  4682.2  379.54  4725.6  378.08  4746.4  378.15
  4765.3  377.12  4789.9  375.37  4804.3  375.11  4817.9  373.19    4841  373.74
  4862.3  372.71  4883.1  373.07  4904.1  371.85  4935.6  371.53  4998.7  369.84
  5135.3  370.54  5150.2  369.16  5156.3  369.99  5182.5  370.87  5251.8  370.83
  5310.5  371.73  5609.2  375.29  5705.2  377.69  5833.3  379.28  5924.3  381.84
#Mann= 4 ,-1 , 0
  4408.4      .1       0  4765.3     .08       0  4935.6     .07       0
  5310.5     .05       0
Bank Sta=4935.6,5310.5
XS Rating Curve= 0 ,0
Exp/Cntr=0.3,0.1

Type RM Length L Ch R = 1 ,15715   ,481,481,481
BEGIN DESCRIPTION:
UNT075 IN SUCR 32.0
END DESCRIPTION:
XS GIS Cut Line= 3
      2294179.42     13385237.77      2293715.87     13386232.58
       2293549.2     13386498.21
#Sta/Elev= 30
  4328.2  379.99  4389.6  377.27  4481.1  374.96  4492.7  374.07  4525.8  373.69
  4583.6  371.48  4623.9  371.35  4629.4  370.28  4713.3  368.29  4749.3  368.85
  4757.5  368.04  4779.5  368.01    4892  366.46  5029.2  366.84  5034.5  365.84
  5044.3  366.68  5120.7  367.59  5126.2  368.21  5132.6  368.11  5226.2  369.97
    5277  370.99    5298  372.37  5365.9   373.9  5419.4  376.21  5442.6   376.2
  5601.5  381.23  5674.5  380.83  5689.8  381.58    5711  381.24  5739.3   381.9
#Mann= 5 ,-1 , 0
  4328.2      .1       0  4779.5     .07       0  5132.6      .1       0
  5226.2     .05       0    5277      .1       0
Bank Sta=4779.5,5126.2
XS Rating Curve= 0 ,0
Exp/Cntr=0.3,0.1

Type RM Length L Ch R = 1 ,15234   ,573,573,573
BEGIN DESCRIPTION:
UNT075 IN SUCR 31.0
END DESCRIPTION:
XS GIS Cut Line= 3
      2293898.16     13384873.21      2293596.08     13385248.21
       2293351.3     13386315.87
#Sta/Elev= 30
  4185.7   386.2  4195.6  386.31  4309.2  380.44  4401.9  377.06  4472.9  373.44
  4601.3  368.64  4729.8  365.57  4863.6  364.12    4871  363.82  4901.3  363.35
  4906.5  362.49  5083.2  363.17  5096.5  361.68    5107  363.18  5131.2  363.35
  5137.8  364.13    5148  363.46  5278.7   365.7    5313  367.38  5398.8  369.24
  5404.5  370.08  5447.8  371.45  5527.5  373.41  5558.4  373.27  5589.2   374.3
  5609.7  376.51  5630.2  374.53  5666.4  377.55  5757.4  379.15  5762.6  380.09
#Mann= 5 ,-1 , 0
  4185.7      .1       0    4871     .07       0  5137.8      .1       0
  5278.7     .05       0  5447.8      .1       0
Bank Sta=4863.6,5137.8
XS Rating Curve= 0 ,0
Exp/Cntr=0.3,0.1

Type RM Length L Ch R = 1 ,14661   ,433,433,433
BEGIN DESCRIPTION:
UNT075 IN SUCR 30.0
END DESCRIPTION:
XS GIS Cut Line= 3
      2293606.52     13384482.56      2293168.99     13384862.79
      2292908.58       13386118.
#Sta/Elev= 30
  4055.2  394.06  4142.7  392.67  4234.8  389.55  4241.4  388.69  4269.9  388.35
  4277.5  387.03  4326.9   386.5  4347.7  384.84  4433.2  381.51  4582.3  373.78
  4715.3  369.13  4771.8  366.03  4802.4  365.86  4843.3  363.38  4880.2  362.42
  4915.9  360.88    4925  361.17  4945.4  360.94  4996.2  358.15  5016.9  359.63
  5056.1  359.86  5078.2  360.91  5111.4  360.08  5121.5  360.61  5221.7  359.89
  5256.7  359.66  5346.9  361.58  5466.3  366.61  5772.7   377.7  5916.8  381.47
#Mann= 7 ,-1 , 0
  4055.2      .1       0  4880.2     .12       0    4925     .07       0
  5078.2     .12       0  5121.5     .08       0  5221.7      .1       0
  5346.9     .05       0
Bank Sta=4925,5078.2
XS Rating Curve= 0 ,0
Exp/Cntr=0.3,0.1

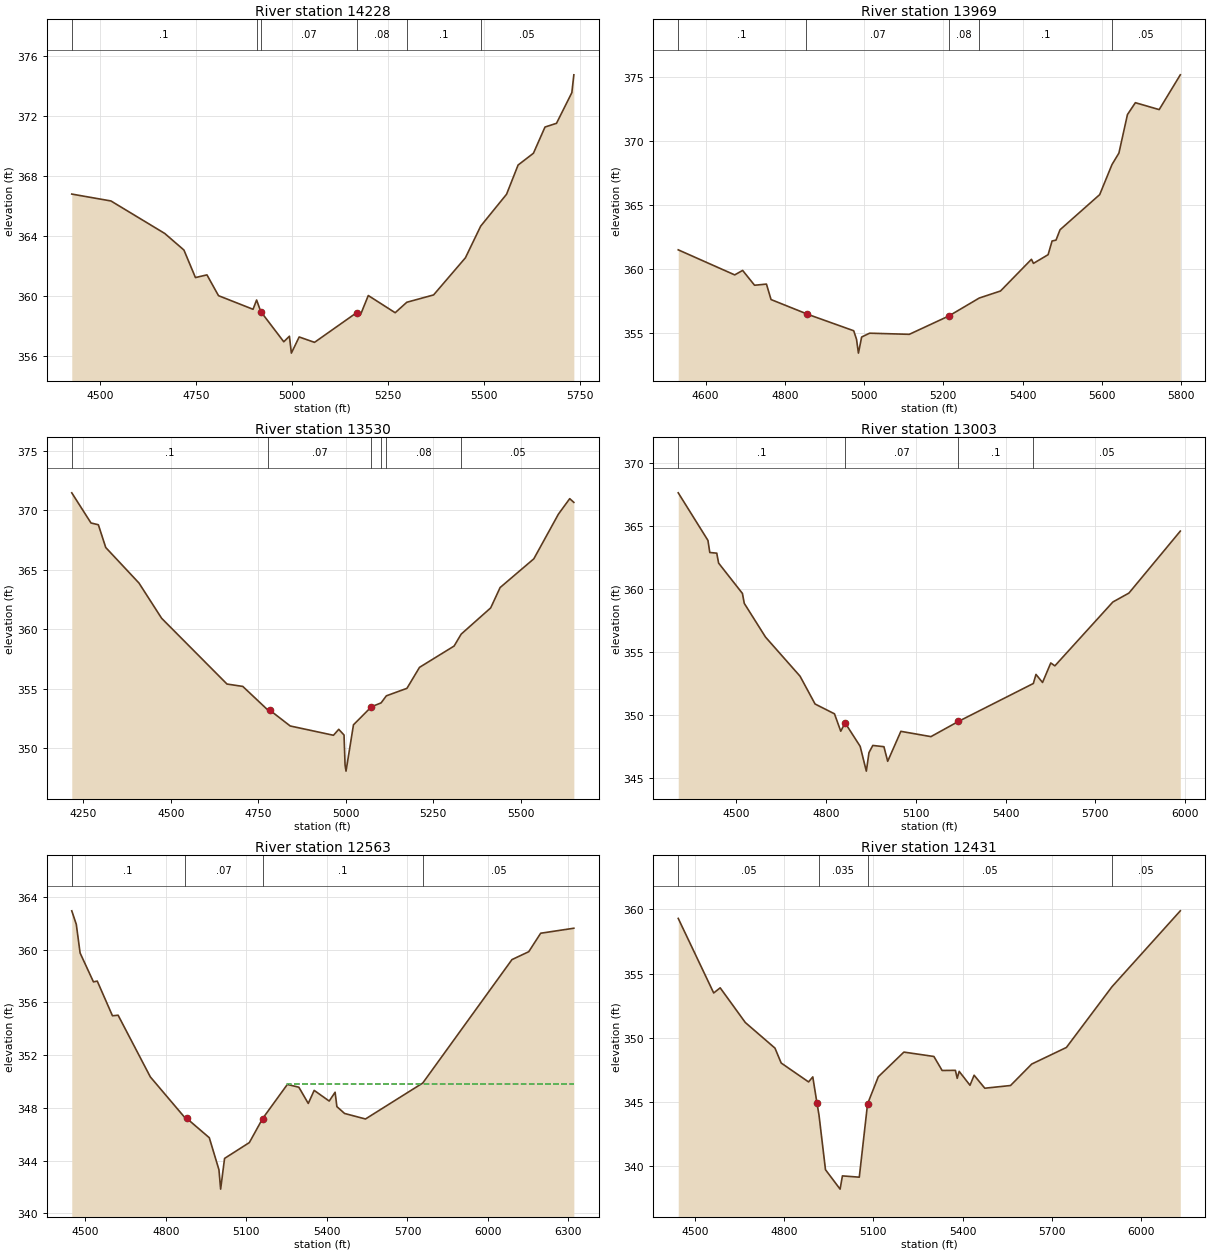
Type RM Length L Ch R = 1 ,14228   ,259,259,259
BEGIN DESCRIPTION:
UNT075 IN SUCR 29.0
END DESCRIPTION:
XS GIS Cut Line= 2
      2292757.54     13384414.87      2292700.25     13385722.01
#Sta/Elev= 30
  4425.3   366.8  4527.4  366.34  4667.5  364.17  4717.6  363.06  4747.6  361.22
  4777.6   361.4  4807.7  360.01  4897.7   359.1    4907  359.72  4917.8  358.95
  4977.8  356.93  4992.5   357.3  4997.6  356.17  5017.9  357.25  5057.9  356.89
    5168  358.88    5178  358.75    5198  360.02  5268.1  358.87  5298.4  359.57
  5368.2  360.06  5451.1  362.54    5491  364.66  5558.4  366.79  5588.4  368.74
  5628.4  369.53  5658.5  371.28  5688.5  371.53  5728.5  373.58  5733.7  374.77
#Mann= 6 ,-1 , 0
  4425.3      .1       0    4907     .12       0  4917.8     .07       0
    5168     .08       0  5298.4      .1       0    5491     .05       0
Bank Sta=4917.8,5168
XS Rating Curve= 0 ,0
Exp/Cntr=0.3,0.1

Type RM Length L Ch R = 1 ,13969   ,439,439,439
BEGIN DESCRIPTION:
UNT075 IN SUCR 28.0
END DESCRIPTION:
XS GIS Cut Line= 2
      2292523.16     13384404.49      2292465.87     13385670.09
#Sta/Elev= 30
  4531.1  361.47  4673.6  359.51  4693.6  359.86  4723.7   358.7  4753.7  358.79
  4765.3  357.58  4853.8  356.48  4854.8  356.46  4973.9  355.14    4981  354.47
  4985.8  353.39  4993.9  354.65    5014  354.95  5114.1  354.86  5214.2   356.3
  5290.7   357.7  5344.3  358.25  5422.4  360.73  5427.4  360.41  5464.4  361.09
  5474.4  362.16  5484.4  362.23  5494.5  363.04  5594.6  365.79  5625.6  368.14
  5643.1  369.04  5664.6  372.05  5684.6  372.98  5744.7  372.44    5798  375.16
#Mann= 5 ,-1 , 0
  4531.1      .1       0  4853.8     .07       0  5214.2     .08       0
  5290.7      .1       0  5625.6     .05       0
Bank Sta=4854.8,5214.2
XS Rating Curve= 0 ,0
Exp/Cntr=0.3,0.1

Type RM Length L Ch R = 1 ,13530   ,527,527,527
BEGIN DESCRIPTION:
UNT075 IN SUCR 27.0
END DESCRIPTION:
XS GIS Cut Line= 3
      2292523.14     13384076.36       2291924.2     13384987.79
      2291820.03     13385315.94
#Sta/Elev= 30
  4216.8  371.45  4271.7  368.92  4292.8  368.77  4313.9  366.86  4408.8  363.88
  4473.6  360.92  4660.4   355.4  4705.6   355.2  4777.9   353.2  4783.9  353.18
  4841.1  351.88  4964.7   351.1  4979.8   351.6  4994.9  351.12  4997.9  348.59
  5000.6  348.09  5021.9  351.98  5073.2  353.49  5100.9  353.82  5115.8  354.41
  5174.7  355.04  5210.6   356.8  5309.5  358.59  5329.7  359.59    5414  361.79
    5441   363.5  5537.3  365.91  5607.6  369.66  5639.9  370.96  5651.7  370.65
#Mann= 6 ,-1 , 0
  4216.8      .1       0  4777.9     .07       0  5073.2     .12       0
  5100.9      .1       0  5115.8     .08       0  5329.7     .05       0
Bank Sta=4783.9,5073.2
XS Rating Curve= 0 ,0
Exp/Cntr=0.3,0.1

Type RM Length L Ch R = 1 ,13003   ,440,440,440
BEGIN DESCRIPTION:
UNT075 IN SUCR 26.0
END DESCRIPTION:
XS GIS Cut Line= 3
      2292241.91     13383732.59      2291533.58     13384701.33
      2291419.37     13385163.34
#Sta/Elev= 30
  4307.4  367.61  4406.6  363.83  4412.8  362.87    4436  362.82  4442.2  362.03
  4521.7  359.62  4527.9  358.83  4598.9  356.15    4714  353.05  4764.2  350.84
    4829  350.06  4849.9  348.68  4864.5  349.34  4914.7  347.48  4935.3  345.51
  4944.1  346.98  4956.9  347.55    4994  347.45  5006.6  346.29  5050.6  348.67
    5151  348.25  5242.9  349.46  5492.8  352.47  5501.6  353.19  5523.5  352.55
    5551   354.1  5564.7  353.87  5758.2  358.94  5811.9  359.65  5983.4  364.57
#Mann= 4 ,-1 , 0
  4307.4      .1       0  4864.5     .07       0  5242.9      .1       0
  5492.8     .05       0
Bank Sta=4864.5,5242.9
XS Rating Curve= 0 ,0
Exp/Cntr=0.3,0.1

Type RM Length L Ch R = 1 ,12563   ,132,132,132
BEGIN DESCRIPTION:
UNT075 IN SUCR 25.0
END DESCRIPTION:
XS GIS Cut Line= 4
      2292049.22     13383524.23      2291783.58     13383774.25
      2291085.66     13384597.17      2290924.43     13384992.44
#Sta/Elev= 30
  4449.3  362.95  4466.2  361.92  4480.4  359.75  4530.1  357.56  4544.3  357.62
  4600.9  354.99    4622  355.03  4742.1  350.35    4870  347.28  4876.9  347.22
  4961.7  345.74  4997.7  343.31    5004  341.84  5018.6  344.17  5110.9  345.37
  5160.3  347.19  5252.5  349.78  5295.4  349.57  5330.5  348.34  5352.5  349.33
  5408.5  348.52  5430.5  349.19  5437.1   348.1  5465.7  347.58  5543.6  347.16
  5757.2  349.89  6089.4  359.25    6152  359.85  6196.4  361.25    6320  361.63
#Mann= 4 ,-1 , 0
  4449.3      .1       0    4870     .07       0  5160.3      .1       0
  5757.2     .05       0
#XS Ineff= 2 , 0
       0                 5252.23       0   349.8
Permanent Ineff=
       F       T
Bank Sta=4876.9,5160.3
XS Rating Curve= 0 ,0
Exp/Cntr=0.3,0.1

Type RM Length L Ch R = 1 ,12431   ,77,77,77
XS GIS Cut Line= 5
      2291939.72     13383410.34      2291478.88     13383933.22
      2291198.23      13384340.9      2291047.56     13384589.06
      2290944.19     13384766.27
#Sta/Elev= 30
    4444  359.29  4563.2  353.49    4585  353.89  4669.5  351.19  4769.1   349.2
    4790  348.04    4882  346.57  4896.2  346.96  4910.4  344.91  4917.1  343.99
  4938.9  339.74    4988  338.23  4995.8  339.26  5052.5  339.16  5080.3  344.86
  5116.3  346.97  5202.4  348.89  5303.2  348.55  5330.9  347.46  5375.5  347.47
  5381.6  346.85  5388.2  347.39  5424.6  346.31  5438.4  347.09  5474.3  346.08
  5560.8  346.29    5632  347.96  5748.5  349.25  5901.6  353.97  6131.4  359.88
#Mann= 4 ,-1 , 0
    4444     .05       0  4917.1    .035       0  5080.3     .05       0
  5901.6     .05       0
Bank Sta=4910.4,5080.3
XS Rating Curve= 0 ,0
Exp/Cntr=0.3,0.1

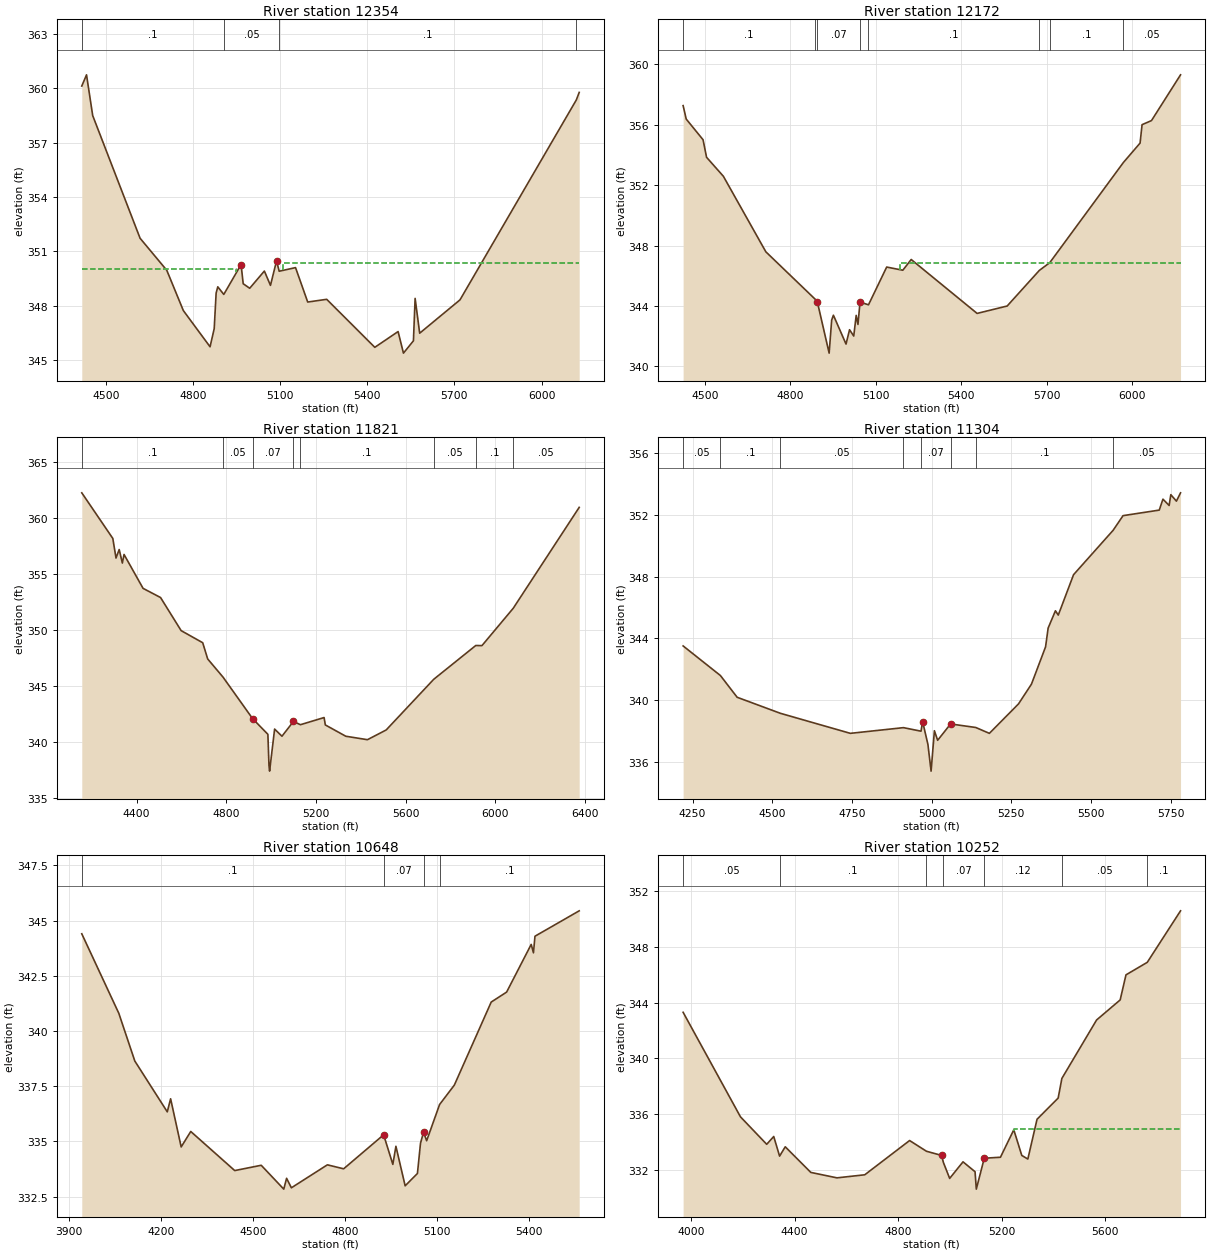
Type RM Length L Ch R = 1 ,12354   ,182,182,182
XS GIS Cut Line= 4
      2291898.41     13383324.61      2291585.23     13383679.15
      2291310.49     13384072.07      2290926.45     13384727.89
#Sta/Elev= 30
  4417.3  360.12  4433.6  360.74  4454.9  358.49    4618  351.72    4710  349.95
  4766.9  347.73  4858.9  345.73  4873.2  346.73  4879.8  348.69  4885.5  349.04
  4906.2  348.62  4965.7  350.27    4973  349.21  4995.4  348.96  5045.9  349.91
  5066.9  349.12  5087.8  350.47  5096.9   349.9  5153.2   350.1  5195.1   348.2
  5260.5  348.35  5426.1   345.7  5506.3  346.57  5524.7  345.38  5559.1  346.06
  5564.9   348.4  5580.6  346.48  5719.4  348.32  6120.1  359.36  6129.8  359.77
#Mann= 4 ,-1 , 0
  4417.3      .1       0  4906.2     .05       0  5096.9      .1       0
  6120.1     .05       0
#XS Ineff= 2 , 0
       0 4949.85  350.05 5111.46       0  350.33
Permanent Ineff=
       T       T
Bank Sta=4965.7,5087.8
XS Rating Curve= 0 ,0
Exp/Cntr=0.3,0.1

Type RM Length L Ch R = 1 ,12172   ,351,351,351
BEGIN DESCRIPTION:
UNT075 IN SUCR 24.0
END DESCRIPTION:
XS GIS Cut Line= 3
      2291736.67     13383159.71      2291257.54     13383836.75
       2290872.4     13384669.47
#Sta/Elev= 30
    4423  357.27  4433.9  356.38    4493  355.01  4505.3  353.85  4564.4  352.59
  4713.5  347.59  4886.2  344.46  4894.2  344.29  4935.8  340.88  4944.7  343.07
  4950.8  343.39  4995.1  341.48  5007.5  342.43  5022.2  342.01  5030.8  343.38
    5037  342.78  5044.3  344.26    5074  344.08  5137.9  346.58  5194.5  346.37
    5224  347.08  5455.4  343.51    5561     344  5674.1  346.36  5710.6  346.87
    5969   353.5  6027.8  354.79  6034.8  356.01  6067.9  356.28  6169.9  359.31
#Mann= 8 ,-1 , 0
    4423      .1       0  4886.2     .12       0  4894.2     .07       0
  5044.3     .12       0    5074      .1       0  5674.1     .05       0
  5710.6      .1       0    5969     .05       0
#XS Ineff= 2 , 0
       0                 5184.29       0  346.85
Permanent Ineff=
       F       T
Bank Sta=4894.2,5044.3
XS Rating Curve= 0 ,0
Exp/Cntr=0.3,0.1

Type RM Length L Ch R = 1 ,11821   ,517,517,517
BEGIN DESCRIPTION:
UNT075 IN SUCR 23.0
END DESCRIPTION:
XS GIS Cut Line= 4
      2291679.38     13382732.61      2291314.83     13383065.92
      2290846.08     13384060.71      2290710.66     13384670.09
#Sta/Elev= 30
  4155.9  362.24  4294.3  358.16  4308.5  356.41  4322.7  357.17  4336.8  355.96
  4344.3  356.73  4429.1   353.7  4507.1  352.88  4598.9  349.92  4695.1  348.84
  4717.2  347.39  4785.8  345.76  4917.3  342.06  4985.7  340.65  4990.6  337.86
  4993.3  337.36  5015.7  341.12  5048.5  340.48  5099.6   341.8  5130.9  341.51
  5236.3  342.15  5241.8  341.49  5332.9  340.48  5429.6  340.17  5513.2  341.04
  5725.2  345.57  5912.6  348.59  5940.2  348.58  6079.7  351.92  6373.8  360.94
#Mann= 8 ,-1 , 0
  4155.9      .1       0  4785.8     .05       0  4917.3     .07       0
  5099.6     .12       0  5130.9      .1       0  5725.2     .05       0
  5912.6      .1       0  6079.7     .05       0
Bank Sta=4917.3,5099.6
XS Rating Curve= 0 ,0
Exp/Cntr=0.3,0.1

Type RM Length L Ch R = 1 ,11304   ,656,656,656
BEGIN DESCRIPTION:
UNT075 IN SUCR 22.0
END DESCRIPTION:
XS GIS Cut Line= 3
      2290820.04     13382539.86      2290632.54     13383628.42
      2290482.09       13384059.
#Sta/Elev= 30
  4220.5  343.51  4337.5  341.59    4390  340.18  4525.7  339.14  4745.1  337.84
  4911.9  338.21  4966.9  337.98    4972   338.6  4988.6  337.12  4998.5  335.39
  5008.9  338.01  5019.1  337.39  5059.7  338.45  5138.7  338.22  5181.4  337.84
  5272.8  339.75  5313.4  341.03  5357.7  343.45  5365.8  344.67  5388.7  345.79
  5397.6  345.51  5445.5  348.13  5569.7  351.01  5600.8  351.96  5714.4  352.32
    5726  353.03  5745.4  352.62  5750.7  353.32  5768.3   352.9  5781.2  353.44
#Mann= 8 ,-1 , 0
  4220.5     .05       0  4337.5      .1       0  4525.7     .05       0
  4911.9     .12       0  4966.9     .07       0  5059.7     .12       0
  5138.7      .1       0  5569.7     .05       0
Bank Sta=4972,5059.7
XS Rating Curve= 0 ,0
Exp/Cntr=0.3,0.1

Type RM Length L Ch R = 1 ,10648   ,396,396,396
BEGIN DESCRIPTION:
UNT075 IN SUCR 21.0
END DESCRIPTION:
XS GIS Cut Line= 3
      2290481.48     13382341.99      2290158.58     13383076.33
      2290200.19     13383892.97
#Sta/Elev= 30
    3943   344.4  4063.6   340.8  4115.7  338.64  4221.4  336.34  4232.3  336.93
  4266.7  334.75  4297.9  335.45  4441.1  333.68  4527.3  333.92  4600.8  332.84
    4610  333.33  4625.6   332.9  4742.8  333.94  4795.8  333.76    4926   335.3
    4956  333.96    4966  334.78  4996.1  332.99  5036.1  333.55  5046.1  334.92
  5056.1  335.42  5066.1  335.03  5108.2  336.67  5156.3  337.55  5276.4  341.31
  5326.5  341.76  5406.6  343.92  5413.9  343.54  5418.9  344.29  5562.9  345.44
#Mann= 4 ,-1 , 0
    3943      .1       0    4926     .07       0  5056.1     .12       0
  5108.2      .1       0
Bank Sta=4926,5056.1
XS Rating Curve= 0 ,0
Exp/Cntr=0.3,0.1

Type RM Length L Ch R = 1 ,10252   ,591,591,591
BEGIN DESCRIPTION:
UNT075 IN SUCR 20.0
END DESCRIPTION:
XS GIS Cut Line= 3
      2290330.46     13382331.53      2289856.49     13383013.83
      2289585.66     13384071.12
#Sta/Elev= 30
    3969  343.31  4190.7   335.8    4292  333.83  4319.1  334.39  4341.8  332.98
  4363.6  333.65  4462.5  331.81  4563.5  331.42  4670.9  331.64  4844.2   334.1
  4909.4  333.33  4968.1  333.03  4974.7  332.53    4999  331.38  5050.6  332.57
  5097.1  331.86    5102  330.61  5132.7  332.83  5195.2   332.9  5246.8  334.87
  5277.7  333.03  5301.1  332.77  5336.7  335.63  5418.3  337.15  5432.6  338.56
  5566.8  342.76  5657.9   344.2  5680.3     346  5762.6   346.9  5891.2   350.6
#Mann= 7 ,-1 , 0
    3969     .05       0  4341.8      .1       0  4909.4     .12       0
  4974.7     .07       0  5132.7     .12       0  5432.6     .05       0
  5762.6      .1       0
#XS Ineff= 2 , 0
                         5247.77          334.95
Permanent Ineff=
       F       F
Bank Sta=4968.1,5132.7
XS Rating Curve= 0 ,0
Exp/Cntr=0.3,0.1

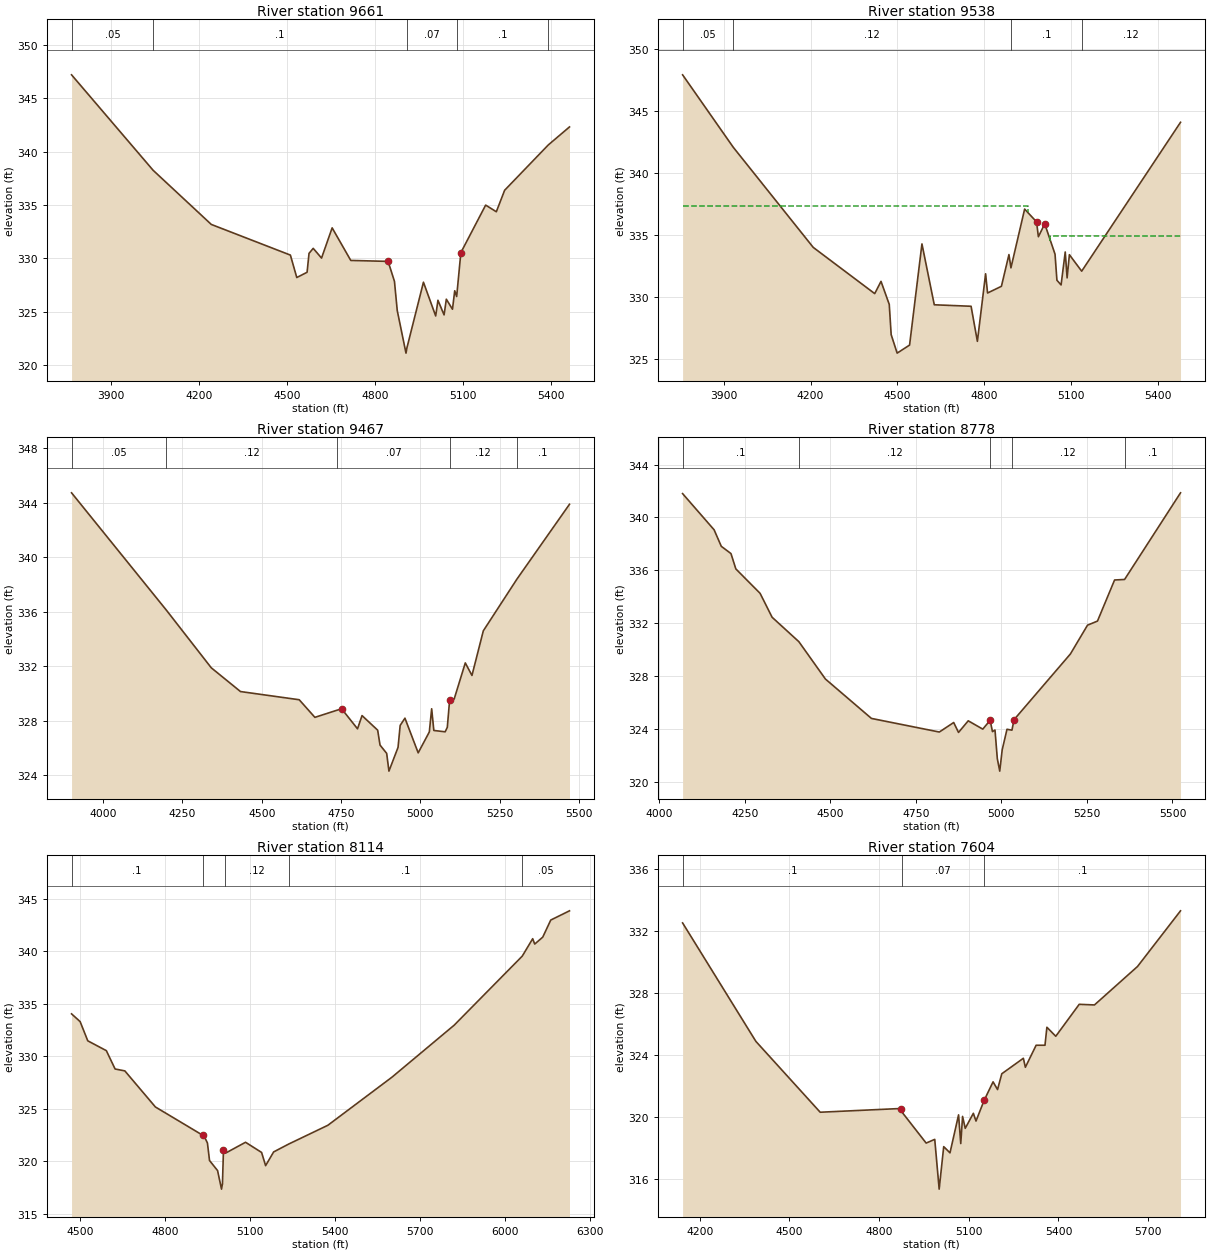
Type RM Length L Ch R = 1 ,9661    ,123,123,123
BEGIN DESCRIPTION:
Mapping XS d7cbd653
END DESCRIPTION:
XS GIS Cut Line= 4
      2290364.53     13382230.92      2289541.64     13382954.85
      2289458.31     13382960.06      2289124.97      13383355.9
#Sta/Elev= 30
    3765  347.18    4043  338.24  4241.3  333.17  4510.8   330.3  4532.6   328.2
  4567.7  328.69  4574.3  330.46  4588.6  330.93    4617  330.02  4653.1  332.85
  4716.6   329.8  4843.8  329.71  4865.5  327.84    4875  325.11  4904.8  321.12
    4908  321.62  4964.3  327.76    5006   324.6  5013.7  326.07  5034.6   324.7
  5042.3  326.17  5063.2  325.23  5070.9  326.96  5077.5  326.42  5091.8  330.53
  5176.3  334.98  5212.7  334.36    5241  336.37  5389.6  340.61    5462   342.3
#Mann= 5 ,-1 , 0
    3765     .05       0    4043      .1       0    4908     .07       0
  5077.5      .1       0  5389.6      .1       0
Bank Sta=4843.8,5091.8
XS Rating Curve= 0 ,0
Exp/Cntr=0.3,0.1

Type RM Length L Ch R = 1 ,9538    ,71,71,71
BEGIN DESCRIPTION:
Mapping XS 12835946
END DESCRIPTION:
XS GIS Cut Line= 4
      2290291.61     13382173.64      2289499.98     13382876.73
      2289359.35     13382887.15      2289032.61     13383291.68
#Sta/Elev= 30
  3758.2   347.9  3933.4  342.05  4209.4  333.98  4421.8  330.25  4443.5  331.24
    4472  329.38  4478.6  326.94  4499.3  325.45  4542.2   326.1  4584.9  334.26
  4627.5  329.35  4754.6  329.23  4776.4   326.4  4804.8  331.85  4811.5   330.3
  4859.4  330.84  4885.4   333.4  4892.3  332.33  4939.6  337.07  4980.7  336.04
  4987.1  334.84    5009  335.88  5044.6  333.43  5051.1  331.33  5065.5  330.95
  5079.8  333.61  5086.3  331.52  5094.2  333.39  5136.6  332.06    5478  344.07
#Mann= 4 ,-1 , 0
  3758.2     .05       0  3933.4     .12       0  4892.3      .1       0
  5136.6     .12       0
#XS Ineff= 2 , 0
       0    4950  337.32 5028.57       0   334.9
Permanent Ineff=
       T       T
Bank Sta=4980.7,5009
XS Rating Curve= 0 ,0
Exp/Cntr=0.3,0.1

Type RM Length L Ch R = 1 ,9467    ,689,689,689
BEGIN DESCRIPTION:
UNT075 IN SUCR 19.0
END DESCRIPTION:
XS GIS Cut Line= 3
      2290028.35     13382055.53      2289460.66     13382706.54
      2288941.29     13383184.37
#Sta/Elev= 30
  3900.5  344.71  4199.5  336.11  4340.9  331.89    4433  330.15  4618.1  329.55
  4667.5  328.26  4738.1  328.79    4752  328.88  4801.9  327.42  4816.1  328.39
  4865.4  327.32  4872.8  326.23  4893.8  325.62  4900.9  324.32  4929.6  326.06
  4936.3  327.67 4951.36   328.2  4993.1  325.66  5028.2  327.19  5035.6  328.89
  5042.4   327.3  5078.1   327.2  5084.9  327.53  5092.3  329.56  5106.5   329.6
  5141.6  332.25  5162.6  331.33  5198.4   334.6  5304.4  338.39    5470  343.87
#Mann= 5 ,-1 , 0
  3900.5     .05       0  4199.5     .12       0  4738.1     .07       0
  5092.3     .12       0  5304.4      .1       0
Bank Sta=4752,5092.3
XS Rating Curve= 0 ,0
Exp/Cntr=0.3,0.1

Type RM Length L Ch R = 1 ,8778    ,664,664,664
BEGIN DESCRIPTION:
UNT075 IN SUCR 18.0
END DESCRIPTION:
XS GIS Cut Line= 3
      2289537.71     13381646.87      2288887.72     13382346.85
      2288587.74     13382746.83
#Sta/Elev= 30
  4068.4   341.8  4160.5  339.06  4181.5  337.81  4209.8  337.26    4224   336.1
  4294.9  334.25    4330  332.44  4408.2  330.59  4485.9  327.76  4620.3  324.78
  4818.7  323.75  4860.7  324.47  4874.8  323.72  4903.2   324.6  4945.7  323.97
  4967.2  324.64    4974  323.78  4981.4   323.9  4988.2  321.73  4995.3  320.79
  5002.4   322.4  5016.5  323.96  5030.9  323.89  5037.2  324.69  5201.8  329.66
  5251.8  331.84  5280.9  332.15  5330.9  335.26  5360.1   335.3  5523.6  341.86
#Mann= 5 ,-1 , 0
  4068.4      .1       0  4408.2     .12       0  4967.2     .07       0
  5030.9     .12       0  5360.1      .1       0
Bank Sta=4967.2,5037.2
XS Rating Curve= 0 ,0
Exp/Cntr=0.3,0.1

Type RM Length L Ch R = 1 ,8114    ,510,510,510
BEGIN DESCRIPTION:
UNT075 IN SUCR 16.0
END DESCRIPTION:
XS GIS Cut Line= 5
      2289247.15      13381498.2      2288965.87     13381565.92
      2288070.04     13382378.42      2288064.83     13382378.42
      2287882.66     13382555.38
#Sta/Elev= 30
  4470.5  334.05  4500.8  333.31  4527.7  331.48  4593.3  330.54  4624.2  328.79
  4658.6  328.61  4766.4  325.17  4934.2  322.46    4936  322.53  4950.2  321.73
  4957.6  320.06    4986   319.1  4999.9  317.33  5003.2  317.83  5006.9  321.11
  5013.8  320.76  5084.7   321.8  5141.4  320.83  5155.6  319.57    5184  320.88
  5237.1  321.63  5375.3  323.42  5601.7  328.01  5821.3  332.97  6061.7  339.56
  6098.5  341.22  6105.7  340.71    6134  341.37  6162.3     343  6228.4  343.88
#Mann= 5 ,-1 , 0
  4470.5      .1       0  4934.2     .07       0  5013.8     .12       0
  5237.1      .1       0  6061.7     .05       0
Bank Sta=4936,5006.9
XS Rating Curve= 0 ,0
Exp/Cntr=0.3,0.1

Type RM Length L Ch R = 1 ,7604    ,564,564,564
BEGIN DESCRIPTION:
UNT075 IN SUCR 15.0
END DESCRIPTION:
XS GIS Cut Line= 3
      2289163.78     13381347.17      2288512.74     13381529.46
      2287691.27     13382080.58
#Sta/Elev= 30
    4143   332.5  4388.1  324.86  4603.2  320.29  4872.3  320.53  4878.3  320.26
  4957.6   318.3  4986.3  318.54  5001.1  315.33  5016.3  318.07  5037.3  317.67
    5066  320.12  5073.3  318.27  5079.4  320.02  5088.3  319.25  5115.4  320.22
  5124.3  319.72  5151.4  321.05  5181.4  322.25  5196.4  321.75  5210.5  322.77
  5282.7  323.77  5289.4  323.19  5325.4  324.61    5355  324.61  5361.4  325.77
  5391.1  325.19  5469.5  327.25  5520.5  327.21  5664.5  329.69  5808.3  333.28
#Mann= 3 ,-1 , 0
    4143      .1       0  4878.3     .07       0  5151.4      .1       0
Bank Sta=4872.3,5151.4
XS Rating Curve= 0 ,0
Exp/Cntr=0.3,0.1

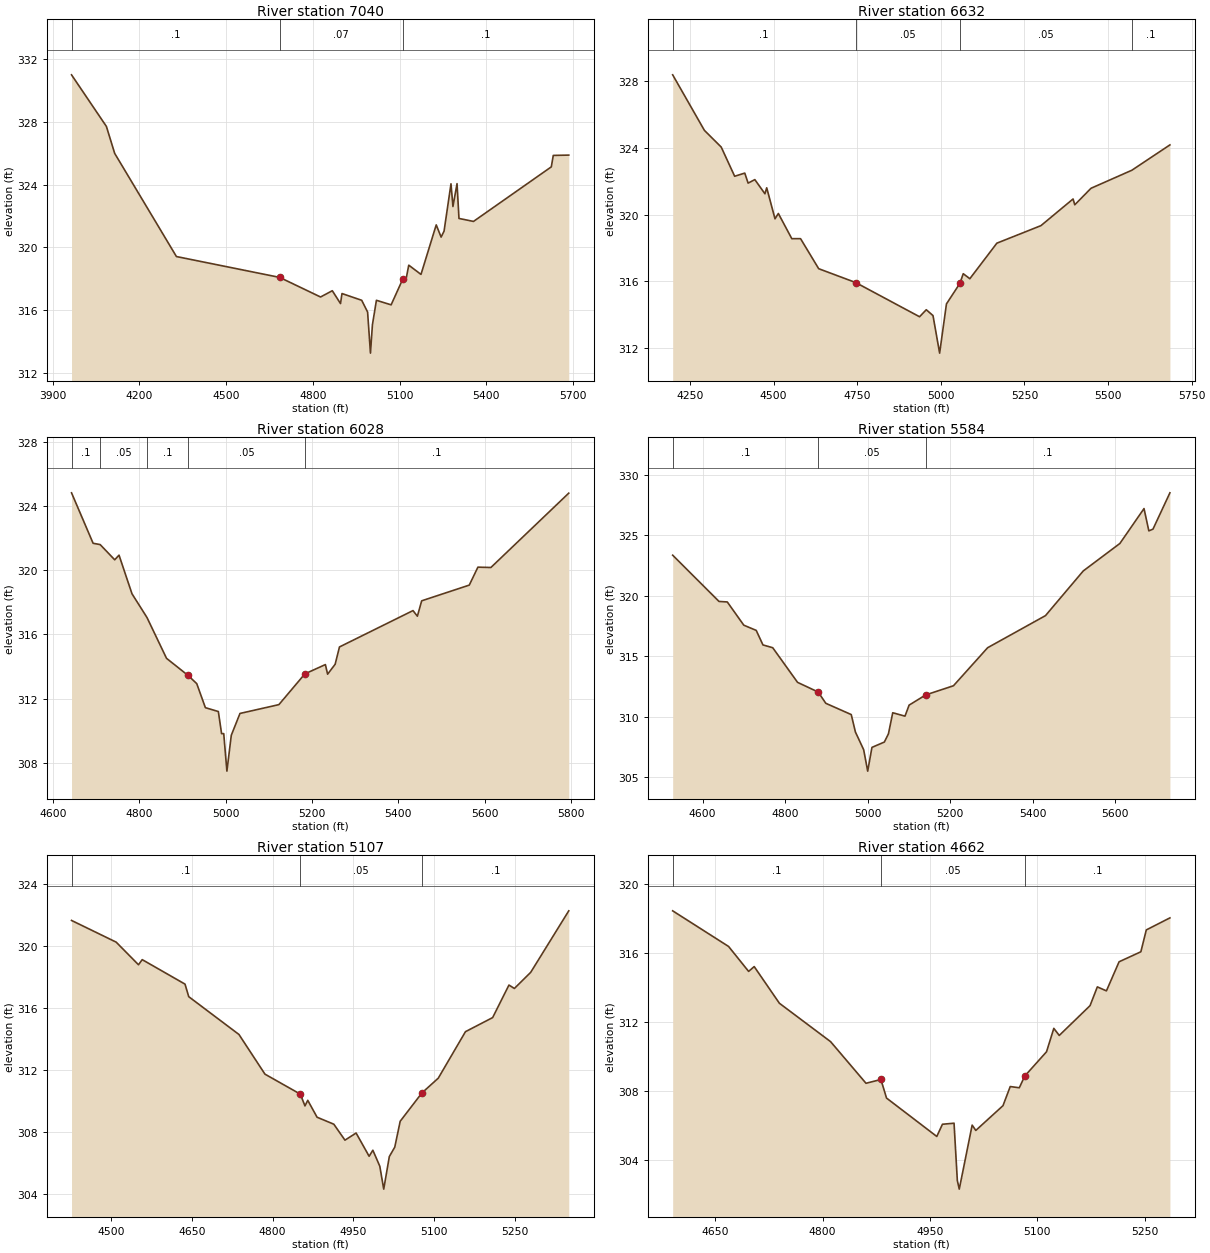
Type RM Length L Ch R = 1 ,7040    ,408,408,408
BEGIN DESCRIPTION:
UNT075 IN SUCR 14.0
END DESCRIPTION:
XS GIS Cut Line= 3
      2289054.46     13381050.28      2287773.16     13381289.87
      2287497.36      13381602.1
#Sta/Elev= 30
  3965.4     331    4086  327.71  4114.7  325.99  4328.3  319.41  4685.4  318.08
  4826.8  316.83  4867.5  317.23  4895.9  316.41    4901  317.05  4969.2  316.62
  4989.6  315.87  4999.5  313.25  5006.3  315.06  5020.1  316.62    5071  316.33
  5111.5  317.98  5121.8  317.89    5132  318.86  5174.3  318.27    5227  321.43
  5243.9  320.65  5254.1  321.03  5278.1  324.05  5284.8   322.6    5299  324.06
  5305.7  321.84  5355.9  321.65  5625.1  325.13  5631.9  325.86  5685.5  325.88
#Mann= 3 , 0 , 0
  3965.4      .1       0  4685.4     .07       0  5111.5      .1       0
Bank Sta=4685.4,5111.5
XS Rating Curve= 0 ,0
Exp/Cntr=0.3,0.1

Type RM Length L Ch R = 1 ,6632    ,604,604,604
BEGIN DESCRIPTION:
UNT075 IN SUCR 13.0
END DESCRIPTION:
XS GIS Cut Line= 2
      2288872.14     13380774.25      2287392.92     13380920.09
#Sta/Elev= 30
  4198.6  328.38  4293.5  325.05  4343.7  324.05  4383.9   322.3  4414.1  322.49
  4424.1  321.89  4444.2   322.1  4474.4  321.25  4479.7  321.61  4504.5  319.75
  4514.5  320.07  4554.7  318.56  4580.9  318.56  4635.1  316.76  4745.7  315.93
  4936.6  313.88  4956.7   314.3  4976.8  313.95  4996.6   311.7    5017  314.65
  5057.2  315.88  5067.2  316.46  5086.9  316.16  5167.7  318.29  5299.4  319.34
  5395.5  320.94  5400.6  320.59  5449.1  321.58  5571.1  322.66    5685  324.18
#Mann= 4 ,-1 , 0
  4198.6      .1       0  4745.7     .05       0  5057.2     .05       0
  5571.1      .1       0
Bank Sta=4745.7,5057.2
XS Rating Curve= 0 ,0
Exp/Cntr=0.3,0.1

Type RM Length L Ch R = 1 ,6028    ,444,444,444
BEGIN DESCRIPTION:
UNT075 IN SUCR 12.0
END DESCRIPTION:
XS GIS Cut Line= 3
       2288487.7     13380296.85      2288137.72     13380296.85
      2287337.76     13380246.86
#Sta/Elev= 30
  4643.3  324.84  4693.3  321.69  4709.6  321.61  4743.3  320.66  4753.3  320.95
  4783.3  318.54    4818  317.06  4863.3  314.51  4913.3  313.44  4933.3  312.93
  4953.3  311.43  4983.3  311.19  4990.8  309.81  4995.8  309.81  5003.1  307.47
  5013.3  309.71  5033.4  311.07  5123.5  311.62  5183.7  313.54  5231.2  314.12
  5236.3  313.52  5253.8  314.14  5263.8  315.22  5434.1  317.49  5444.2  317.14
  5454.2   318.1  5564.4  319.08  5584.4   320.2  5614.5  320.18  5794.8  324.82
#Mann= 5 ,-1 , 0
  4643.3      .1       0  4709.6     .05       0    4818      .1       0
  4913.3     .05       0  5183.7      .1       0
Bank Sta=4913.3,5183.7
XS Rating Curve= 0 ,0
Exp/Cntr=0.3,0.1

Type RM Length L Ch R = 1 ,5584    ,477,477,477
BEGIN DESCRIPTION:
UNT075 IN SUCR 11.0
END DESCRIPTION:
XS GIS Cut Line= 2
      2288439.86     13379857.58      2287236.69     13379935.71
#Sta/Elev= 30
  4527.3  323.34  4639.7  319.52  4659.7  319.48  4699.8  317.56  4729.9  317.13
  4746.2  315.93  4769.9   315.7  4830.1  312.84  4880.2  312.04  4898.6  311.11
  4960.3  310.18  4970.4  308.74  4990.4  307.28  5000.2  305.51  5010.5  307.47
  5040.5  307.91  5050.5  308.59  5060.9  310.33  5090.6  310.05  5100.6  310.96
  5140.7   311.8  5208.2  312.56    5291   315.7  5431.3  318.35  5522.9  322.04
  5611.7  324.31  5670.2  327.19  5681.9  325.35  5691.9  325.49    5733  328.49
#Mann= 3 , 0 , 0
  4527.3      .1       0  4880.2     .05       0  5140.7      .1       0
Bank Sta=4880.2,5140.7
XS Rating Curve= 0 ,0
Exp/Cntr=0.3,0.1

Type RM Length L Ch R = 1 ,5107    ,445,445,445
BEGIN DESCRIPTION:
UNT075 IN SUCR 10.0
END DESCRIPTION:
XS GIS Cut Line= 3
      2288387.73     13379646.86      2287837.72     13379496.85
      2287487.77     13379446.86
#Sta/Elev= 30
  4426.5  321.65  4509.4  320.25  4550.9  318.79  4557.8  319.12  4637.3  317.54
  4644.2  316.73  4737.5  314.29  4785.8  311.73  4851.5  310.44  4860.1  309.68
  4865.3  310.04  4882.6  308.95  4913.7   308.5  4934.4  307.47  4955.1  307.93
  4979.3  306.43  4986.2  306.82  4999.1  305.79  5006.4  304.31  5016.8  306.41
  5026.9  307.02    5037  308.69  5077.4  310.52  5107.7  311.47  5158.2  314.47
  5208.7  315.38    5239  317.48  5249.1  317.26  5279.4   318.3  5350.1  322.27
#Mann= 3 , 0 , 0
  4426.5      .1       0  4851.5     .05       0  5077.4      .1       0
Bank Sta=4851.5,5077.4
XS Rating Curve= 0 ,0
Exp/Cntr=0.3,0.1

Type RM Length L Ch R = 1 ,4662    ,415,415,415
BEGIN DESCRIPTION:
UNT075 IN SUCR 9.0
END DESCRIPTION:
XS GIS Cut Line= 3
      2288287.73     13379346.86      2287987.72     13379096.85
      2287687.68     13379046.85
#Sta/Elev= 30
  4590.5  318.47  4668.6   316.4  4696.6  314.95  4704.4  315.23  4739.6   313.1
  4811.1  310.87  4860.6  308.45  4881.4  308.67  4889.3  307.59  4959.5  305.36
  4967.4  306.07  4983.6  306.13  4988.2   302.8  4990.9   302.3  5008.9  306.02
    5014  305.71    5052  307.15  5062.1  308.26  5074.8  308.19  5082.4  308.87
  5112.8  310.28    5123  311.64  5130.6  311.23  5173.6  312.96  5183.8  314.05
  5196.5  313.82  5214.2  315.51  5244.6  316.09  5252.2  317.36  5285.2  318.06
#Mann= 3 , 0 , 0
  4590.5      .1       0  4881.4     .05       0  5082.4      .1       0
Bank Sta=4881.4,5082.4
XS Rating Curve= 0 ,0
Exp/Cntr=0.3,0.1