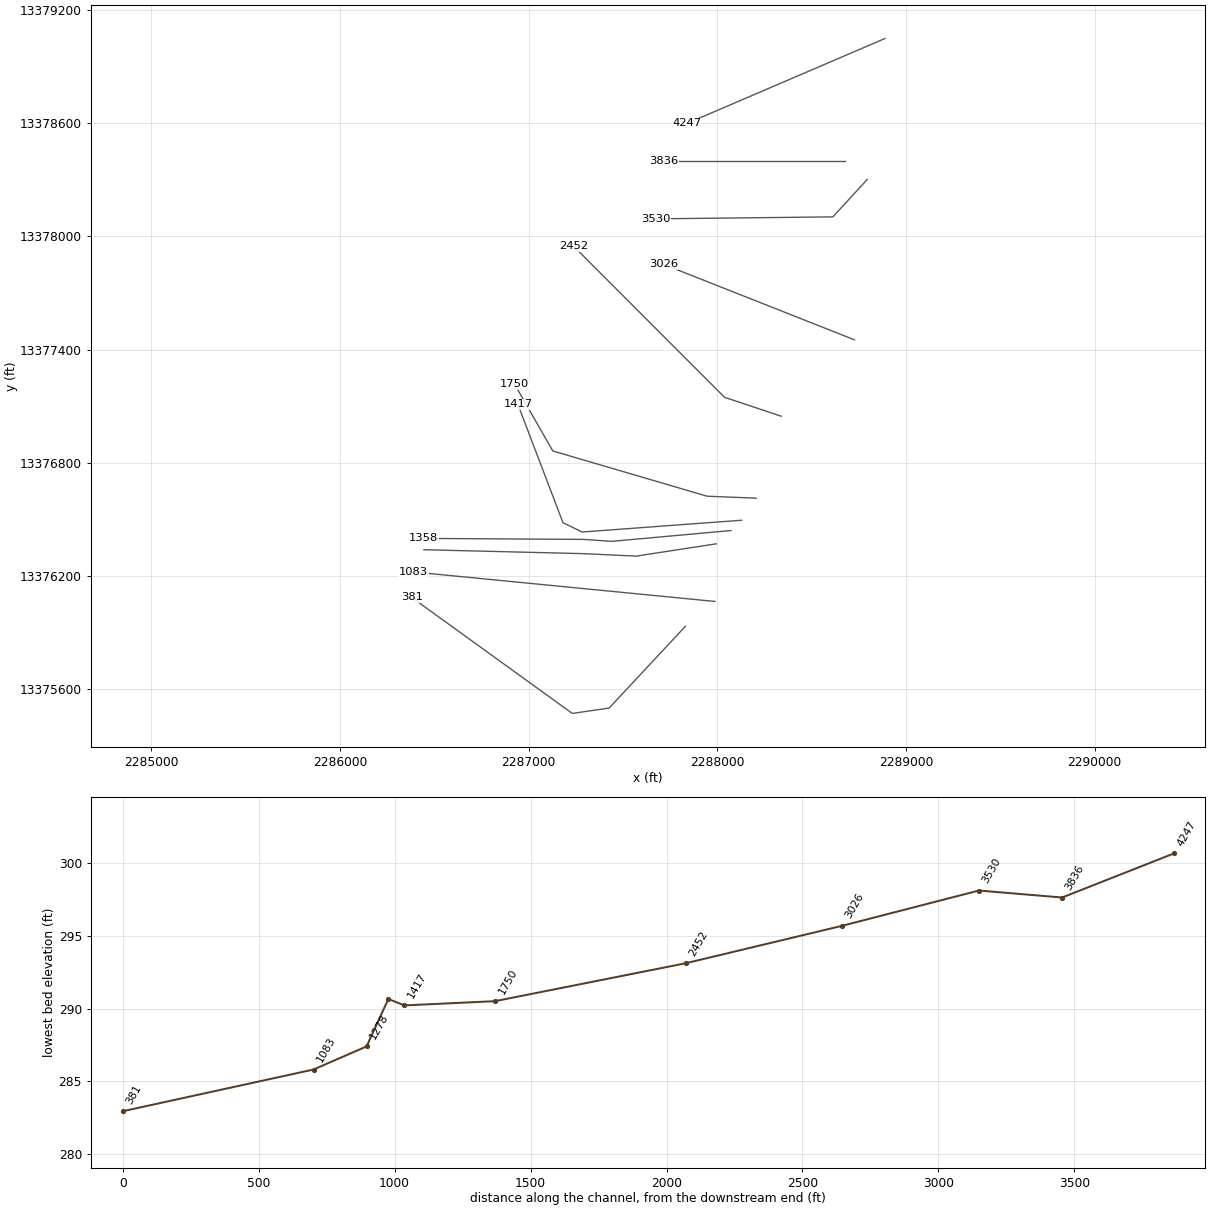
HEC-RAS study UNT075 IN SUCR.prj: UNT075 IN SUCR Base Level Engineering

--- UNT075 IN SUCR.g01 (geometry) --- (continued)

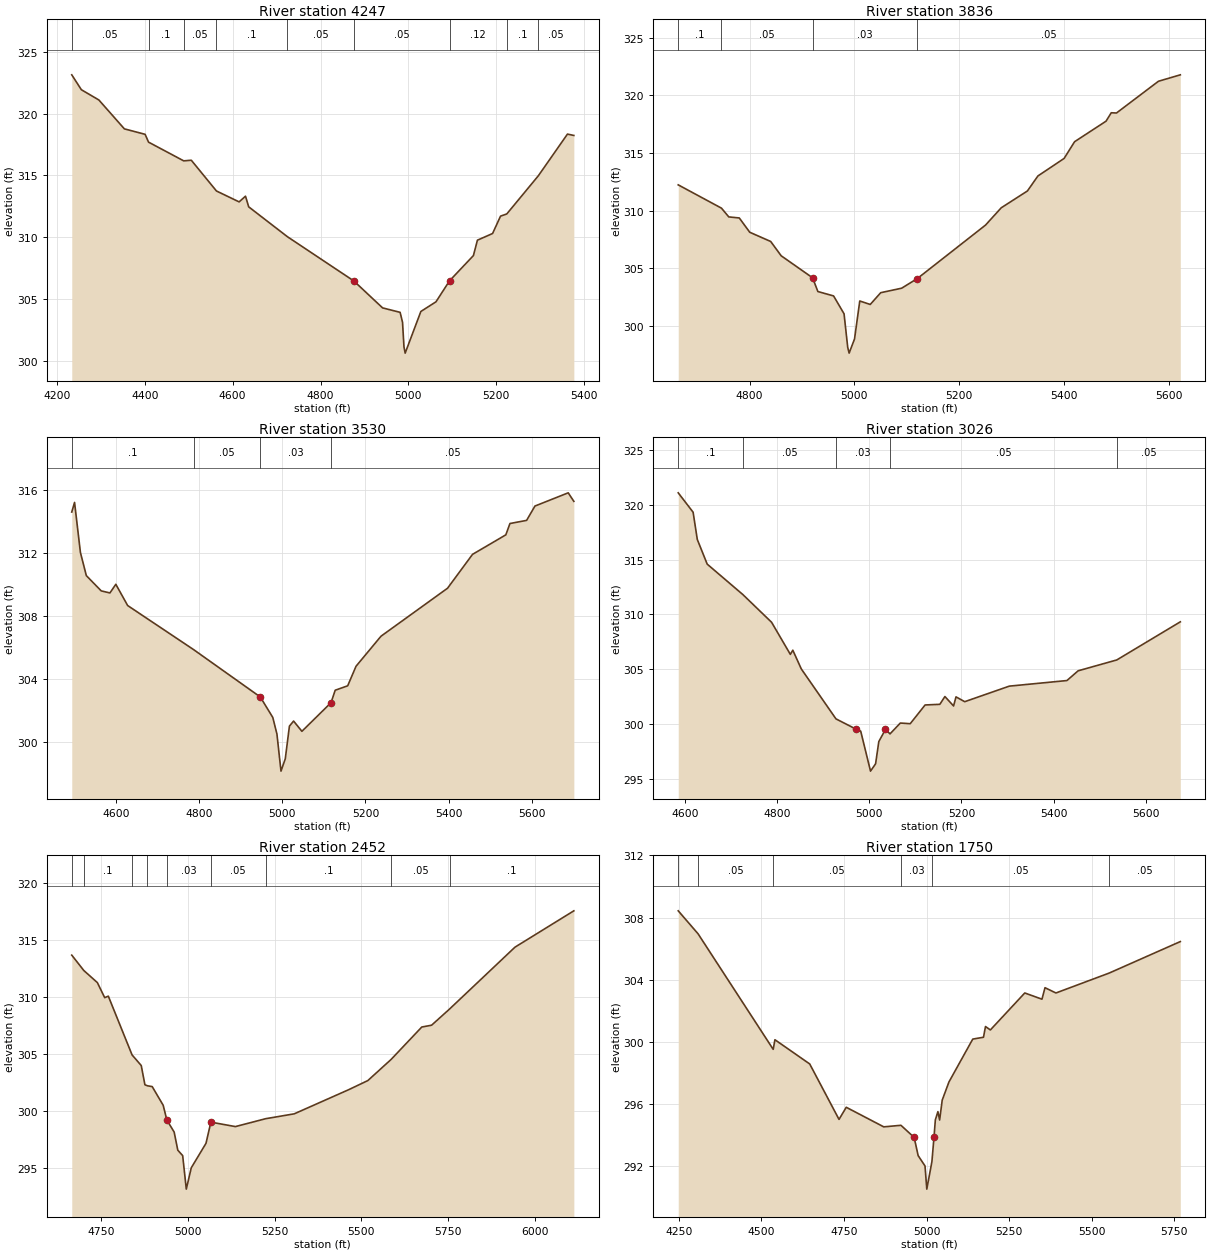
Type RM Length L Ch R = 1 ,4247    ,411,411,411
BEGIN DESCRIPTION:
UNT075 IN SUCR 8.0
END DESCRIPTION:
XS GIS Cut Line= 3
      2288887.76     13379046.87      2288187.72     13378746.85
      2287837.73     13378596.86
#Sta/Elev= 30
    4234  323.12  4255.8  321.92  4295.7  321.09  4353.7  318.76  4400.9  318.32
  4408.7  317.69  4488.7  316.18    4506  316.23  4563.2  313.75  4614.8  312.87
  4629.3  313.33  4636.6  312.47  4724.7  310.06  4875.9  306.49  4941.2  304.32
  4981.1  303.96  4986.6  303.16  4989.9  301.17  4992.6  300.67  5028.3  304.03
  5062.7  304.81  5093.5   306.5  5147.9  308.54    5157  309.78  5191.5  310.32
  5209.6  311.72  5223.9   311.9  5295.7  314.98  5361.9  318.34  5376.4  318.23
#Mann= 9 ,-1 , 0
    4234     .05       0  4408.7      .1       0  4488.7     .05       0
  4563.2      .1       0  4724.7     .05       0  4875.9     .05       0
  5093.5     .12       0  5223.9      .1       0  5295.7     .05       0
Bank Sta=4875.9,5093.5
XS Rating Curve= 0 ,0
Exp/Cntr=0.3,0.1

Type RM Length L Ch R = 1 ,3836    ,306,306,306
BEGIN DESCRIPTION:
UNT075 IN SUCR 7.0
END DESCRIPTION:
XS GIS Cut Line= 2
       2288674.2     13378399.25       2287715.9     13378399.25
#Sta/Elev= 30
  4663.8  312.23  4746.3  310.21  4760.3  309.45  4780.3  309.36  4800.3  308.12
  4840.3  307.32  4860.3  306.08  4920.3  304.17  4930.3  302.98  4960.3   302.6
  4980.3  301.05  4987.3  298.14    4990  297.64  5000.3  298.87  5010.3  302.16
  5030.3  301.86  5050.3  302.88  5090.3  303.27  5120.3  304.11  5250.3  308.74
  5280.3  310.24  5330.3   311.7  5350.3     313  5400.3  314.52  5420.3  315.97
  5480.3  317.75  5490.3  318.48  5500.3  318.46  5580.3  321.21  5622.1  321.77
#Mann= 4 ,-1 , 0
  4663.8      .1       0  4746.3     .05       0  4920.3     .03       0
  5120.3     .05       0
Bank Sta=4920.3,5120.3
XS Rating Curve= 0 ,0
Exp/Cntr=0.3,0.1

Type RM Length L Ch R = 1 ,3530    ,504,504,504
BEGIN DESCRIPTION:
UNT075 IN SUCR 6.0
END DESCRIPTION:
XS GIS Cut Line= 3
      2288793.99     13378300.28       2288611.7     13378102.37
      2287674.23     13378091.96
#Sta/Elev= 30
  4494.2  314.58  4500.9  315.19    4515  312.01  4529.2  310.54    4565  309.57
  4585.9  309.44  4600.1  309.99  4628.5  308.64    4787  305.84  4947.3  302.83
  4977.3  301.53  4987.3  300.47    4997  298.12  5007.3   298.9  5017.3  300.98
  5027.3   301.3  5047.3  300.65  5117.3  302.47  5127.3  303.26  5157.3  303.54
  5177.3  304.78  5237.3  306.69  5397.3  309.74  5457.3  311.89  5537.3  313.13
  5547.3  313.85  5587.3  314.05  5607.3  314.96  5687.3   315.8  5700.8  315.26
#Mann= 4 ,-1 , 0
  4494.2      .1       0    4787     .05       0  4947.3     .03       0
  5117.3     .05       0
Bank Sta=4947.3,5117.3
XS Rating Curve= 0 ,0
Exp/Cntr=0.3,0.1

Type RM Length L Ch R = 1 ,3026    ,574,574,574
BEGIN DESCRIPTION:
UNT075 IN SUCR 5.0
END DESCRIPTION:
XS GIS Cut Line= 2
      2288726.26     13377451.34      2287712.35     13377851.71
#Sta/Elev= 30
  4585.2   321.1  4617.5  319.33  4626.6  316.84  4648.1  314.59  4725.8   311.8
  4787.9  309.28  4828.6  306.35    4834  306.73  4852.4  305.02  4927.7  300.46
  4971.9  299.51  4981.4  299.34  5002.7  295.69  5013.7  296.36  5020.7  298.39
  5035.2   299.5    5045  299.09  5067.4  300.08  5088.9  300.02  5121.2  301.73
  5153.2  301.79  5164.2   302.5    5183  301.64  5188.3  302.47  5207.2  302.03
    5304  303.45  5429.1  303.96  5453.5  304.85  5537.3  305.84  5675.3  309.32
#Mann= 5 ,-1 , 0
  4585.2      .1       0  4725.8     .05       0  4927.7     .03       0
    5045     .05       0  5537.3     .05       0
Bank Sta=4971.9,5035.2
XS Rating Curve= 0 ,0
Exp/Cntr=0.3,0.1

Type RM Length L Ch R = 1 ,2452    ,702,702,702
BEGIN DESCRIPTION:
UNT075 IN SUCR 4.0
END DESCRIPTION:
XS GIS Cut Line= 3
      2288337.75     13377046.84      2288037.72     13377146.85
      2287237.74     13377946.83
#Sta/Elev= 30
  4665.1  313.66  4699.9  312.31  4738.9  311.25    4760  309.93  4770.5  310.06
    4839   304.9  4865.4  303.97    4876  302.28  4883.4  302.19    4897  302.12
  4928.7  300.48  4939.2  299.19  4960.3  298.13  4970.8  296.54  4984.9  296.06
  4995.3  293.12  5009.6  294.99  5052.1  297.14  5066.2     299  5136.9  298.61
  5223.8   299.3  5306.6  299.73  5462.2  301.83  5518.8  302.65    5586  304.51
  5674.3  307.35  5702.6  307.51  5754.4  308.93    5943  314.36  6112.7  317.55
#Mann= 9 ,-1 , 0
  4665.1     .05       0  4699.9      .1       0    4839     .05       0
  4883.4      .1       0  4939.2     .03       0  5066.2     .05       0
  5223.8      .1       0    5586     .05       0  5754.4      .1       0
Bank Sta=4939.2,5066.2
XS Rating Curve= 0 ,0
Exp/Cntr=0.3,0.1

Type RM Length L Ch R = 1 ,1750    ,333,333,333
BEGIN DESCRIPTION:
UNT075 IN SUCR 3.0
END DESCRIPTION:
XS GIS Cut Line= 4
      2288205.49     13376612.79      2287945.04     13376623.21
      2287127.33     13376862.79      2286924.21     13377216.94
#Sta/Elev= 30
  4247.9  308.43    4308  306.95  4535.6  299.51  4540.8  300.13  4646.2  298.57
    4735     295  4756.9  295.78  4870.5  294.52  4922.6  294.62  4962.6  293.84
  4974.7  292.67  4995.5     292  5000.9  290.51  5016.4  292.28 5022.86  293.89
  5026.8  294.97  5034.6   295.5  5039.8  294.96  5047.6  296.24    5068  297.41
  5140.1  300.17  5172.7  300.29  5178.7  300.98  5193.5  300.76  5297.7  303.14
  5349.8  302.74    5359  303.48  5392.1  303.14  5553.2  304.42  5768.9  306.45
#Mann= 6 ,-1 , 0
  4247.9      .1       0    4308     .05       0  4535.6     .05       0
  4922.6     .03       0  5016.4     .05       0  5553.2     .05       0
Bank Sta=4962.6,5022.86
XS Rating Curve= 0 ,0
Exp/Cntr=0.3,0.1

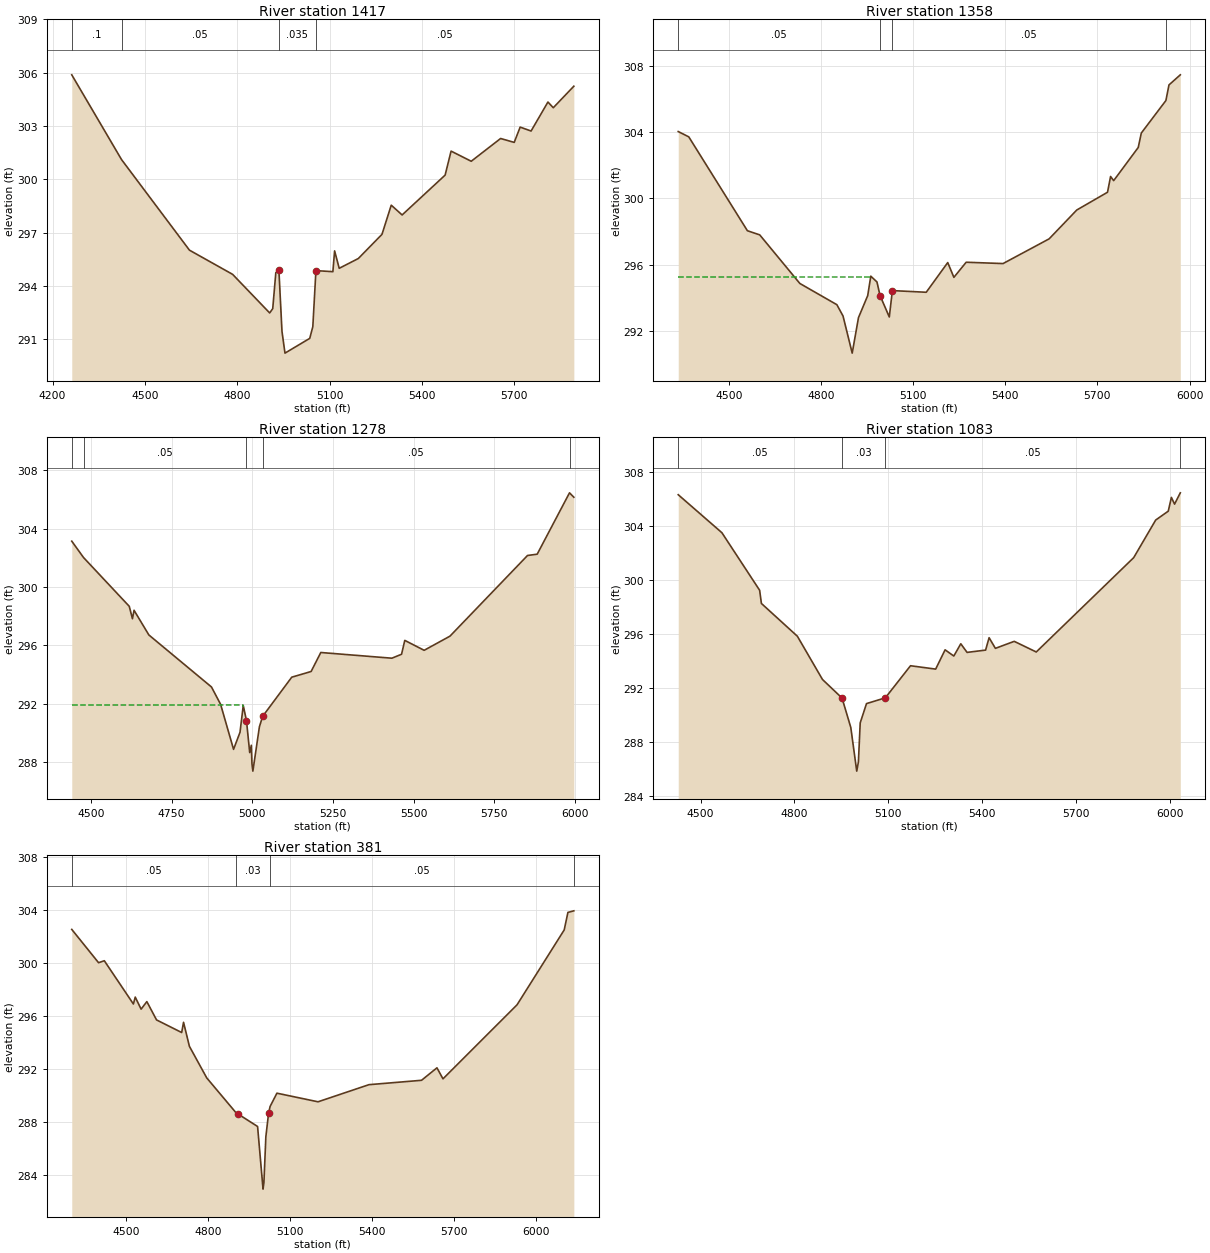
Type RM Length L Ch R = 1 ,1417    ,59,59,59
XS GIS Cut Line= 4
      2288129.13     13376496.05      2287282.78     13376433.55
      2287181.22     13376483.03      2286942.18     13377109.23
#Sta/Elev= 30
  4262.3  305.87  4424.2   301.1  4644.8  296.01  4785.1  294.65  4905.5  292.48
  4915.5  292.72  4925.5  294.74  4935.5  294.89  4945.6  291.44  4955.3  290.22
  5035.8  291.05  5045.8  291.71  5055.9  294.86    5111   294.8  5116.6  295.97
  5131.6  294.99  5193.7  295.54  5270.6   296.9  5300.7  298.54  5336.1  297.99
  5475.8  300.23  5495.2  301.58  5560.7  301.01  5656.2  302.29  5700.4  302.07
  5719.7  302.93  5755.2  302.71    5810  304.34  5827.4  304.02  5894.2  305.23
#Mann= 4 ,-1 , 0
  4262.3      .1       0  4424.2     .05       0  4935.5    .035       0
  5055.9     .05       0
#XS Ineff= 1 ,-1
 4746.13 4926.32  294.73
Permanent Ineff=
       T
Bank Sta=4935.5,5055.9
XS Rating Curve= 0 ,0
Exp/Cntr=0.3,0.1

Type RM Length L Ch R = 1 ,1358    ,80,80,80
XS GIS Cut Line= 4
      2288071.88     13376441.37      2287439.03     13376384.07
       2287290.6     13376394.49      2286440.85     13376399.68
#Sta/Elev= 30
  4335.8  304.02  4370.1   303.7  4560.9  298.04    4601  297.79  4731.6  294.86
  4852.1  293.58  4872.1   292.9    4902  290.66  4922.4   292.8  4952.5  294.13
  4962.5   295.3  4982.6  294.95  4992.6  294.13  5022.7  292.84  5032.7  294.43
  5142.9  294.33  5212.9  296.12  5232.9  295.23  5272.9  296.14  5392.9  296.06
  5542.9  297.55  5632.9  299.29  5732.9  300.36  5742.9  301.31  5752.9  301.06
  5832.9  303.06  5842.9  303.93  5922.9  305.89  5932.9  306.83  5969.8  307.44
#Mann= 4 ,-1 , 0
  4335.8     .05       0  4992.6    .035       0  5032.7     .05       0
  5922.9      .1       0
#XS Ineff= 2 , 0
       0 4961.61  295.26               0
Permanent Ineff=
       T       F
Bank Sta=4992.6,5032.7
XS Rating Curve= 0 ,0
Exp/Cntr=0.3,0.1

Type RM Length L Ch R = 1 ,1278    ,195,195,195
XS GIS Cut Line= 4
      2287993.75     13376371.05      2287569.24     13376305.95
       2287290.6     13376318.97      2286444.28      13376339.8
#Sta/Elev= 30
  4441.1  303.14  4477.6  302.02  4619.2  298.68    4629  297.83    4634  298.41
  4679.9  296.72  4873.8  293.16  4902.1  291.97  4942.2  288.89  4962.2  290.06
  4972.2  291.89  4982.2  290.86  4992.2  288.67  4997.2  289.17  4999.2   287.9
    5002   287.4  5022.3  290.44  5032.3  291.15  5122.4  293.83  5182.4  294.22
  5212.4  295.52  5432.5  295.13  5462.5   295.4  5472.5  296.35  5532.5  295.67
  5612.5  296.64  5852.6  302.16  5882.6  302.25  5982.7  306.45  5996.1  306.15
#Mann= 5 ,-1 , 0
  4441.1      .1       0  4477.6     .05       0  4982.2    .035       0
  5032.3     .05       0  5982.7     .05       0
#XS Ineff= 2 , 0
       0 4972.96  291.92               0
Permanent Ineff=
       T       F
Bank Sta=4982.2,5032.3
XS Rating Curve= 0 ,0
Exp/Cntr=0.3,0.1

Type RM Length L Ch R = 1 ,1083    ,702,702,702
BEGIN DESCRIPTION:
UNT075 IN SUCR 2.0
END DESCRIPTION:
XS GIS Cut Line= 2
      2287986.68     13376065.92      2286389.39     13376222.01
#Sta/Elev= 30
  4428.6  306.32  4568.2   303.5  4688.8  299.23  4694.5  298.25  4809.4  295.82
  4889.7  292.61 4952.27  291.23  4980.2  289.05  4999.2  285.81  5004.5  286.49
  5010.3  289.39  5030.4  290.82  5090.7  291.25  5171.1  293.63  5251.5  293.38
  5281.6  294.81  5309.5  294.35  5331.8  295.26  5351.9  294.62  5411.1  294.79
  5422.3  295.71  5442.4  294.92  5502.6  295.44    5573  294.65  5884.5  301.65
  5954.8  304.44    5995   305.1    6005  306.12  6015.1  305.62  6033.5  306.46
#Mann= 4 ,-1 , 0
  4428.6     .05       0 4952.27     .03       0  5090.7     .05       0
  6033.5      .1       0
Bank Sta=4952.27,5090.7
XS Rating Curve= 0 ,0
Exp/Cntr=0.3,0.1

Type RM Length L Ch R = 1 ,381     ,0,0,0
BEGIN DESCRIPTION:
UNT075 IN SUCR 1.0
END DESCRIPTION:
XS GIS Cut Line= 4
      2287829.61     13375933.78      2287425.99     13375501.52
      2287230.68     13375472.87       2286379.1     13376087.47
#Sta/Elev= 30
  4300.4  302.51  4398.6     300  4419.6  300.15  4526.1  296.89  4532.9  297.41
  4554.4   296.5  4575.4  297.07  4610.9  295.69    4703  294.74  4709.8  295.51
  4731.3   293.7  4794.8  291.32  4900.2  288.74  4910.3  288.59    4981  287.66
    5001  282.94  5004.2  283.44  5011.3  286.89  5021.4  288.68  5026.9  289.17
  5051.8  290.17  5202.4  289.52  5388.8  290.81  5581.5  291.14    5638  292.08
  5660.1  291.25  5931.4  296.83  6104.1  302.47  6117.7  303.79  6139.4  303.91
#Mann= 4 ,-1 , 0
  4300.4     .05       0  4900.2     .03       0  5026.9     .05       0
  6139.4      .1       0
Bank Sta=4910.3,5021.4
XS Rating Curve= 0 ,0
Exp/Cntr=0.3,0.1

Chan Stop Cuts=-1
Use User Specified Reach Order=0
Composite Channel Slope=5