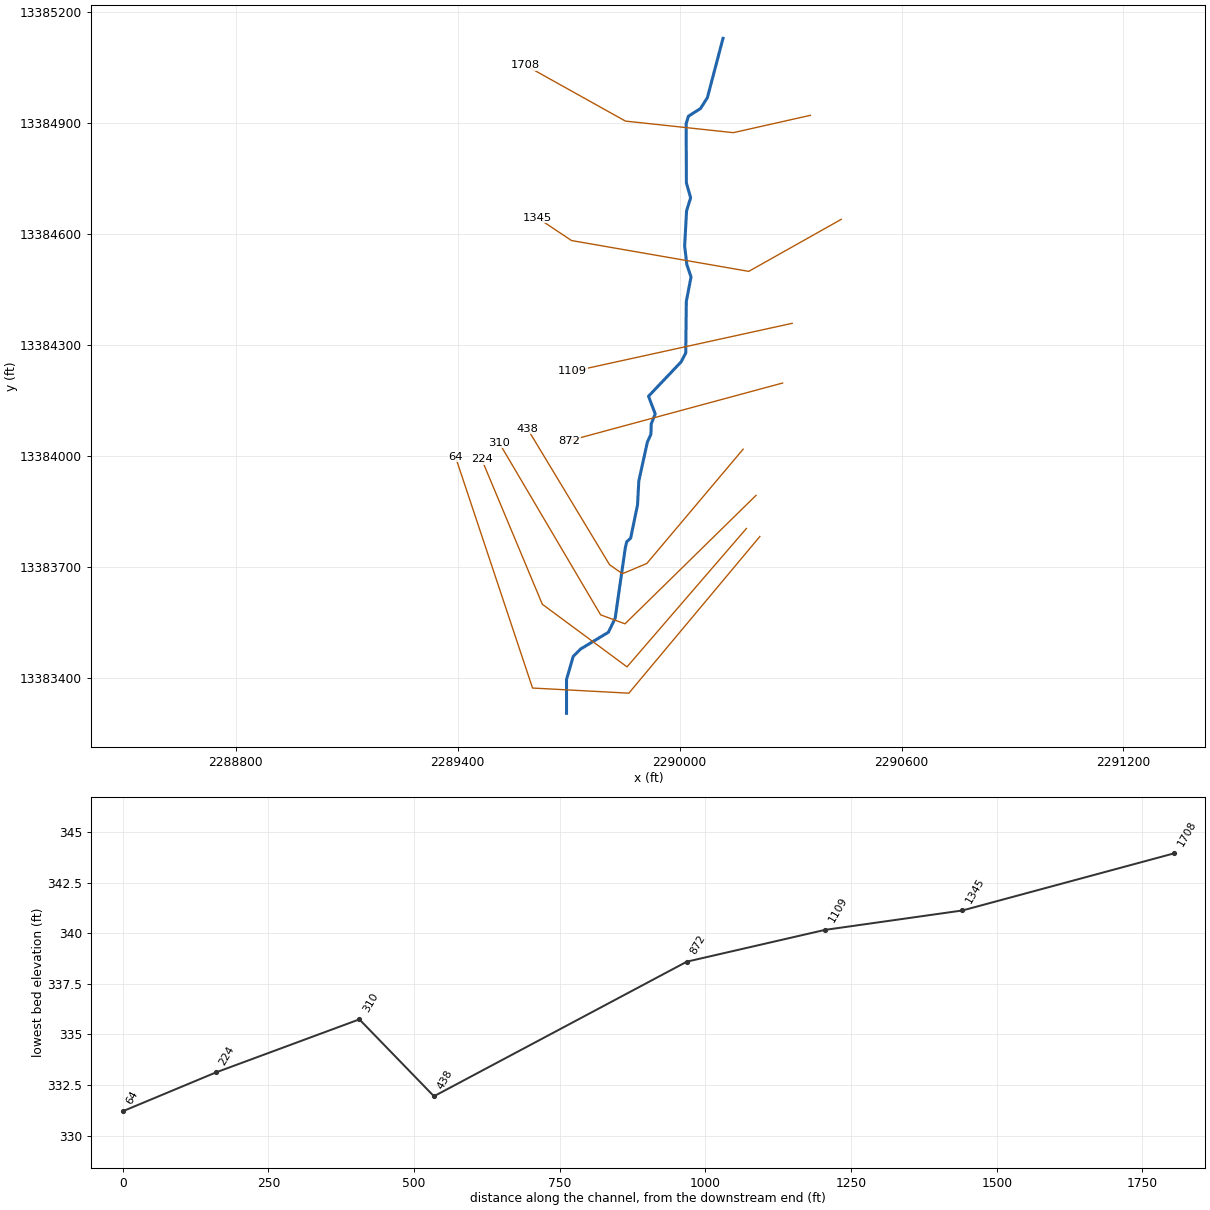
--- UNT076 IN SUCR.prj (project) ---

Proj Title=UNT076 IN SUCR Base Level Engineering
Current Plan=p01
Default Exp/Contr=0.3,0.1
English Units
Geom File=g01
Flow File=f01
Plan File=p01
Y Axis Title=Elevation
X Axis Title(PF)=Main Channel Distance
X Axis Title(XS)=Station
BEGIN DESCRIPTION:
UNT076 IN SUCR
END DESCRIPTION:
DSS Export Rating Curves= 0
DSS Export Rating Curve Sorted= 0
DSS Export Volume Flow Curves= 0
DXF OffsetX= 0
DXF OffsetY= 0
DXF ScaleX= 1
DXF ScaleY= 10

--- UNT076 IN SUCR.p01 (plan) ---

Plan Title=Multiple Run
Short Identifier=Multiple
Geom File=g01
Flow File=f01
Subcritical Flow
K Sum by GR= 0
Std Step Tol= 0.01
Critical Tol= 0.01
Num of Std Step Trials= 20
Max Error Tol= 0.3
Flow Tol Ratio= 0.001
Split Flow NTrial= 30
Split Flow Tol= 0.02
Split Flow Ratio= 0.02
Log Output Level= 0
Friction Slope Method= 1
Unsteady Friction Slope Method= 2
Unsteady Bridges Friction Slope Method= 1
Parabolic Critical Depth
Global Vel Dist=  1 , 1 , 1
Global Log Level= 0
CheckData=True
Encroach Param= -1, 0, 0, 0
BEGIN DESCRIPTION:
Multiple Run
END DESCRIPTION:

--- UNT076 IN SUCR.f01 (steady flow) ---

Flow Title=Multiple
Program Version=4.10
Number of Profiles= 7
Profile Names=10-year,25-year,50-year,1pct_min,100-year,1pct_plu,500-year
River Rch & RM=UNT076 IN SUCR,Reach-1         ,1708
     239     323     392     349     472     638     685
Boundary for River Rch & Prof#=UNT076 IN SUCR,Reach-1         , 1
Up Type= 0
Dn Type= 3
Dn Slope=0.0185
Boundary for River Rch & Prof#=UNT076 IN SUCR,Reach-1         , 2
Up Type= 0
Dn Type= 3
Dn Slope=0.0185
Boundary for River Rch & Prof#=UNT076 IN SUCR,Reach-1         , 3
Up Type= 0
Dn Type= 3
Dn Slope=0.0185
Boundary for River Rch & Prof#=UNT076 IN SUCR,Reach-1         , 4
Up Type= 0
Dn Type= 3
Dn Slope=0.0185
Boundary for River Rch & Prof#=UNT076 IN SUCR,Reach-1         , 5
Up Type= 0
Dn Type= 3
Dn Slope=0.0185
Boundary for River Rch & Prof#=UNT076 IN SUCR,Reach-1         , 6
Up Type= 0
Dn Type= 3
Dn Slope=0.0185
Boundary for River Rch & Prof#=UNT076 IN SUCR,Reach-1         , 7
Up Type= 0
Dn Type= 3
Dn Slope=0.0185
DSS Import GetInterval= 0
DSS Import GetPeak= 0
DSS Import FillOption= 0

--- UNT076 IN SUCR.g01 (geometry) ---

Geom Title=Existing Conditions
Program Version=4.10

River Reach=UNT076 IN SUCR  ,Reach-1
Reach XY= 30
      2290117.41     13385128.05      2290075.17     13384967.78
      2290056.47     13384938.17      2290024.04     13384917.64
      2290017.79     13384897.71      2290018.37     13384737.02
      2290029.85     13384696.87      2290018.86     13384661.56
      2290013.68     13384566.77      2290019.54     13384516.69
      2290030.92     13384482.86      2290018.18     13384416.77
      2290016.66     13384277.29      2290003.95      13384253.1
      2289915.97     13384160.39      2289934.12      13384112.6
      2289923.33     13384085.82      2289922.53     13384057.96
      2289912.78     13384035.95      2289889.77     13383931.33
       2289886.3     13383866.84      2289867.64     13383776.52
      2289857.05     13383767.15      2289853.14     13383750.23
       2289825.8     13383560.12      2289807.57     13383522.36
      2289732.05     13383476.79      2289712.52     13383457.26
      2289694.29     13383394.76      2289694.35     13383303.01

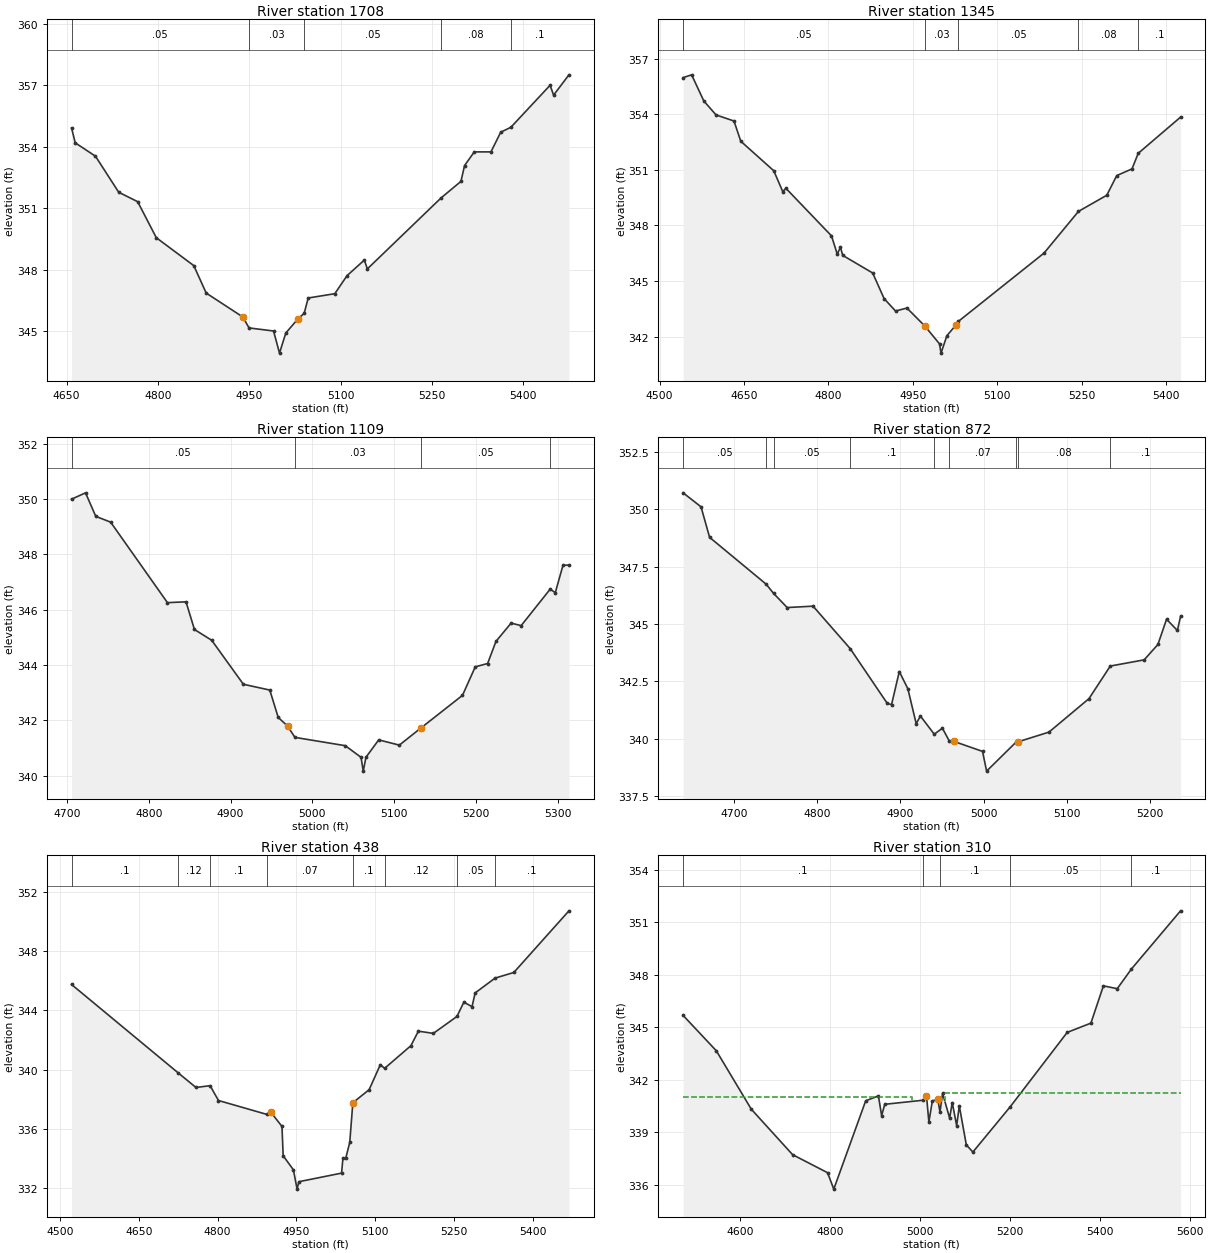
Type RM Length L Ch R = 1 ,1708    ,363,363,363
BEGIN DESCRIPTION:
UNT076 IN SUCR 3.0
END DESCRIPTION:
XS GIS Cut Line= 4
      2290353.67      13384919.9      2290145.35     13384873.03
      2289853.68     13384904.28      2289582.82     13385055.33
#Sta/Elev= 30
  4658.2  354.93  4664.3   354.2  4697.5  353.55  4735.7  351.79  4766.8  351.33
  4797.5  349.57    4859  348.21  4879.4  346.87  4939.7   345.7  4949.7  345.17
    4990  345.02  4999.8  343.94  5010.1  344.92  5030.3  345.62  5040.3  345.88
  5046.9  346.63  5090.6  346.84  5110.7  347.72  5139.1  348.48  5144.1  348.05
  5265.4  351.52  5297.8  352.32  5303.7  353.09  5319.7  353.76  5347.1  353.76
  5363.1  354.72  5379.8  354.96  5444.2  357.01    5450  356.53  5475.2  357.52
#Mann= 5 ,-1 , 0
  4658.2     .05       0  4949.7     .03       0  5040.3     .05       0
  5265.4     .08       0  5379.8      .1       0
Bank Sta=4939.7,5030.3
XS Rating Curve= 0 ,0
Exp/Cntr=0.3,0.1

Type RM Length L Ch R = 1 ,1345    ,236,236,236
BEGIN DESCRIPTION:
Mapping XS 5018f72c
END DESCRIPTION:
XS GIS Cut Line= 4
      2290437.02     13384638.65      2290187.01     13384498.03
      2289707.85     13384581.36      2289615.57     13384642.88
#Sta/Elev= 30
  4541.9  355.97    4557  356.12  4578.7  354.71  4600.4  353.96  4632.3  353.63
  4644.4  352.54    4703  350.95  4718.9  349.83  4724.7     350  4805.6  347.44
  4815.8  346.46  4821.6  346.83  4825.5  346.39  4878.8  345.44  4899.1  344.06
  4919.4  343.39  4939.7  343.55  4971.5  342.58  4997.6  341.62  5000.3  341.12
  5010.7  342.06  5026.1  342.61  5031.1  342.83  5183.3  346.51  5244.6  348.76
  5294.9  349.63  5312.6  350.69  5339.7  351.05  5350.8  351.89    5426  353.84
#Mann= 5 ,-1 , 0
  4541.9     .05       0  4971.5     .03       0  5031.1     .05       0
  5244.6     .08       0  5350.8      .1       0
Bank Sta=4971.5,5026.1
XS Rating Curve= 0 ,0
Exp/Cntr=0.3,0.1

Type RM Length L Ch R = 1 ,1109    ,237,237,237
BEGIN DESCRIPTION:
Mapping XS 3806d781
END DESCRIPTION:
XS GIS Cut Line= 2
      2290304.42     13384357.58      2289710.63     13384227.37
#Sta/Elev= 30
  4705.6  349.99  4722.7  350.22  4735.2  349.37  4753.4  349.16  4822.8  346.25
  4845.5  346.28  4855.8  345.28  4876.9  344.89  4915.6   343.3  4947.9  343.09
  4958.2   342.1  4969.6  341.79  4978.6  341.38  5040.1  341.08  5059.4  340.66
  5062.1  340.16  5065.4  340.66    5081  341.29  5106.2   341.1  5132.2  341.71
  5183.4   342.9    5199  343.93  5214.1  344.05  5224.3  344.85  5242.8  345.51
  5255.1  345.42  5290.6  346.74  5296.8  346.61  5306.2   347.6  5313.5  347.61
#Mann= 4 ,-1 , 0
  4705.6     .05       0  4978.6     .03       0  5132.2     .05       0
  5290.6     .08       0
Bank Sta=4969.6,5132.2
XS Rating Curve= 0 ,0
Exp/Cntr=0.3,0.1

Type RM Length L Ch R = 1 ,872     ,434,434,434
BEGIN DESCRIPTION:
UNT076 IN SUCR 2.0
END DESCRIPTION:
XS GIS Cut Line= 2
      2290278.41     13384196.13       2289701.5     13384040.21
#Sta/Elev= 30
  4638.9  350.72  4660.4  350.11  4670.7  348.78  4738.6  346.74  4747.5  346.34
  4763.9  345.72    4795  345.78  4839.6  343.93  4884.2  341.54  4889.3  341.49
  4898.6  342.93  4908.9  342.18  4918.9  340.66    4924  340.99  4940.6   340.2
  4950.4  340.46  4958.7   339.9  4963.9  339.89  4998.6  339.45  5003.5  338.59
  5038.5  339.84  5041.5  339.87  5078.4  340.29  5126.5  341.75  5152.1  343.17
  5192.8  343.44  5209.3  344.11  5219.7  345.21  5232.7  344.72  5236.5  345.33
#Mann= 9 ,-1 , 0
  4638.9     .05       0  4738.6     .08       0  4747.5     .05       0
  4839.6      .1       0  4940.6     .12       0  4958.7     .07       0
  5038.5     .12       0  5041.5     .08       0  5152.1      .1       0
Bank Sta=4963.9,5041.5
XS Rating Curve= 0 ,0
Exp/Cntr=0.3,0.1

Type RM Length L Ch R = 1 ,438     ,128,128,128
BEGIN DESCRIPTION:
Mapping XS ae9ca0bf
END DESCRIPTION:
XS GIS Cut Line= 5
      2290171.85     13384017.35      2289911.44     13383708.33
      2289845.46     13383680.55      2289810.74     13383704.85
      2289588.84     13384072.38
#Sta/Elev= 30
  4521.7  345.75  4724.6  339.79  4758.7   338.8  4785.6  338.92  4801.6  337.92
  4893.9  336.98  4901.6  337.12  4922.5  336.17  4924.8  334.19  4944.3  333.24
  4951.3  331.94  4954.6  332.44    5036  333.02  5038.6  334.02  5043.9  334.02
  5051.6  335.09  5057.5  337.77  5088.5  338.65  5109.9  340.34    5118  340.09
  5168.1  341.62  5182.3   342.6  5210.8  342.45  5255.7  343.59    5269  344.56
  5284.5  344.25  5290.4  345.18  5328.4  346.18  5364.1  346.56  5469.1  350.72
#Mann= 8 ,-1 , 0
  4521.7      .1       0  4724.6     .12       0  4785.6      .1       0
  4893.9     .07       0  5057.5      .1       0    5118     .12       0
  5255.7     .05       0  5328.4      .1       0
Bank Sta=4901.6,5057.5
XS Rating Curve= 0 ,0
Exp/Cntr=0.3,0.1

Type RM Length L Ch R = 1 ,310     ,246,246,246
BEGIN DESCRIPTION:
Mapping XS 6436ce1a
END DESCRIPTION:
XS GIS Cut Line= 4
      2290206.57     13383892.35      2289852.41     13383545.13
      2289786.44     13383569.44      2289512.13     13384034.71
#Sta/Elev= 30
  4473.4  345.67  4547.2  343.65    4625  340.31  4716.9  337.71  4794.6  336.68
  4808.5  335.74  4879.5  340.79  4907.8  341.07  4914.9  339.94  4921.9  340.59
  5006.3  340.82  5014.7  341.08    5020  339.58  5027.7  340.77  5039.7   340.9
  5044.7  340.15  5050.5  341.22  5066.2   339.8    5072  340.69  5081.8  339.37
  5087.7   340.5  5103.3  338.27  5117.9  337.86    5201  340.45  5327.7   344.7
  5380.4  345.23  5408.2  347.36    5439   347.2  5470.4  348.32  5579.8  351.65
#Mann= 5 ,-1 , 0
  4473.4      .1       0  5006.3     .03       0  5044.7      .1       0
    5201     .05       0  5470.4      .1       0
#XS Ineff= 2 , 0
       0 4981.79  341.01 5055.71       0  341.25
Permanent Ineff=
       T       T
Bank Sta=5014.7,5039.7
XS Rating Curve= 0 ,0
Exp/Cntr=0.3,0.1

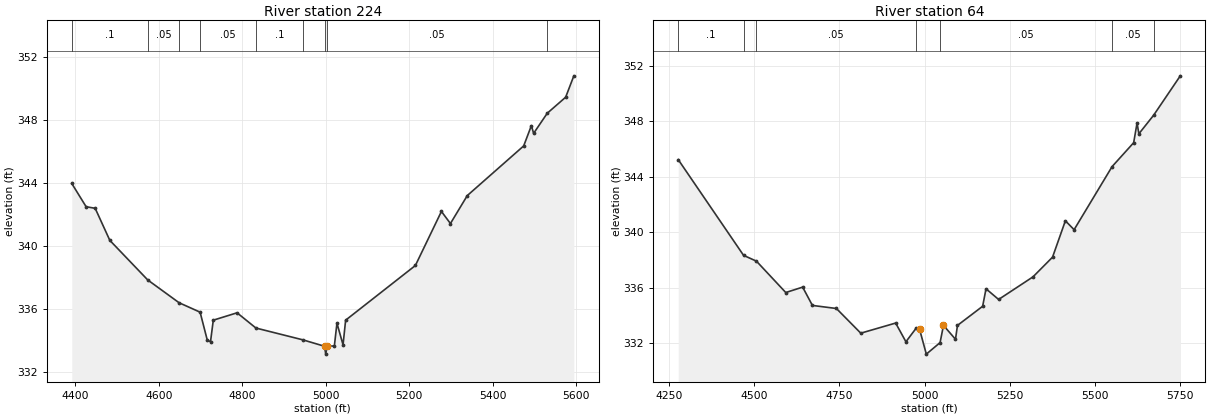
Type RM Length L Ch R = 1 ,224     ,160,160,160
BEGIN DESCRIPTION:
Mapping XS 6436ce1a
END DESCRIPTION:
XS GIS Cut Line= 4
      2290180.62     13383802.89      2289857.85     13383428.77
       2289628.9     13383598.04      2289465.07     13383989.71
#Sta/Elev= 30
  4391.1  343.98  4425.5   342.5  4447.2   342.4  4482.3  340.36  4573.2  337.84
  4648.3  336.39  4698.7  335.79  4716.1  333.99  4723.7  333.92  4730.3  335.28
  4787.3  335.75  4832.5  334.78  4944.8  334.03    4997  333.62  4999.8  333.12
    5003  333.62  5020.5  333.64  5026.7  335.09  5041.3  333.71  5047.5  335.28
  5214.7  338.76  5277.1   342.2  5298.7  341.43  5339.1  343.21  5474.3  346.37
  5492.7  347.66  5498.1  347.17  5530.8  348.45  5574.9  349.47  5594.5  350.83
#Mann= 9 ,-1 , 0
  4391.1      .1       0  4573.2     .05       0  4648.3      .1       0
  4698.7     .05       0  4832.5      .1       0  4944.8     .05       0
    4997     .03       0    5003     .05       0  5530.8      .1       0
Bank Sta=4997,5003
XS Rating Curve= 0 ,0
Exp/Cntr=0.3,0.1

Type RM Length L Ch R = 1 ,64      ,0,0,0
BEGIN DESCRIPTION:
UNT076 IN SUCR 1.0
END DESCRIPTION:
XS GIS Cut Line= 4
      2290216.97     13383781.21      2289862.82     13383357.63
      2289602.41     13383371.52      2289394.08     13383996.51
#Sta/Elev= 30
  4278.1  345.22  4469.6  338.32  4507.4   337.9  4593.3  335.64  4642.8  336.03
  4671.4  334.71  4741.7  334.49  4813.2  332.71  4915.4  333.44  4945.5  332.09
  4975.5  333.07  4985.5  332.99  5005.3   331.2  5045.6  332.03  5055.6  333.27
  5090.8  332.27  5096.6  333.27  5170.4  334.65  5180.3  335.91  5217.2  335.14
    5318  336.77  5375.3  338.19  5412.9  340.81  5438.5  340.17  5549.9  344.72
  5613.1  346.44    5623  347.86  5628.3  347.08  5671.6  348.42  5749.8  351.26
#Mann= 7 ,-1 , 0
  4278.1      .1       0  4469.6     .05       0  4507.4     .05       0
  4975.5     .03       0  5045.6     .05       0  5549.9     .05       0
  5671.6      .1       0
Bank Sta=4985.5,5055.6
XS Rating Curve= 0 ,0
Exp/Cntr=0.3,0.1

Chan Stop Cuts=-1
Use User Specified Reach Order=0
Composite Channel Slope=5