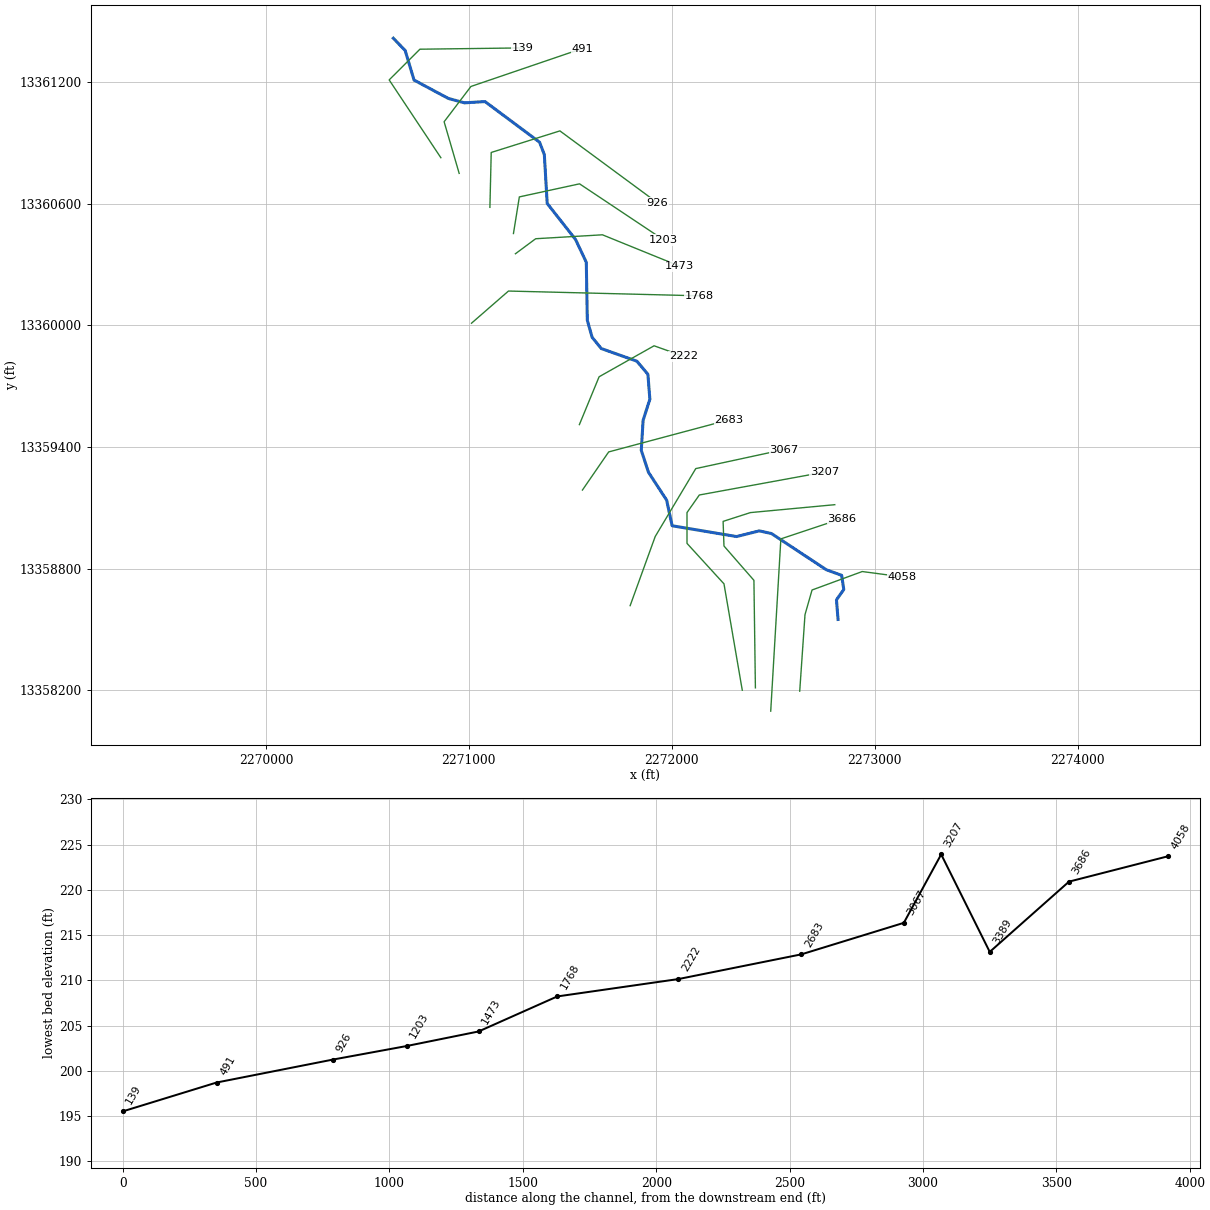
--- UNT077 IN SUCR.prj (project) ---

Proj Title=UNT077 IN SUCR Base Level Engineering
Current Plan=p01
Default Exp/Contr=0.3,0.1
English Units
Geom File=g01
Flow File=f01
Plan File=p01
Y Axis Title=Elevation
X Axis Title(PF)=Main Channel Distance
X Axis Title(XS)=Station
BEGIN DESCRIPTION:
UNT077 IN SUCR
END DESCRIPTION:
DSS Export Rating Curves= 0
DSS Export Rating Curve Sorted= 0
DSS Export Volume Flow Curves= 0
DXF OffsetX= 0
DXF OffsetY= 0
DXF ScaleX= 1
DXF ScaleY= 10

--- UNT077 IN SUCR.p01 (plan) ---

Plan Title=Multiple Run
Short Identifier=Multiple
Geom File=g01
Flow File=f01
Subcritical Flow
K Sum by GR= 0
Std Step Tol= 0.01
Critical Tol= 0.01
Num of Std Step Trials= 20
Max Error Tol= 0.3
Flow Tol Ratio= 0.001
Split Flow NTrial= 30
Split Flow Tol= 0.02
Split Flow Ratio= 0.02
Log Output Level= 0
Friction Slope Method= 1
Unsteady Friction Slope Method= 2
Unsteady Bridges Friction Slope Method= 1
Parabolic Critical Depth
Global Vel Dist=  1 , 1 , 1
Global Log Level= 0
CheckData=True
Encroach Param= -1, 0, 0, 0
BEGIN DESCRIPTION:
Multiple Run
END DESCRIPTION:

--- UNT077 IN SUCR.f01 (steady flow) ---

Flow Title=Multiple
Program Version=4.10
Number of Profiles= 7
Profile Names=10-year,25-year,50-year,1pct_min,100-year,1pct_plu,500-year
River Rch & RM=UNT077 IN SUCR,Reach-1         ,4058
     235     326     402     365     493     667     753
Boundary for River Rch & Prof#=UNT077 IN SUCR,Reach-1         , 1
Up Type= 0
Dn Type= 3
Dn Slope=0.01
Boundary for River Rch & Prof#=UNT077 IN SUCR,Reach-1         , 2
Up Type= 0
Dn Type= 3
Dn Slope=0.01
Boundary for River Rch & Prof#=UNT077 IN SUCR,Reach-1         , 3
Up Type= 0
Dn Type= 3
Dn Slope=0.01
Boundary for River Rch & Prof#=UNT077 IN SUCR,Reach-1         , 4
Up Type= 0
Dn Type= 3
Dn Slope=0.01
Boundary for River Rch & Prof#=UNT077 IN SUCR,Reach-1         , 5
Up Type= 0
Dn Type= 3
Dn Slope=0.01
Boundary for River Rch & Prof#=UNT077 IN SUCR,Reach-1         , 6
Up Type= 0
Dn Type= 3
Dn Slope=0.01
Boundary for River Rch & Prof#=UNT077 IN SUCR,Reach-1         , 7
Up Type= 0
Dn Type= 3
Dn Slope=0.01
DSS Import GetInterval= 0
DSS Import GetPeak= 0
DSS Import FillOption= 0

--- UNT077 IN SUCR.g01 (geometry) ---

Geom Title=Existing Conditions
Program Version=4.10

River Reach=UNT077 IN SUCR  ,Reach-1
Reach XY= 30
      2272819.55     13358549.23      2272811.73     13358646.13
      2272847.85     13358697.05      2272837.43      13358766.8
      2272761.56      13358794.6       2272491.2     13358973.22
       2272431.3     13358986.24        2272319.     13358958.25
      2272001.81     13359011.55      2271974.73     13359137.94
      2271885.14     13359275.44      2271849.73     13359383.77
      2271858.75     13359531.69      2271892.09     13359635.85
      2271882.37     13359758.77       2271828.2     13359823.35
       2271652.5     13359885.85      2271607.37     13359941.41
      2271583.75     13360025.44      2271578.75     13360311.41
      2271525.98     13360423.56      2271386.05     13360601.69
      2271371.94      13360842.6       2271348.5     13360903.79
      2271079.63     13361104.31      2270978.29     13361098.06
      2270898.94     13361119.76      2270729.75     13361210.45
      2270686.09     13361356.19      2270627.72     13361416.86

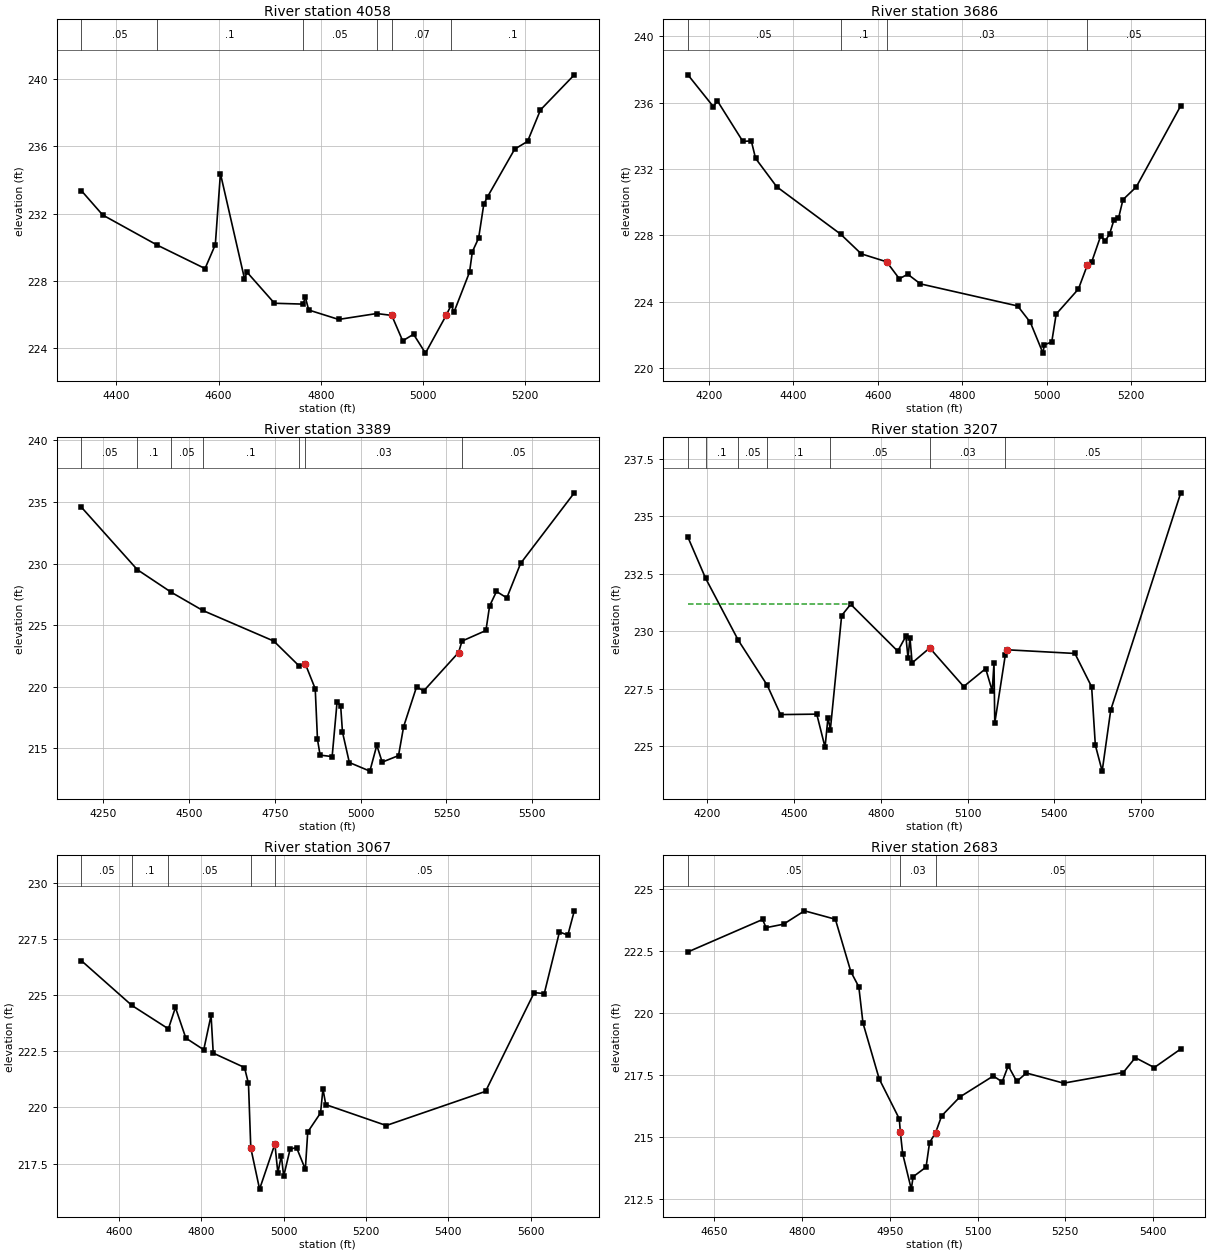
Type RM Length L Ch R = 1 ,4058    ,372,372,372
BEGIN DESCRIPTION:
UNT077 IN SUCR 5.0
END DESCRIPTION:
XS GIS Cut Line= 5
      2272630.62     13358195.39      2272656.66     13358573.02
      2272691.38     13358694.55      2272938.78     13358785.69
      2273133.38     13358759.75
#Sta/Elev= 30
  4331.5  233.36  4373.1  231.92    4480  230.13  4573.5  228.74  4593.6  230.16
  4603.6  234.38  4650.7  228.14  4655.8  228.52  4709.4  226.68  4765.1  226.63
  4769.9  227.03  4776.4  226.28    4835  225.72  4909.5  226.07    4939  225.96
  4960.4  224.45  4981.7  224.84    5005  223.72  5045.7  225.97  5055.5  226.58
  5060.8  226.15  5091.3  228.53  5096.8  229.74  5109.1  230.55  5119.2  232.56
  5126.7  233.01  5179.7  235.83  5204.9  236.29  5230.2  238.16  5296.4  240.24
#Mann= 6 ,-1 , 0
  4331.5     .05       0    4480      .1       0  4765.1     .05       0
  4909.5      .1       0    4939     .07       0  5055.5      .1       0
Bank Sta=4939,5045.7
XS Rating Curve= 0 ,0
Exp/Cntr=0.3,0.1

Type RM Length L Ch R = 1 ,3686    ,297,297,297
BEGIN DESCRIPTION:
UNT077 IN SUCR 4.0
END DESCRIPTION:
XS GIS Cut Line= 3
      2272487.72     13358096.87      2272537.72     13358946.85
      2272837.73     13359046.86
#Sta/Elev= 30
  4150.2  237.67  4210.3  235.76  4220.3  236.09  4280.4  233.66  4300.4  233.69
  4310.5  232.64  4360.6  230.93  4511.8  228.08  4560.9  226.89    4621  226.41
  4651.1  225.39  4671.1  225.66  4701.1  225.08  4931.5  223.75  4961.6  222.76
  4991.4  220.91  4994.6  221.41  5012.2  221.58  5022.7  223.26  5075.4  224.77
  5096.5  226.21  5107.1  226.42  5128.1  227.96  5138.7  227.66  5149.2  228.08
  5159.8  228.95  5170.3  229.02  5180.9  230.15  5212.5  230.92  5317.9  235.81
#Mann= 4 ,-1 , 0
  4150.2     .05       0  4511.8      .1       0    4621     .03       0
  5096.5     .05       0
Bank Sta=4621,5096.5
XS Rating Curve= 0 ,0
Exp/Cntr=0.3,0.1

Type RM Length L Ch R = 1 ,3389    ,182,182,182
BEGIN DESCRIPTION:
Mapping XS f819fee0
END DESCRIPTION:
XS GIS Cut Line= 6
      2272412.21     13358211.72      2272404.92     13358742.29
      2272257.36     13358911.56      2272253.02     13359033.09
      2272387.56     13359076.49      2272803.47     13359115.48
#Sta/Elev= 30
  4186.8  234.58  4349.6  229.51  4448.2  227.68  4540.1   226.2  4747.3  223.71
  4820.3  221.71  4839.4  221.83  4867.9  219.84  4874.5  215.72  4882.1  214.45
  4917.2  214.33  4931.5  218.75    4942  218.46  4947.3  216.32  4967.3  213.85
  5027.1  213.15  5047.3  215.25    5063  213.88  5110.6  214.41  5125.5  216.77
  5163.1  219.99  5184.1  219.67  5285.5  222.78  5295.5  223.71  5365.2  224.57
  5375.9  226.56    5396  227.74  5426.1  227.22  5466.3  230.02  5622.7  235.75
#Mann= 7 ,-1 , 0
  4186.8     .05       0  4349.6      .1       0  4448.2     .05       0
  4540.1      .1       0  4820.3     .05       0  4839.4     .03       0
  5295.5     .05       0
Bank Sta=4839.4,5285.5
XS Rating Curve= 0 ,0
Exp/Cntr=0.3,0.1

Type RM Length L Ch R = 1 ,3207    ,140,140,140
BEGIN DESCRIPTION:
UNT077 IN SUCR 3.0
END DESCRIPTION:
XS GIS Cut Line= 6
      2272347.53     13358199.98      2272257.36     13358724.93
      2272075.06     13358924.58      2272075.06     13359076.49
      2272135.83      13359163.3      2272752.15     13359276.15
#Sta/Elev= 30
    4134   234.1  4195.2  232.31  4308.3  229.61  4407.9  227.66  4454.1  226.38
  4579.1   226.4  4607.7  224.96  4617.9  226.25  4626.1  225.73  4665.1  230.69
  4696.3  231.18  4858.8  229.14  4886.9  229.79  4894.3  228.85  4901.1  229.72
  4908.5  228.63  4969.3  229.28  5086.6   227.6  5162.6  228.38  5185.2  227.41
  5191.3  228.61    5194  226.01  5230.6  228.99  5236.8   229.2  5470.8  229.04
  5528.6  227.59  5541.4  225.05    5565  223.92  5594.6  226.58  5836.5  236.03
#Mann= 7 ,-1 , 0
    4134     .05       0  4195.2      .1       0  4308.3     .05       0
  4407.9      .1       0  4626.1     .05       0  4969.3     .03       0
  5230.6     .05       0
#XS Ineff= 2 , 0
       0 4694.44   231.2 5381.94       0  229.03
Permanent Ineff=
       T       T
Bank Sta=4969.3,5236.8
XS Rating Curve= 0 ,0
Exp/Cntr=0.3,0.1

Type RM Length L Ch R = 1 ,3067    ,384,384,384
BEGIN DESCRIPTION:
Mapping XS b2a67016
END DESCRIPTION:
XS GIS Cut Line= 4
      2271794.88     13358617.41      2271918.34     13358958.39
      2272118.24     13359293.52      2272553.03     13359387.53
#Sta/Elev= 30
  4508.6  226.52  4631.3  224.53  4719.9  223.49    4737  224.44  4762.3  223.08
  4805.8  222.56  4823.6  224.09  4828.9  222.41  4904.8  221.77  4914.5  221.06
 4920.14  218.19  4941.5  216.36  4978.7  218.37  4985.9  217.08  4994.3  217.85
  5000.1  216.94  5015.7  218.14  5031.3  218.21  5052.7  217.24  5058.5   218.9
  5089.7  219.75  5095.5  220.82  5102.3  220.12  5249.3  219.19  5490.7  220.71
  5608.8   225.1  5633.3  225.06  5670.2   227.8  5690.6  227.66  5706.3  228.74
#Mann= 5 ,-1 , 0
  4508.6     .05       0  4631.3      .1       0  4719.9     .05       0
 4920.14     .03       0  4978.7     .05       0
Bank Sta=4920.14,4978.7
XS Rating Curve= 0 ,0
Exp/Cntr=0.3,0.1

Type RM Length L Ch R = 1 ,2683    ,461,461,461
BEGIN DESCRIPTION:
UNT077 IN SUCR 2.0
END DESCRIPTION:
XS GIS Cut Line= 3
      2271559.69     13359187.68      2271689.04     13359375.83
      2272282.77     13359534.55
#Sta/Elev= 30
  4604.7  222.46  4732.4  223.77  4738.4  223.44  4768.2  223.58  4804.1  224.12
  4856.9  223.78  4883.4  221.66    4897  221.05  4904.1  219.59  4931.9  217.33
  4966.2  215.72 4968.06  215.17    4972  214.31  4986.7  212.88  4989.9  213.38
    5012  213.77    5018  214.76  5028.3  215.16  5038.7  215.84  5069.7   216.6
    5127  217.45  5142.2  217.21  5152.5  217.86  5167.1  217.23  5183.6  217.57
  5247.2  217.16  5349.2  217.59  5369.9  218.19  5402.3  217.79  5447.6  218.54
#Mann= 3 , 0 , 0
  4604.7     .05       0 4968.06     .03       0  5028.3     .05       0
Bank Sta=4968.06,5028.3
XS Rating Curve= 0 ,0
Exp/Cntr=0.3,0.1

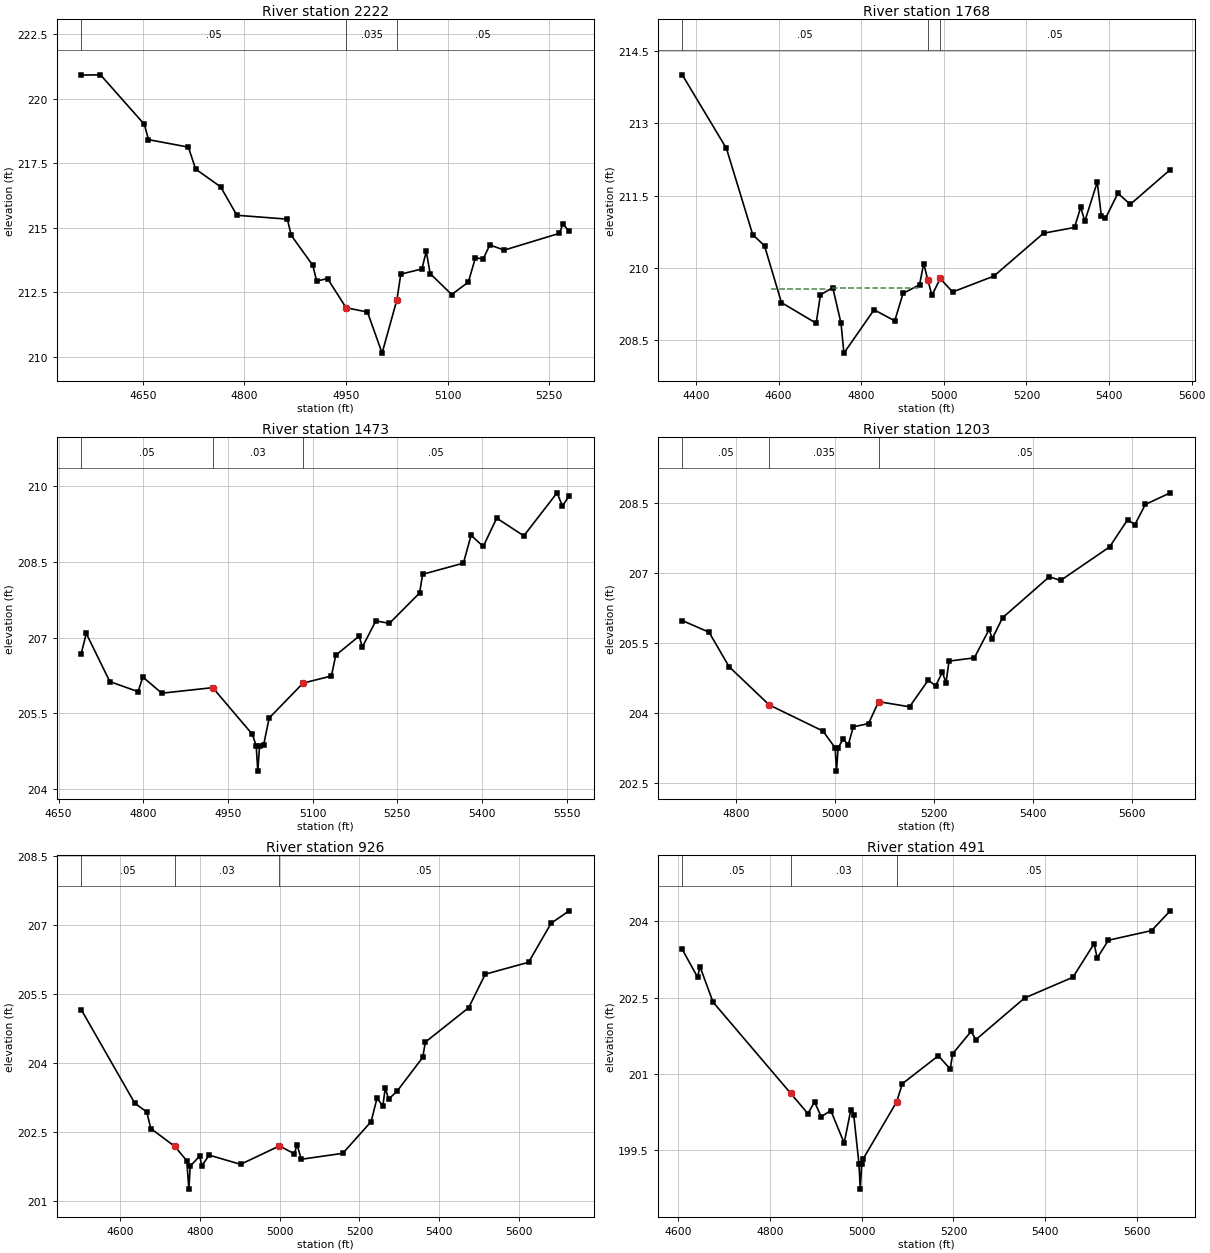
Type RM Length L Ch R = 1 ,2222    ,454,454,454
BEGIN DESCRIPTION:
Mapping XS 0bd457c3
END DESCRIPTION:
XS GIS Cut Line= 4
      2271544.69     13359510.54       2271641.9     13359746.63
      2271912.74     13359899.41        2272058.     13359847.59
#Sta/Elev= 30
  4558.9  220.92  4587.4  220.93  4652.2  219.01  4658.2  218.42  4717.1  218.13
  4727.9  217.28  4764.8  216.59  4788.8  215.49  4863.3  215.34  4869.1  214.71
  4900.9  213.55  4906.6  212.94  4922.6  213.04    4950  211.91  4981.6  211.74
  5003.2  210.15  5025.1  212.22  5030.8  213.21    5062  213.41  5068.4  214.09
  5074.2  213.23    5106  212.42  5130.5   212.9  5141.1  213.85  5152.3  213.79
  5162.3  214.34  5183.5  214.14  5264.9  214.79  5270.2  215.15  5279.4  214.87
#Mann= 3 , 0 , 0
  4558.9     .05       0    4950    .035       0  5025.1     .05       0
#XS Ineff= 2 , 0
       0                 5068.33       0  214.07
Permanent Ineff=
       F       T
Bank Sta=4950,5025.1
XS Rating Curve= 0 ,0
Exp/Cntr=0.3,0.1

Type RM Length L Ch R = 1 ,1768    ,295,295,295
BEGIN DESCRIPTION:
Mapping XS c046f52d
END DESCRIPTION:
XS GIS Cut Line= 3
      2271012.89     13360010.78      2271195.17     13360169.55
      2272134.35     13360146.07
#Sta/Elev= 30
  4366.9  214.01  4473.9  212.48  4537.5  210.69    4566  210.46    4607  209.28
  4691.2  208.85  4701.2  209.44  4731.2  209.59  4751.2  208.85  4758.2  208.23
  4831.2  209.13  4881.3   208.9  4901.3  209.47  4941.3  209.65  4951.3  210.09
  4961.3  209.75  4971.3  209.43  4991.3  209.78  5021.3   209.5  5121.3  209.83
  5241.4  210.72  5316.4  210.84  5331.4  211.26  5341.4  210.97  5371.4  211.78
  5381.4  211.08  5391.4  211.03  5421.4  211.55  5451.4  211.32  5548.1  212.04
#Mann= 3 , 0 , 0
  4366.9     .05       0  4961.3    .035       0  4991.3     .05       0
#XS Ineff= 2 ,-1
 4581.55 4716.56  209.57  4728.3 4941.09  209.59
Permanent Ineff=
       T       T
Bank Sta=4961.3,4991.3
XS Rating Curve= 0 ,0
Exp/Cntr=0.3,0.1

Type RM Length L Ch R = 1 ,1473    ,270,270,270
BEGIN DESCRIPTION:
Mapping XS d3076e44
END DESCRIPTION:
XS GIS Cut Line= 4
      2271229.45     13360353.51      2271329.38     13360427.66
      2271658.25     13360447.01       2272038.7     13360292.25
#Sta/Elev= 30
  4689.9  206.68  4698.9  207.08  4740.6  206.13  4790.7  205.93  4799.1  206.22
  4832.7   205.9  4922.9  206.01    4993  205.09    5000  204.86  5002.8  204.36
    5006  204.86    5013  204.87    5023  205.41  5083.1   206.1  5133.2  206.24
    5141  206.65  5182.5  207.03  5187.9  206.81    5212  207.33    5236  207.28
  5289.5  207.88  5294.9  208.25  5367.1  208.47  5380.7  209.02  5402.3   208.8
  5426.1  209.36  5474.2  209.01  5533.1  209.86  5542.6   209.6  5554.5   209.8
#Mann= 3 , 0 , 0
  4689.9     .05       0  4922.9     .03       0  5083.1     .05       0
Bank Sta=4922.9,5083.1
XS Rating Curve= 0 ,0
Exp/Cntr=0.3,0.1

Type RM Length L Ch R = 1 ,1203    ,277,277,277
BEGIN DESCRIPTION:
Mapping XS 783a836d
END DESCRIPTION:
XS GIS Cut Line= 4
      2271219.75     13360453.41      2271248.78     13360634.01
      2271545.41      13360698.5      2271960.87     13360421.52
#Sta/Elev= 30
  4691.4  205.98  4745.5  205.73    4786  204.99  4867.1  204.17  4975.6  203.61
  5000.3  203.25    5003  202.75  5006.3  203.25  5016.5  203.44  5026.7  203.31
    5037   203.7  5067.7  203.77  5088.1  204.24  5150.6  204.13  5188.3   204.7
  5203.3  204.58  5216.7  204.87  5224.3  204.65  5230.3  205.11  5281.4  205.18
  5311.4  205.79  5317.5  205.59  5338.5  206.04    5433  206.92  5455.7  206.84
  5554.8  207.56  5590.9  208.14  5605.9  208.04  5626.9  208.47  5677.2  208.72
#Mann= 3 , 0 , 0
  4691.4     .05       0  4867.1    .035       0  5088.1     .05       0
Bank Sta=4867.1,5088.1
XS Rating Curve= 0 ,0
Exp/Cntr=0.3,0.1

Type RM Length L Ch R = 1 ,926     ,435,435,435
BEGIN DESCRIPTION:
Mapping XS 9d543c5e
END DESCRIPTION:
XS GIS Cut Line= 4
      2271103.69     13360582.46      2271110.14     13360853.26
      2271448.68     13360959.66       2271929.1     13360604.98
#Sta/Elev= 30
  4502.7  205.16  4637.1  203.12  4667.1  202.93  4677.1  202.57  4737.2  202.18
  4767.2  201.87  4772.6  201.25  4775.9  201.75  4799.7  201.97    4805  201.76
  4823.5  201.99  4902.2  201.79  4999.4  202.19    5037  202.02  5043.6  202.22
  5054.1   201.9  5158.4  202.03  5229.3  202.72    5244  203.23  5258.6  203.06
  5264.8  203.45  5273.2  203.21  5294.1  203.38  5358.8  204.12    5365  204.45
  5473.7   205.2  5515.4  205.93    5624  206.19  5680.4  207.04  5725.6  207.31
#Mann= 3 , 0 , 0
  4502.7     .05       0  4737.2     .03       0  4999.4     .05       0
Bank Sta=4737.2,4999.4
XS Rating Curve= 0 ,0
Exp/Cntr=0.3,0.1

Type RM Length L Ch R = 1 ,491     ,352,352,352
BEGIN DESCRIPTION:
Mapping XS d9bde2ff
END DESCRIPTION:
XS GIS Cut Line= 4
      2270952.16     13360750.06        2270878.      13361004.8
      2271010.19      13361178.9      2271558.35     13361365.92
#Sta/Elev= 30
  4609.2  203.45  4642.6   202.9  4647.8  203.11  4676.2  202.41  4845.4  200.61
  4882.9  200.21  4897.4  200.44  4911.9  200.15  4932.8  200.27  4961.9  199.63
  4976.4  200.28  4982.7  200.19  4994.2  199.22    4997  198.72  5000.2  199.22
  5003.5  199.32  5076.2  200.44  5088.7   200.8    5167  201.35    5193  201.09
  5198.3  201.39  5238.4  201.83    5249  201.67    5355  202.49  5460.3   202.9
  5506.4  203.56  5513.2  203.28  5537.7  203.63  5631.7  203.82  5672.3  204.21
#Mann= 3 , 0 , 0
  4609.2     .05       0  4845.4     .03       0  5076.2     .05       0
Bank Sta=4845.4,5076.2
XS Rating Curve= 0 ,0
Exp/Cntr=0.3,0.1

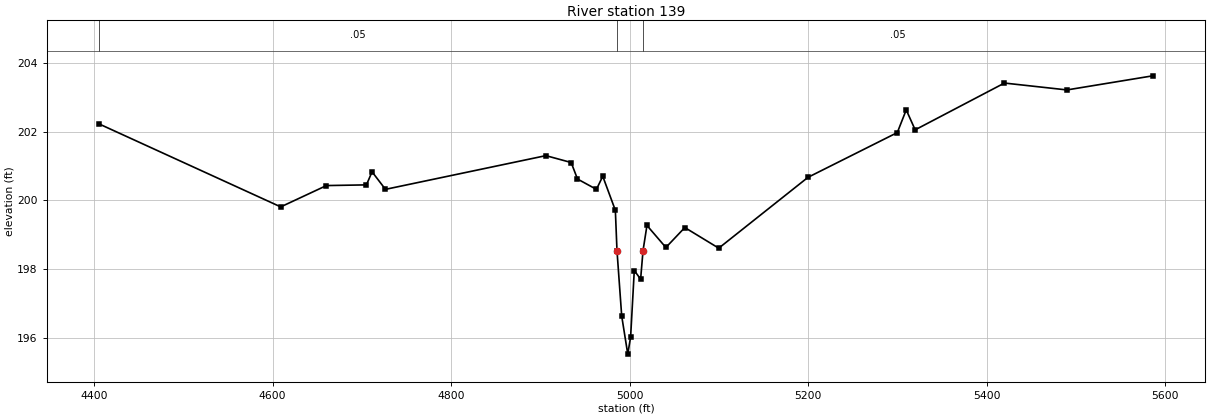
Type RM Length L Ch R = 1 ,139     ,0,0,0
BEGIN DESCRIPTION:
UNT077 IN SUCR 1.0
END DESCRIPTION:
XS GIS Cut Line= 4
      2270861.87     13360827.47      2270607.16     13361211.15
       2270758.7     13361362.68      2271263.82     13361369.12
#Sta/Elev= 30
  4405.9  202.22  4609.2  199.81  4660.4  200.43  4705.2  200.45  4711.5  200.83
  4726.5  200.32  4906.2   201.3  4934.5   201.1  4941.6  200.62  4962.8  200.32
  4969.9   200.7    4984  199.71 4985.83  198.54  4991.1  196.64  4997.9  195.53
  5001.1  196.03  5005.2  197.96  5012.3  197.71    5015  198.54  5019.4  199.27
  5040.6  198.63  5061.8  199.21  5099.8  198.61  5199.8  200.67  5299.8  201.97
  5309.8  202.63  5319.8  202.05  5419.8  203.41  5489.8  203.21  5585.9  203.62
#Mann= 3 , 0 , 0
  4405.9     .05       0 4985.83     .03       0    5015     .05       0
Bank Sta=4985.83,5015
XS Rating Curve= 0 ,0
Exp/Cntr=0.3,0.1

Chan Stop Cuts=-1
Use User Specified Reach Order=0
Composite Channel Slope=5