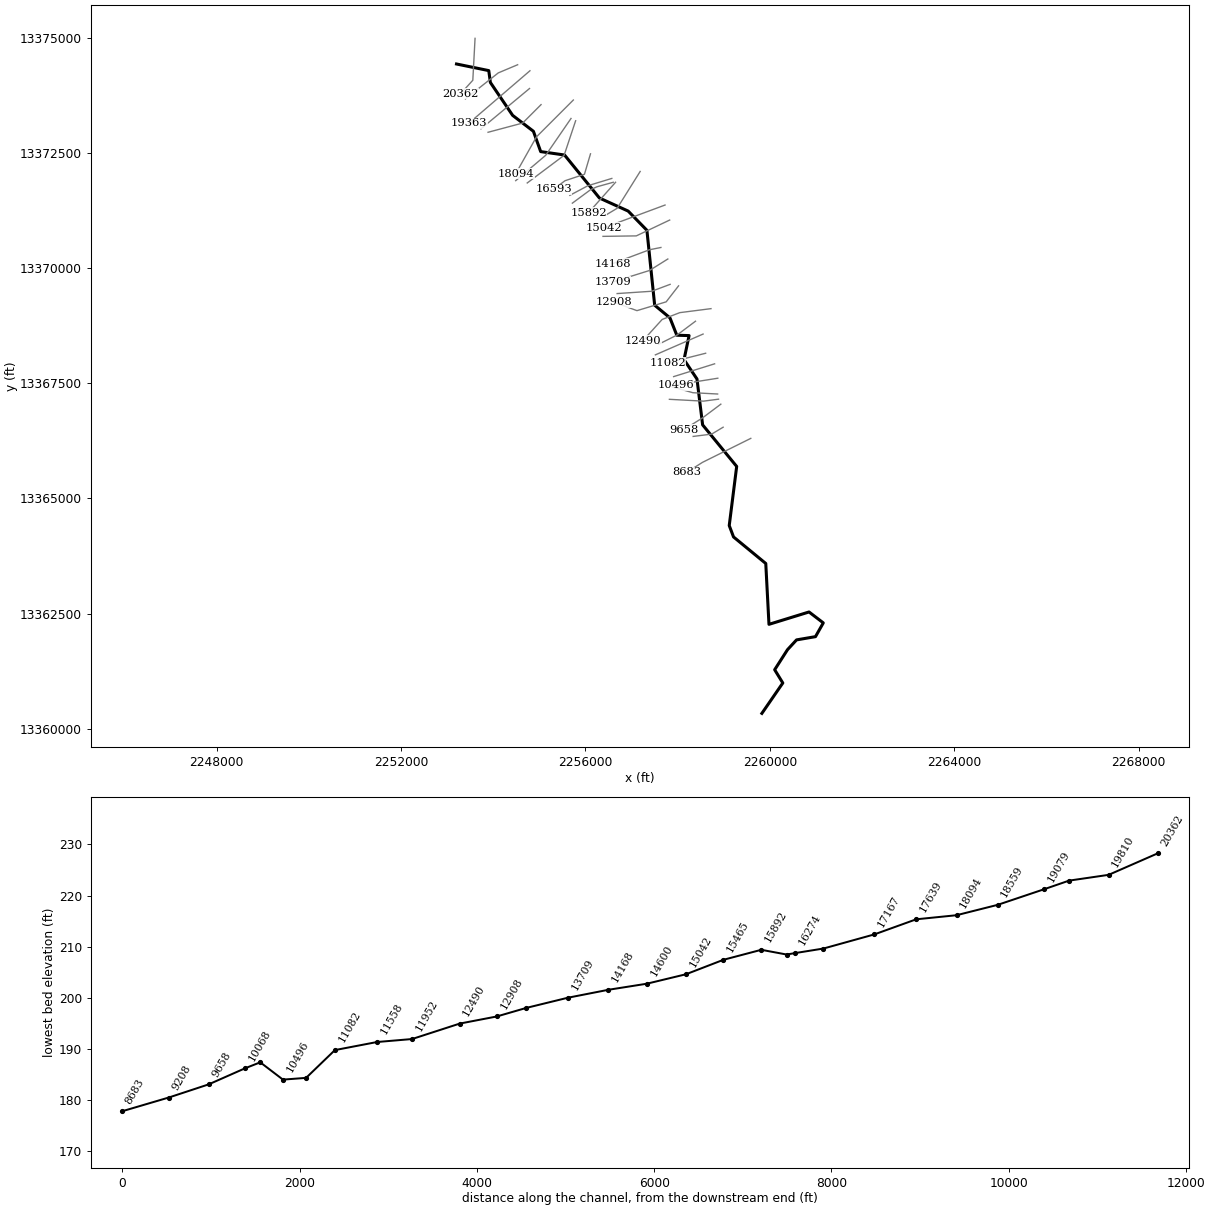
--- UNT078 IN SUCR.prj (project) ---

Proj Title=UNT078 IN SUCR Base Level Engineering
Current Plan=p01
Default Exp/Contr=0.3,0.1
English Units
Geom File=g01
Flow File=f01
Plan File=p01
Y Axis Title=Elevation
X Axis Title(PF)=Main Channel Distance
X Axis Title(XS)=Station
BEGIN DESCRIPTION:
UNT078 IN SUCR
END DESCRIPTION:
DSS Export Rating Curves= 0
DSS Export Rating Curve Sorted= 0
DSS Export Volume Flow Curves= 0
DXF OffsetX= 0
DXF OffsetY= 0
DXF ScaleX= 1
DXF ScaleY= 10

--- UNT078 IN SUCR.p01 (plan) ---

Plan Title=Multiple Run
Short Identifier=Multiple
Geom File=g01
Flow File=f01
Subcritical Flow
K Sum by GR= 0
Std Step Tol= 0.01
Critical Tol= 0.01
Num of Std Step Trials= 20
Max Error Tol= 0.3
Flow Tol Ratio= 0.001
Split Flow NTrial= 30
Split Flow Tol= 0.02
Split Flow Ratio= 0.02
Log Output Level= 0
Friction Slope Method= 1
Unsteady Friction Slope Method= 2
Unsteady Bridges Friction Slope Method= 1
Parabolic Critical Depth
Global Vel Dist=  1 , 1 , 1
Global Log Level= 0
CheckData=True
Encroach Param= -1, 0, 0, 0
BEGIN DESCRIPTION:
Multiple Run
END DESCRIPTION:

--- UNT078 IN SUCR.f01 (steady flow) ---

Flow Title=Multiple
Number of Profiles=7
Profile Names=10-year,25-year,50-year,1pct_min,100-year,1pct_plu,500-year
River Rch & RM= UNT078 IN SUCR,Reach-1,20362
     293     409     506     461     623     842     957
River Rch & RM= UNT078 IN SUCR,Reach-1,19079
     349     493     613     561     759    1027    1182
River Rch & RM= UNT078 IN SUCR,Reach-1,16274
     451     644     807     744    1006    1360    1586
River Rch & RM= UNT078 IN SUCR,Reach-1,12490
     504     720     905     835    1129    1527    1784
River Rch & RM= UNT078 IN SUCR,Reach-1,7667
     536     768     967     893    1208    1633    1914
River Rch & RM= UNT078 IN SUCR,Reach-1,2707
     544     780     982     907    1227    1659    1944
Boundary for River Rch & Prof#=UNT078 IN SUCR,Reach-1,1
Up Type=0
Dn Type=3
Dn Slope=0.005
Boundary for River Rch & Prof#=UNT078 IN SUCR,Reach-1,2
Up Type=0
Dn Type=3
Dn Slope=0.005
Boundary for River Rch & Prof#=UNT078 IN SUCR,Reach-1,3
Up Type=0
Dn Type=3
Dn Slope=0.005
Boundary for River Rch & Prof#=UNT078 IN SUCR,Reach-1,4
Up Type=0
Dn Type=3
Dn Slope=0.005
Boundary for River Rch & Prof#=UNT078 IN SUCR,Reach-1,5
Up Type=0
Dn Type=3
Dn Slope=0.005
Boundary for River Rch & Prof#=UNT078 IN SUCR,Reach-1,6
Up Type=0
Dn Type=3
Dn Slope=0.005
Boundary for River Rch & Prof#=UNT078 IN SUCR,Reach-1,7
Up Type=0
Dn Type=3
Dn Slope=0.005

--- UNT078 IN SUCR.g01 (geometry) ---

Geom Title=Existing Conditions
Program Version=4.10

River Reach=UNT078 IN SUCR  ,Reach-1
Reach XY= 30
      2253203.83     13374428.64      2253903.21     13374285.14
      2253938.28     13374027.65      2254421.31     13373313.62
      2254871.75     13372968.28      2255029.45     13372527.49
      2255547.22     13372453.36      2256304.18      13371520.2
      2256927.39     13371236.74      2257333.81     13370819.95
      2257502.26     13369194.02      2257833.45     13368919.58
      2257982.48     13368542.65      2258248.71     13368534.67
      2258138.69     13368012.78      2258420.11     13367592.83
      2258542.33     13366597.51      2259281.11     13365695.18
      2259119.68     13364412.67      2259213.04     13364165.29
      2259912.26     13363589.55      2259981.74     13362269.15
      2260850.71     13362537.19      2261159.98     13362300.56
      2260990.72     13362001.83       2260579.5     13361931.41
      2260383.62     13361718.98      2260105.29     13361283.84
      2260281.85     13360996.34      2259827.72     13360336.85

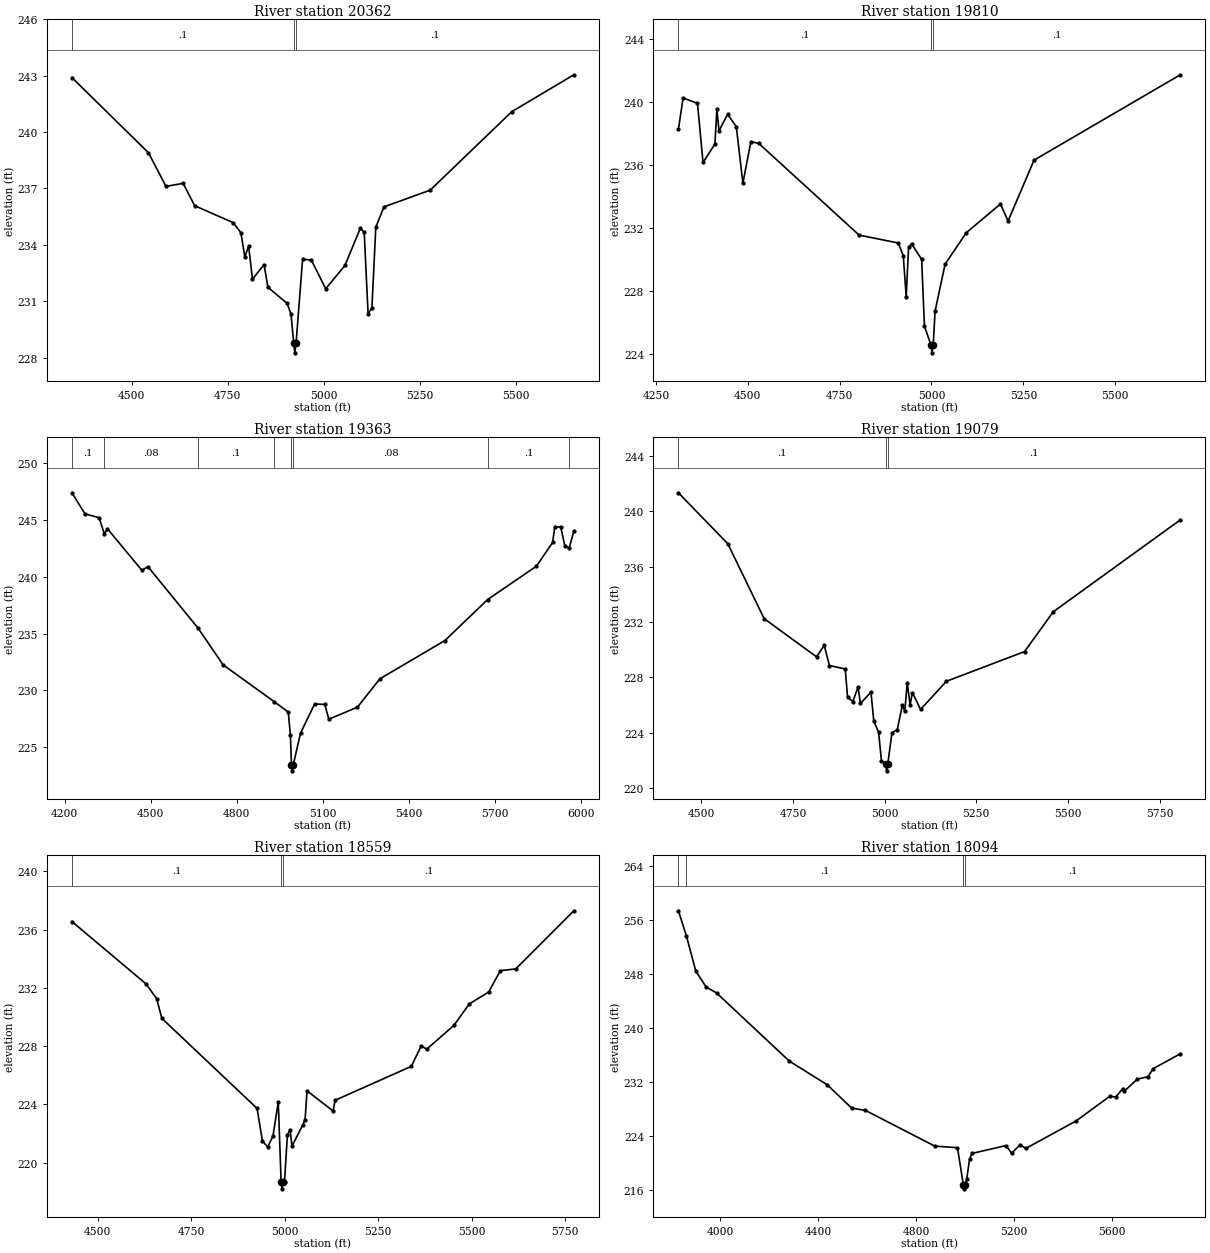
Type RM Length L Ch R = 1 ,20362   ,552,552,552
BEGIN DESCRIPTION:
UNT078 IN SUCR 41.0
END DESCRIPTION:
XS GIS Cut Line= 3
       2253605.8     13374985.38      2253557.19     13374075.64
      2253293.28     13373783.95
#Sta/Elev= 30
  4345.2   242.9    4544   238.9  4589.7  237.11  4634.1  237.27  4664.2  236.08
  4764.3  235.18  4784.4  234.64  4794.4  233.36  4804.4  233.93  4814.4  232.17
  4844.4  232.95  4854.5  231.74  4904.5  230.88  4914.5  230.31  4921.6  228.75
  4924.3  228.25  4927.6  228.75  4944.6  233.23  4967.4  233.19  5004.7  231.66
  5054.7   232.9  5094.8  234.89  5104.8  234.66  5114.8  230.33  5124.8  230.65
  5134.9  234.94  5156.2  236.02  5276.3  236.91  5488.5  241.09  5649.6  243.05
#Mann= 3 ,-1 , 0
  4345.2      .1       0  4921.6     .07       0  4927.6      .1       0
Bank Sta=4921.6,4927.6
XS Rating Curve= 0 ,0
Exp/Cntr=0.3,0.1

Type RM Length L Ch R = 1 ,19810   ,447,447,447
BEGIN DESCRIPTION:
UNT078 IN SUCR 40.0
END DESCRIPTION:
XS GIS Cut Line= 3
      2254529.43     13374412.46      2254109.27     13374235.36
      2253395.54     13373670.61
#Sta/Elev= 30
  4311.2  238.27  4323.9  240.28  4363.1  239.93  4378.2  236.17  4410.5  237.34
  4415.9  239.55  4421.6  238.18  4445.1  239.24  4468.8  238.44  4486.7  234.85
  4508.4   237.5  4530.1  237.38    4803  231.55  4909.4  231.05  4923.2  230.25
  4931.2  227.62  4937.6  230.77  4945.7     231  4973.2  230.01  4980.9  225.75
  4998.7  224.56  5001.5  224.06  5004.7  224.56  5009.8  226.71    5037   229.7
  5094.7   231.7  5187.7  233.53  5208.5  232.45  5279.2  236.32  5677.3  241.75
#Mann= 3 ,-1 , 0
  4311.2      .1       0  4998.7     .07       0  5004.7      .1       0
Bank Sta=4998.7,5004.7
XS Rating Curve= 0 ,0
Exp/Cntr=0.3,0.1

Type RM Length L Ch R = 1 ,19363   ,284,284,284
BEGIN DESCRIPTION:
UNT078 IN SUCR 39.0
END DESCRIPTION:
XS GIS Cut Line= 2
      2254796.63     13374281.79      2253468.89     13373141.49
#Sta/Elev= 30
  4225.4  247.38  4270.7  245.53  4320.1  245.19  4338.7  243.74  4348.6  244.23
  4469.4  240.56  4490.2  240.89  4665.7  235.46  4752.5  232.25  4930.3  229.02
  4979.6   228.1  4987.3  226.06  4990.9  223.43  4993.7  222.93  4996.9  223.43
  5022.4  226.24  5071.8  228.81  5107.1  228.77  5121.2  227.47  5221.1  228.53
    5299  231.02  5526.1  234.39  5674.8  237.99  5845.3  240.93  5901.5  243.01
  5909.1  244.41    5930  244.35  5944.3   242.7  5959.2  242.53  5975.6  243.98
#Mann= 8 ,-1 , 0
  4225.4      .1       0  4338.7     .08       0  4665.7      .1       0
  4930.3     .08       0  4990.9     .07       0  4996.9     .08       0
  5674.8      .1       0  5959.2     .08       0
Bank Sta=4990.9,4996.9
XS Rating Curve= 0 ,0
Exp/Cntr=0.3,0.1

Type RM Length L Ch R = 1 ,19079   ,520,520,520
BEGIN DESCRIPTION:
UNT078 IN SUCR 38.0
END DESCRIPTION:
XS GIS Cut Line= 2
      2254787.71     13373896.85       2253734.4      13373021.6
#Sta/Elev= 30
  4437.2  241.35    4572  237.66  4671.2  232.24  4814.1  229.48    4835  230.31
  4849.3  228.85  4892.3   228.6  4898.8  226.56  4913.1  226.24  4927.4   227.3
  4933.9  226.11  4962.6  226.92  4970.3  224.83  4983.4  224.03  4991.2  221.96
  5002.5  221.73  5005.3  221.23  5008.5  221.73  5019.9  223.99  5034.2   224.2
  5048.3  225.99    5055  225.53  5061.5  227.62  5069.3     226  5075.8  226.89
    5098  225.67  5168.3  227.71  5381.8  229.86    5460  232.74  5806.7  239.39
#Mann= 3 ,-1 , 0
  4437.2      .1       0  5002.5     .07       0  5008.5      .1       0
Bank Sta=5002.5,5008.5
XS Rating Curve= 0 ,0
Exp/Cntr=0.3,0.1

Type RM Length L Ch R = 1 ,18559   ,465,465,465
BEGIN DESCRIPTION:
UNT078 IN SUCR 37.0
END DESCRIPTION:
XS GIS Cut Line= 3
      2255037.75     13373546.88      2254637.72     13373146.85
      2253887.75     13372946.86
#Sta/Elev= 30
  4431.1  236.55  4629.1  232.27  4657.4  231.26  4671.6   229.9  4926.1  223.72
  4940.3  221.49  4954.4  221.07  4968.5  221.82  4982.7  224.17  4990.3   218.7
    4993   218.2  4996.3   218.7  4999.4   218.7  5007.2  221.92  5014.3  222.25
  5019.5  221.14  5048.6  222.61  5054.4  222.96  5059.6  224.93  5129.4  223.54
  5134.6  224.28  5338.4  226.61  5364.9  228.01  5379.7  227.79  5452.2  229.42
  5493.6   230.9  5545.3  231.71  5576.4  233.18  5617.8   233.3    5773  237.29
#Mann= 3 ,-1 , 0
  4431.1      .1       0  4990.3     .07       0  4996.3      .1       0
Bank Sta=4990.3,4996.3
XS Rating Curve= 0 ,0
Exp/Cntr=0.3,0.1

Type RM Length L Ch R = 1 ,18094   ,455,455,455
BEGIN DESCRIPTION:
UNT078 IN SUCR 36.0
END DESCRIPTION:
XS GIS Cut Line= 3
      2255737.74     13373646.87      2254937.72     13372846.85
      2254487.71     13372046.83
#Sta/Elev= 30
  3830.1  257.41  3862.9  253.66  3900.8  248.49  3943.3   246.1  3985.7  245.23
  4282.7  235.12  4438.2  231.59  4537.2  228.15  4593.8   227.8  4876.6  222.51
  4969.5  222.27  4993.9  216.67  4996.6  216.17  4999.9  216.67  5007.1  217.58
  5018.9  220.57  5028.7  221.42    5168  222.59  5190.6  221.45  5225.4  222.72
  5248.3  222.16  5454.9  226.26  5592.5  229.93  5615.5  229.77  5644.5  231.05
  5650.2  230.64  5703.8  232.44  5747.1  232.79  5768.8     234  5879.4   236.2
#Mann= 4 ,-1 , 0
  3830.1     .05       0  3862.9      .1       0  4993.9     .07       0
  4999.9      .1       0
Bank Sta=4993.9,4999.9
XS Rating Curve= 0 ,0
Exp/Cntr=0.3,0.1

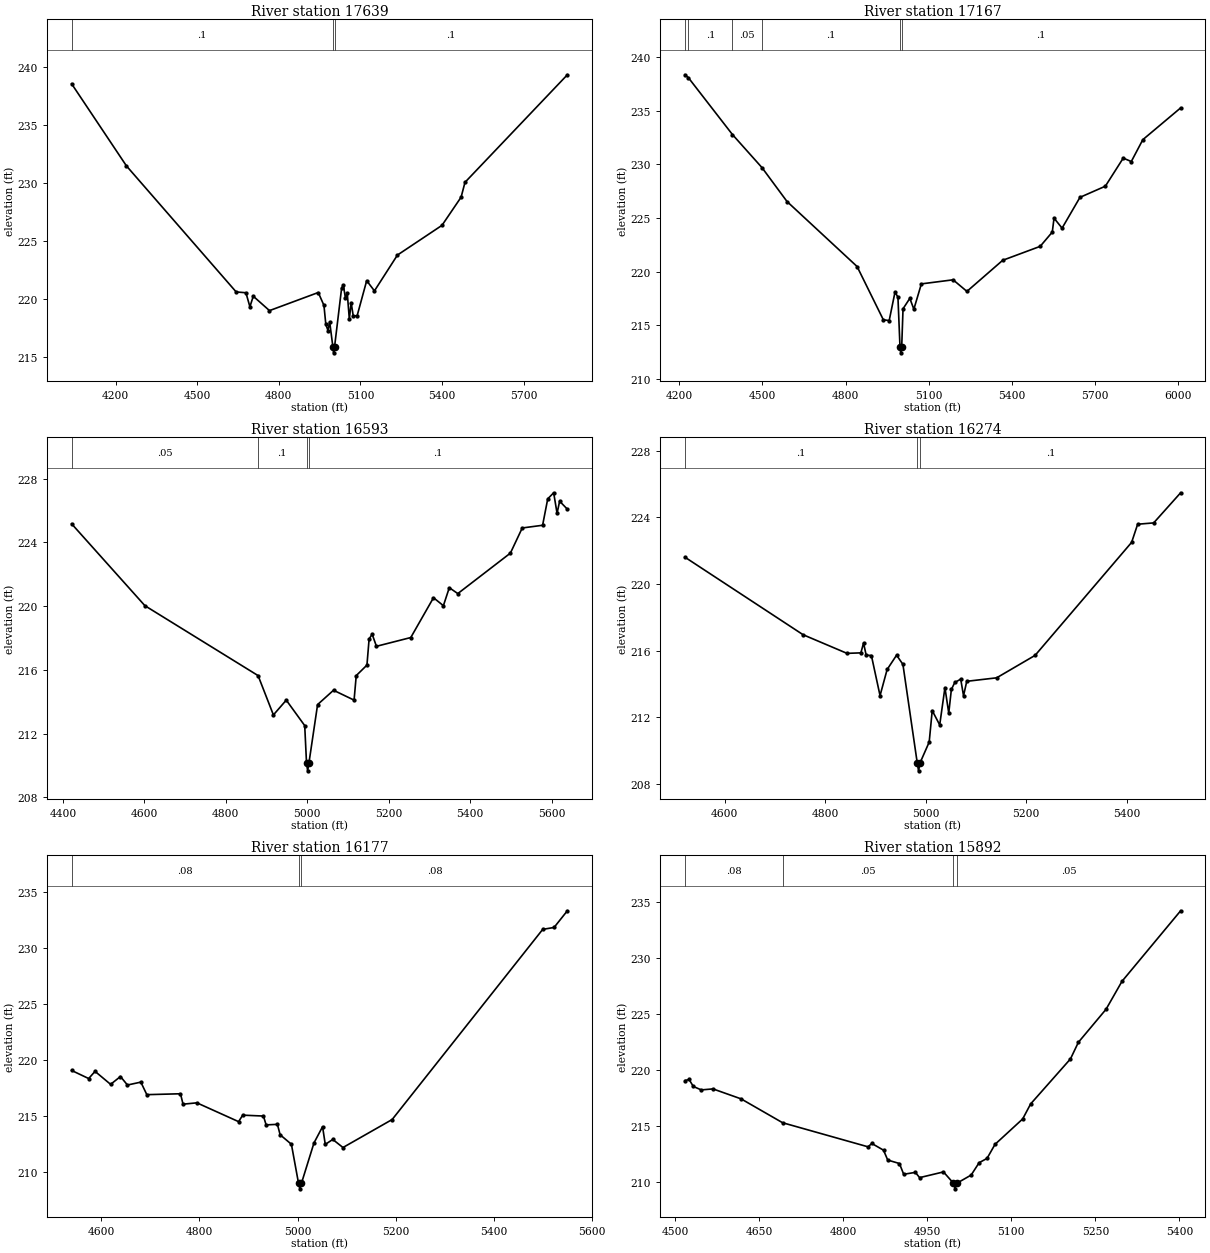
Type RM Length L Ch R = 1 ,17639   ,472,472,472
BEGIN DESCRIPTION:
UNT078 IN SUCR 35.0
END DESCRIPTION:
XS GIS Cut Line= 3
      2255687.72     13373246.86      2255137.72     13372446.85
      2254487.72     13371896.86
#Sta/Elev= 30
  4038.3  238.56  4239.9  231.48  4643.1  220.62    4679  220.55  4693.6  219.34
    4706  220.25  4765.6  219.01  4944.9  220.57  4965.8  219.46  4972.7  217.82
  4980.7  217.29  4986.8  218.05  4998.7  215.87  5001.4  215.37  5004.7  215.87
  5030.6  220.92  5037.1  221.21  5044.9  220.07  5051.4  220.55  5059.1  218.28
  5065.7   219.7  5073.4  218.57  5087.7  218.56  5122.9  221.59  5151.4  220.71
    5236   223.8  5399.7  226.36    5470  228.79  5484.3  230.07  5860.6  239.34
#Mann= 3 ,-1 , 0
  4038.3      .1       0  4998.7     .07       0  5004.7      .1       0
Bank Sta=4998.7,5004.7
XS Rating Curve= 0 ,0
Exp/Cntr=0.3,0.1

Type RM Length L Ch R = 1 ,17167   ,574,574,574
BEGIN DESCRIPTION:
UNT078 IN SUCR 34.0
END DESCRIPTION:
XS GIS Cut Line= 3
      2255787.72     13373196.86      2255537.72     13372446.85
       2254737.7     13371846.84
#Sta/Elev= 30
  4219.9  238.35  4232.4  238.08  4391.5  232.78  4498.4  229.69  4588.8  226.53
  4841.8  220.47  4936.7   215.5  4957.8  215.43  4978.8  218.09  4989.4  217.61
  4996.9  212.92  4999.7  212.42  5002.9  212.92  5007.8  216.53  5032.3   217.5
  5046.9  216.49    5074  218.85  5188.6  219.23  5238.6  218.15  5367.8  221.05
  5503.2  222.35  5546.9  223.68  5553.2  224.98  5582.3  224.05  5646.9  226.92
  5738.6  227.96  5803.2  230.58  5832.3  230.26    5874   232.3  6010.5  235.26
#Mann= 6 ,-1 , 0
  4219.9     .05       0  4232.4      .1       0  4391.5     .05       0
  4498.4      .1       0  4996.9     .07       0  5002.9      .1       0
Bank Sta=4996.9,5002.9
XS Rating Curve= 0 ,0
Exp/Cntr=0.3,0.1

Type RM Length L Ch R = 1 ,16593   ,319,319,319
BEGIN DESCRIPTION:
Mapping XS 585cdd78
END DESCRIPTION:
XS GIS Cut Line= 4
      2256110.12     13372479.37      2255978.98     13372035.89
      2255556.97     13371895.22      2255309.05     13371709.28
#Sta/Elev= 30
  4421.4  225.17  4601.3  220.03  4879.2  215.64  4916.8  213.17  4948.4   214.1
  4993.7   212.5  4998.1  210.16  5000.9  209.66  5004.1  210.16  5025.3  213.82
  5064.4  214.72  5114.9   214.1  5120.2  215.64  5146.5   216.3  5151.8  217.94
  5159.3  218.24  5169.8  217.48  5254.1  218.03  5309.9  220.53  5334.2  220.03
  5348.7  221.16  5369.6  220.79  5498.7  223.33  5527.8  224.91  5577.8  225.08
  5590.4  226.74    5605  227.12  5613.3  225.83  5619.6  226.59  5638.6  226.09
#Mann= 4 ,-1 , 0
  4421.4     .05       0  4879.2      .1       0  4998.1     .07       0
  5004.1      .1       0
Bank Sta=4998.1,5004.1
XS Rating Curve= 0 ,0
Exp/Cntr=0.3,0.1

Type RM Length L Ch R = 1 ,16274   ,97,97,97
BEGIN DESCRIPTION:
UNT078 IN SUCR 33.0
END DESCRIPTION:
XS GIS Cut Line= 3
      2256572.65     13371945.29      2256055.28     13371787.93
      2255662.26     13371578.32
#Sta/Elev= 30
  4521.2  221.61  4756.3  216.95  4843.7  215.83  4871.3  215.86  4876.6  216.45
  4881.8  215.72  4892.2   215.7  4909.4  213.29  4923.5  214.86  4942.3  215.72
  4954.9  215.17  4983.3  209.27    4986  208.77  4989.3  209.27  5007.2   210.5
  5013.2  212.39  5028.1  211.53  5038.5  213.77  5046.1  212.24  5051.3  213.66
  5058.1  214.08  5069.9  214.28  5075.5  213.28  5081.9  214.15  5141.4  214.36
  5217.9  215.71  5409.9   222.5  5421.9  223.59  5453.8  223.67  5507.4  225.48
#Mann= 3 ,-1 , 0
  4521.2      .1       0  4983.3     .07       0  4989.3      .1       0
Bank Sta=4983.3,4989.3
XS Rating Curve= 0 ,0
Exp/Cntr=0.3,0.1

Type RM Length L Ch R = 1 ,16177   ,285,285,285
BEGIN DESCRIPTION:
UNT078 IN SUCR 32.0
END DESCRIPTION:
XS GIS Cut Line= 4
      2256603.64     13371861.84      2256250.78     13371764.08
      2256110.11     13371699.71      2255716.72     13371408.84
#Sta/Elev= 30
  4539.7  219.06  4574.4  218.34  4587.4  218.98  4619.1  217.82  4639.2  218.52
  4653.4  217.76  4680.7  218.02  4692.9   216.9  4761.5  216.98  4766.7  216.05
  4794.9  216.17  4879.9  214.49  4888.3  215.07  4930.5  214.99    4936   214.2
    4959  214.25  4964.5  213.32  4987.5  212.47    5002  208.99  5004.8  208.49
    5008  208.99  5033.5  212.59    5051  214.04  5056.5  212.46  5071.8   212.9
  5092.6  212.18  5192.8  214.68  5499.6  231.66  5522.7  231.83  5549.8  233.32
#Mann= 3 ,-1 , 0
  4539.7     .08       0    5002     .07       0    5008     .08       0
Bank Sta=5002,5008
XS Rating Curve= 0 ,0
Exp/Cntr=0.3,0.1

Type RM Length L Ch R = 1 ,15892   ,427,427,427
BEGIN DESCRIPTION:
UNT078 IN SUCR 31.0
END DESCRIPTION:
XS GIS Cut Line= 2
      2256653.73     13371861.85      2256066.05     13371200.42
#Sta/Elev= 30
  4517.4  219.07  4524.9  219.17  4532.4  218.55  4546.6  218.24  4567.5  218.33
  4617.7  217.44  4691.8  215.31  4844.3  213.16    4851  213.46  4871.9  212.86
  4879.4  211.98  4900.3  211.67  4907.9  210.71  4928.8  210.88  4936.3  210.41
  4978.9  210.92  4996.8  209.91  4999.6  209.41  5002.8  209.91  5028.3  210.64
  5042.5  211.74  5056.7  212.13  5070.9  213.38  5120.3  215.65  5134.5  216.99
  5205.6  221.01  5219.7  222.49  5269.1  225.44  5297.5  227.93  5402.2  234.23
#Mann= 4 ,-1 , 0
  4517.4     .08       0  4691.8     .05       0  4996.8     .03       0
  5002.8     .05       0
Bank Sta=4996.8,5002.8
XS Rating Curve= 0 ,0
Exp/Cntr=0.3,0.1

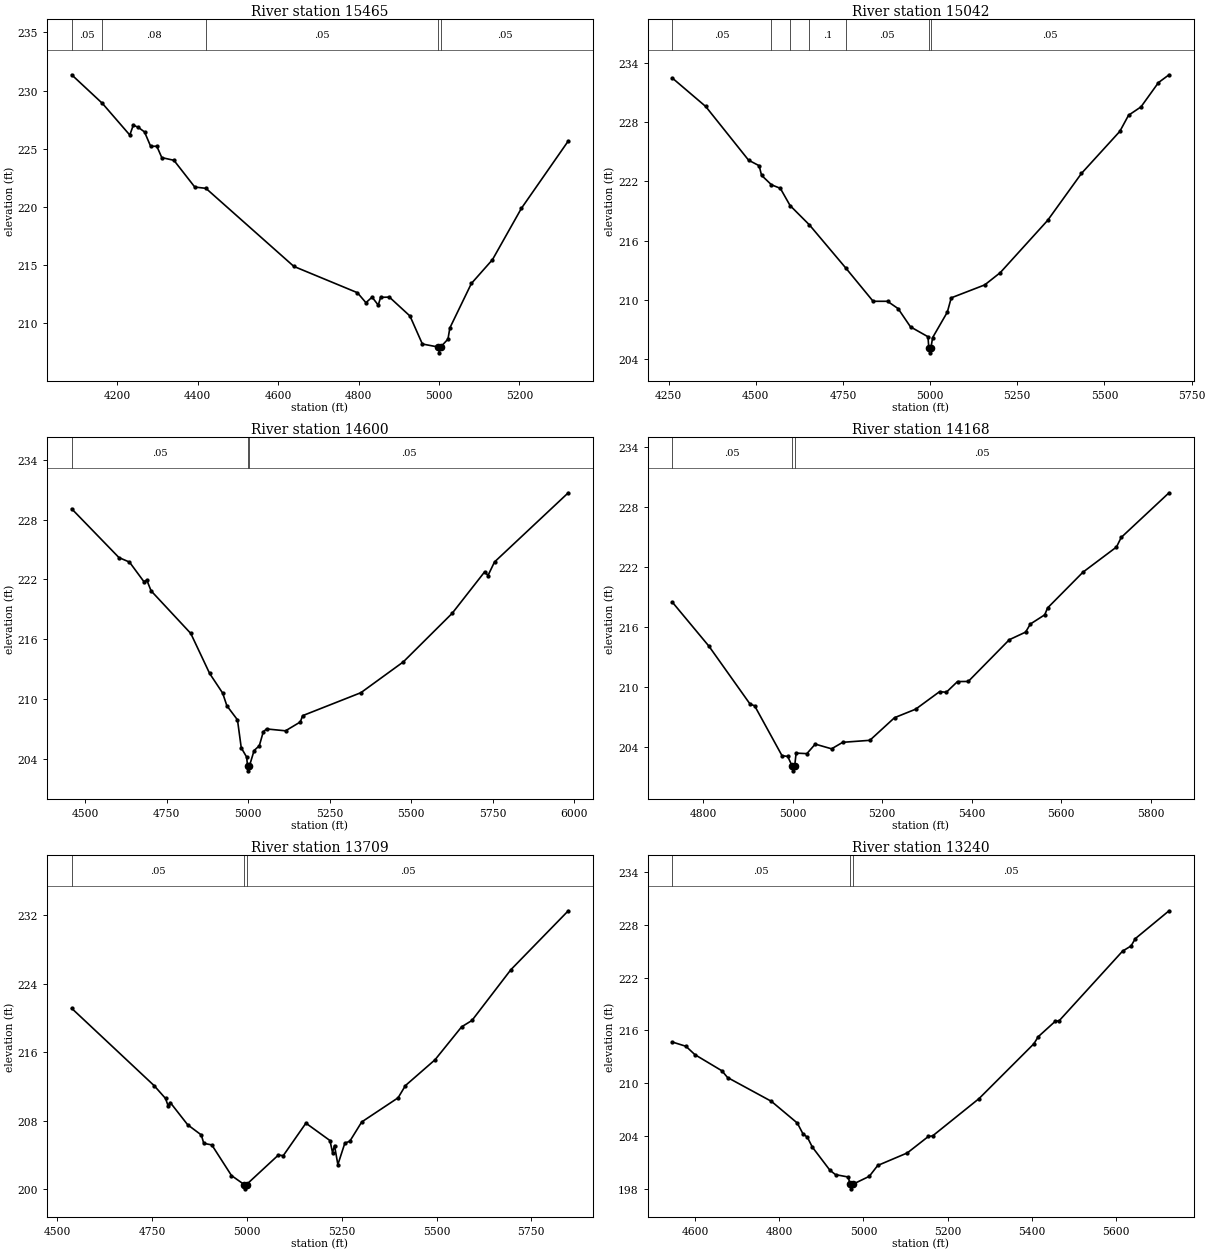
Type RM Length L Ch R = 1 ,15465   ,423,423,423
BEGIN DESCRIPTION:
UNT078 IN SUCR 30.0
END DESCRIPTION:
XS GIS Cut Line= 3
      2257187.74     13372096.89      2256687.72     13371296.85
      2256437.71     13371146.85
#Sta/Elev= 30
  4086.6  231.36    4163   228.9  4231.1  226.18  4239.9  227.03  4252.3  226.84
  4267.7  226.45    4283  225.21  4298.3  225.22  4310.7  224.24  4340.8  224.01
  4392.7  221.71  4420.4   221.6  4639.1  214.89  4797.1  212.63  4818.4  211.77
  4833.7  212.25    4849  211.56  4854.9  212.23  4876.7  212.25    4928  210.62
  4958.7  208.22  4998.1  207.96  5000.9  207.46  5004.1  207.96  5022.4  208.64
  5027.1   209.6  5080.6  213.42  5133.1  215.47    5205  219.88  5321.6  225.67
#Mann= 5 ,-1 , 0
  4086.6     .05       0    4163     .08       0  4420.4     .05       0
  4998.1     .03       0  5004.1     .05       0
Bank Sta=4998.1,5004.1
XS Rating Curve= 0 ,0
Exp/Cntr=0.3,0.1

Type RM Length L Ch R = 1 ,15042   ,442,442,442
BEGIN DESCRIPTION:
UNT078 IN SUCR 29.0
END DESCRIPTION:
XS GIS Cut Line= 2
      2257727.18       13371368.      2256392.34     13370872.02
#Sta/Elev= 30
  4261.1  232.45  4356.5  229.58  4479.5  224.14  4509.8  223.58  4516.6  222.61
    4545  221.65  4570.5  221.29  4598.4  219.55  4654.1  217.58  4757.7  213.24
  4836.6  209.85  4877.8  209.85  4908.2  209.11  4943.8  207.26  4993.9  206.26
  4996.2  205.13    4999  204.63  5002.2  205.13  5007.3  206.18  5049.3  208.75
  5060.6   210.2  5156.6  211.51  5201.1  212.75  5336.9  218.04    5434   222.8
    5544  227.06    5569  228.69  5604.7  229.54  5654.8     232  5685.1  232.79
#Mann= 7 ,-1 , 0
  4261.1     .05       0    4545      .1       0  4598.4     .05       0
  4654.1      .1       0  4757.7     .05       0  4996.2     .03       0
  5002.2     .05       0
Bank Sta=4996.2,5002.2
XS Rating Curve= 0 ,0
Exp/Cntr=0.3,0.1

Type RM Length L Ch R = 1 ,14600   ,432,432,432
BEGIN DESCRIPTION:
UNT078 IN SUCR 28.0
END DESCRIPTION:
XS GIS Cut Line= 3
      2257827.85     13371042.19      2257103.92     13370698.45
      2256381.39     13370688.06
#Sta/Elev= 30
  4458.1   229.1  4603.2   224.2  4635.4  223.75  4679.6  221.79  4688.6  221.94
  4701.8  220.86  4823.6  216.58  4881.5  212.56  4921.4  210.59  4934.3  209.32
  4966.9   207.9  4978.5  205.09  4995.1  204.16  4997.7  203.28  5000.4  202.78
  5003.7  203.28  5017.9  204.82  5033.9   205.3  5046.1   206.7    5056  206.99
  5114.3   206.8  5159.8  207.69  5166.7  208.32  5345.7  210.63  5475.7  213.72
  5625.7   218.6  5725.7  222.78  5735.7   222.4  5755.7  223.76  5982.1  230.71
#Mann= 3 ,-1 , 0
  4458.1     .05       0  4997.7    .035       0  5003.7     .05       0
Bank Sta=4997.7,5003.7
XS Rating Curve= 0 ,0
Exp/Cntr=0.3,0.1

Type RM Length L Ch R = 1 ,14168   ,459,459,459
BEGIN DESCRIPTION:
UNT078 IN SUCR 27.0
END DESCRIPTION:
XS GIS Cut Line= 3
      2257637.72     13370446.85      2257387.72     13370396.85
      2256587.76     13370096.87
#Sta/Elev= 30
  4731.8  218.44  4813.4  214.05  4905.2  208.27  4915.4   208.1  4976.5  203.12
  4989.4  203.04  4998.9   202.1  5001.6   201.6  5004.9   202.1  5008.1  203.37
  5032.1  203.32  5050.8  204.27  5087.3   203.8  5112.2  204.45  5172.8  204.65
  5227.9  206.91  5275.1  207.76  5328.5  209.51  5343.6  209.45  5368.6  210.52
  5392.6  210.53  5484.3   214.7  5520.7  215.46  5531.4  216.27  5563.5  217.19
  5569.7  217.87  5648.9  221.45  5723.7  223.96  5734.3  224.92  5841.1  229.38
#Mann= 3 ,-1 , 0
  4731.8     .05       0  4998.9    .035       0  5004.9     .05       0
Bank Sta=4998.9,5004.9
XS Rating Curve= 0 ,0
Exp/Cntr=0.3,0.1

Type RM Length L Ch R = 1 ,13709   ,469,469,469
BEGIN DESCRIPTION:
UNT078 IN SUCR 26.0
END DESCRIPTION:
XS GIS Cut Line= 3
      2257787.68     13370196.83      2257387.72     13369946.85
      2256587.73     13369696.86
#Sta/Elev= 30
  4537.7  221.12  4755.2  212.09  4785.3  210.59  4791.8  209.76  4797.7  210.12
  4843.7  207.52  4879.6  206.33  4886.1  205.35  4907.3  205.17  4959.2  201.59
  4992.8  200.54  4995.5  200.04  4998.8  200.54  5082.7  203.98  5095.8  203.92
  5155.5  207.71  5218.9  205.68  5225.7  204.28  5230.9   205.1  5239.8  202.87
  5258.2  205.38  5271.3   205.6  5302.7  207.85  5398.6  210.67    5418   212.1
    5496  215.11  5566.2  218.96  5593.4   219.7  5696.1  225.63  5847.5  232.51
#Mann= 3 ,-1 , 0
  4537.7     .05       0  4992.8     .03       0  4998.8     .05       0
Bank Sta=4992.8,4998.8
XS Rating Curve= 0 ,0
Exp/Cntr=0.3,0.1

Type RM Length L Ch R = 1 ,13240   ,332,332,332
BEGIN DESCRIPTION:
UNT078 IN SUCR 25.0
END DESCRIPTION:
XS GIS Cut Line= 3
       2257837.7     13369646.85      2257437.72     13369496.85
      2256687.77     13369446.86
#Sta/Elev= 30
  4546.6  214.69  4578.6  214.21    4600  213.26  4664.1  211.43  4677.4  210.67
  4781.5  207.97    4843  205.51  4856.3   204.3    4867  203.89  4878.6  202.79
  4920.4  200.16  4933.7  199.66    4964  199.39  4968.1  198.55  4970.9  198.05
  4974.1  198.55  5013.9  199.47  5033.9   200.7  5104.1  202.12  5154.2  203.99
  5164.2  204.05  5274.4  208.28  5404.7   214.5  5414.8  215.29  5454.8  217.02
  5464.9  217.12  5615.2     225  5635.2  225.58  5645.3  226.41  5725.4  229.57
#Mann= 3 ,-1 , 0
  4546.6     .05       0  4968.1     .03       0  4974.1     .05       0
Bank Sta=4968.1,4974.1
XS Rating Curve= 0 ,0
Exp/Cntr=0.3,0.1

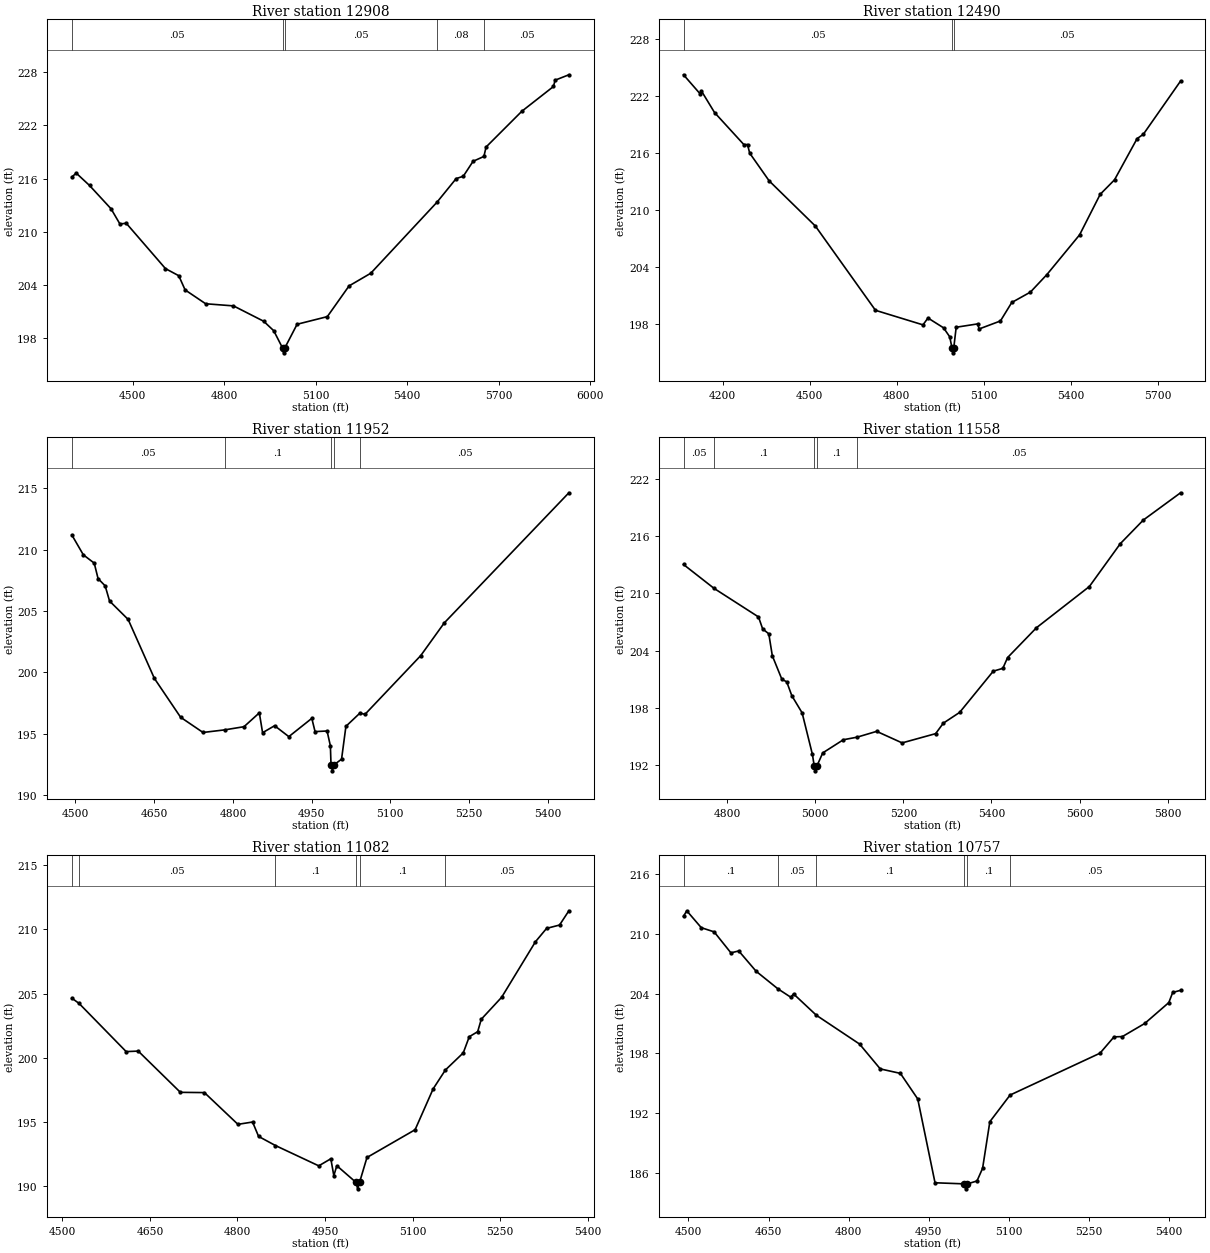
Type RM Length L Ch R = 1 ,12908   ,418,418,418
BEGIN DESCRIPTION:
UNT078 IN SUCR 24.0
END DESCRIPTION:
XS GIS Cut Line= 4
      2258020.69     13369614.38      2257751.61     13369267.17
      2257117.93      13369076.2      2256623.14     13369258.49
#Sta/Elev= 30
  4301.1  216.19  4315.5  216.63    4359  215.24  4429.6  212.61  4458.6   210.9
  4479.4  210.98  4607.9  205.87  4651.4  205.07  4672.2  203.47  4739.5  201.91
  4830.7  201.67  4929.6  199.94  4962.6  198.87  4992.1  196.88  4994.8  196.38
  4998.1  196.88  5039.1   199.6  5138.1  200.46  5209.3  203.92  5280.5  205.35
  5497.1  213.34  5560.1  216.01  5583.6  216.28  5615.6  217.96  5651.1  218.51
  5658.2  219.57  5775.4   223.6    5879  226.39  5884.3   227.1  5929.5  227.71
#Mann= 5 ,-1 , 0
  4301.1     .05       0  4992.1     .03       0  4998.1     .05       0
  5497.1     .08       0  5651.1     .05       0
Bank Sta=4992.1,4998.1
XS Rating Curve= 0 ,0
Exp/Cntr=0.3,0.1

Type RM Length L Ch R = 1 ,12490   ,538,538,538
BEGIN DESCRIPTION:
UNT078 IN SUCR 23.0
END DESCRIPTION:
XS GIS Cut Line= 4
      2258723.87     13369119.61      2258046.75      13369032.8
      2257664.81     13368885.23      2257248.16     13368425.18
#Sta/Elev= 30
  4065.6  224.21  4121.9  222.24  4126.9  222.53  4172.6  220.24  4273.4  216.88
  4286.2  216.88  4293.6  215.98  4360.8  213.06  4520.1  208.31  4727.1  199.46
  4890.8  197.93    4908  198.65  4961.6  197.62  4983.1  196.67  4990.8  195.49
  4993.5  194.99  4996.8  195.49  5005.2  197.68    5079  198.03  5084.4   197.5
  5157.7  198.34  5196.7  200.28  5260.9  201.37  5317.4   203.2  5430.5  207.39
  5501.5  211.65  5550.8  213.17  5628.6   217.5  5650.2  217.96  5778.4  223.55
#Mann= 3 ,-1 , 0
  4065.6     .05       0  4990.8    .035       0  4996.8     .05       0
Bank Sta=4990.8,4996.8
XS Rating Curve= 0 ,0
Exp/Cntr=0.3,0.1

Type RM Length L Ch R = 1 ,11952   ,394,394,394
BEGIN DESCRIPTION:
UNT078 IN SUCR 22.0
END DESCRIPTION:
XS GIS Cut Line= 3
       2258387.7     13368846.84      2257987.72     13368546.85
      2257587.71     13368346.85
#Sta/Elev= 30
  4493.1  211.21    4515  209.59  4535.8  208.91  4543.1  207.65  4556.6  207.06
    4565  205.82  4600.4  204.32  4650.4  199.51  4700.4  196.34  4743.1   195.1
  4784.1  195.31  4821.2  195.57  4850.4   196.7  4856.6  195.08  4879.5  195.65
  4906.6  194.76  4950.4  196.25  4956.6  195.17  4979.5  195.22  4985.8  194.01
    4987  192.47  4989.7  191.97    4993  192.47  5007.1  192.92  5015.4   195.6
  5042.1  196.68  5051.8  196.58    5158  201.37  5202.7  204.03  5440.3  214.65
#Mann= 5 ,-1 , 0
  4493.1     .05       0  4784.1      .1       0    4987     .07       0
    4993      .1       0  5042.1     .05       0
Bank Sta=4987,4993
XS Rating Curve= 0 ,0
Exp/Cntr=0.3,0.1

Type RM Length L Ch R = 1 ,11558   ,476,476,476
BEGIN DESCRIPTION:
UNT078 IN SUCR 21.0
END DESCRIPTION:
XS GIS Cut Line= 2
      2258552.56     13368568.28      2257517.83     13368116.89
#Sta/Elev= 30
  4700.6  213.03  4770.1  210.52  4870.9  207.53  4880.4  206.27  4894.3  205.76
  4902.3  203.46  4924.1  200.98    4935  200.73  4946.6  199.27    4970  197.47
  4993.4  193.11  4997.5  191.89  5000.2  191.39  5003.5  191.89  5016.8  193.27
  5063.6  194.65  5094.8  194.92  5139.3  195.53  5197.1  194.32  5273.2  195.29
  5290.7  196.39  5327.8  197.52  5404.1  201.84  5425.9  202.14  5436.7  203.27
  5502.3   206.4  5622.4  210.72  5692.6  215.21  5744.9  217.69  5829.5  220.55
#Mann= 5 ,-1 , 0
  4700.6     .05       0  4770.1      .1       0  4997.5     .07       0
  5003.5      .1       0  5094.8     .05       0
Bank Sta=4997.5,5003.5
XS Rating Curve= 0 ,0
Exp/Cntr=0.3,0.1

Type RM Length L Ch R = 1 ,11082   ,325,325,325
BEGIN DESCRIPTION:
UNT078 IN SUCR 20.0
END DESCRIPTION:
XS GIS Cut Line= 2
      2258608.03     13368151.59      2257782.17     13367943.39
#Sta/Elev= 30
  4516.2  204.65  4528.6  204.24  4609.3  200.49    4630  200.53  4702.2  197.32
  4743.4   197.3  4800.8  194.83  4825.9  195.01  4836.2  193.89  4865.1  193.18
  4939.3   191.6    4960  192.15  4965.1  190.84  4970.3  191.61  5003.2  190.31
  5005.9  189.81  5009.2  190.31  5021.9  192.25  5104.4  194.41  5135.3  197.59
  5156.3  199.06  5186.9  200.39  5197.2  201.65  5211.6  202.04  5217.8  203.01
  5252.7  204.72  5310.6  209.04  5329.7  210.08  5351.9  210.34  5367.9  211.45
#Mann= 6 ,-1 , 0
  4516.2      .1       0  4528.6     .05       0  4865.1      .1       0
  5003.2     .07       0  5009.2      .1       0  5156.3     .05       0
Bank Sta=5003.2,5009.2
XS Rating Curve= 0 ,0
Exp/Cntr=0.3,0.1

Type RM Length L Ch R = 1 ,10757   ,261,261,261
BEGIN DESCRIPTION:
UNT078 IN SUCR 19.0
END DESCRIPTION:
XS GIS Cut Line= 2
      2258802.48     13367922.42      2257913.67     13367644.67
#Sta/Elev= 30
  4490.7  211.79  4496.8  212.34    4524  210.64  4548.1  210.22  4579.5  208.11
  4594.2   208.3  4626.7  206.26  4667.6  204.49  4691.6  203.65  4696.9  203.98
  4739.7  201.83  4820.5  198.94  4859.3  196.44    4897  195.99  4929.5  193.42
  4961.9  184.99  5016.5  184.88  5019.3  184.38  5022.5  184.88  5040.5  185.17
    5051  186.44  5064.6  191.13  5102.5  193.81    5271  198.02  5297.2  199.66
  5312.9  199.69  5354.8  201.01  5399.9  203.11  5407.2  204.13  5421.9  204.34
#Mann= 6 ,-1 , 0
  4490.7      .1       0  4667.6     .05       0  4739.7      .1       0
  5016.5     .07       0  5022.5      .1       0  5102.5     .05       0
Bank Sta=5016.5,5022.5
XS Rating Curve= 0 ,0
Exp/Cntr=0.3,0.1

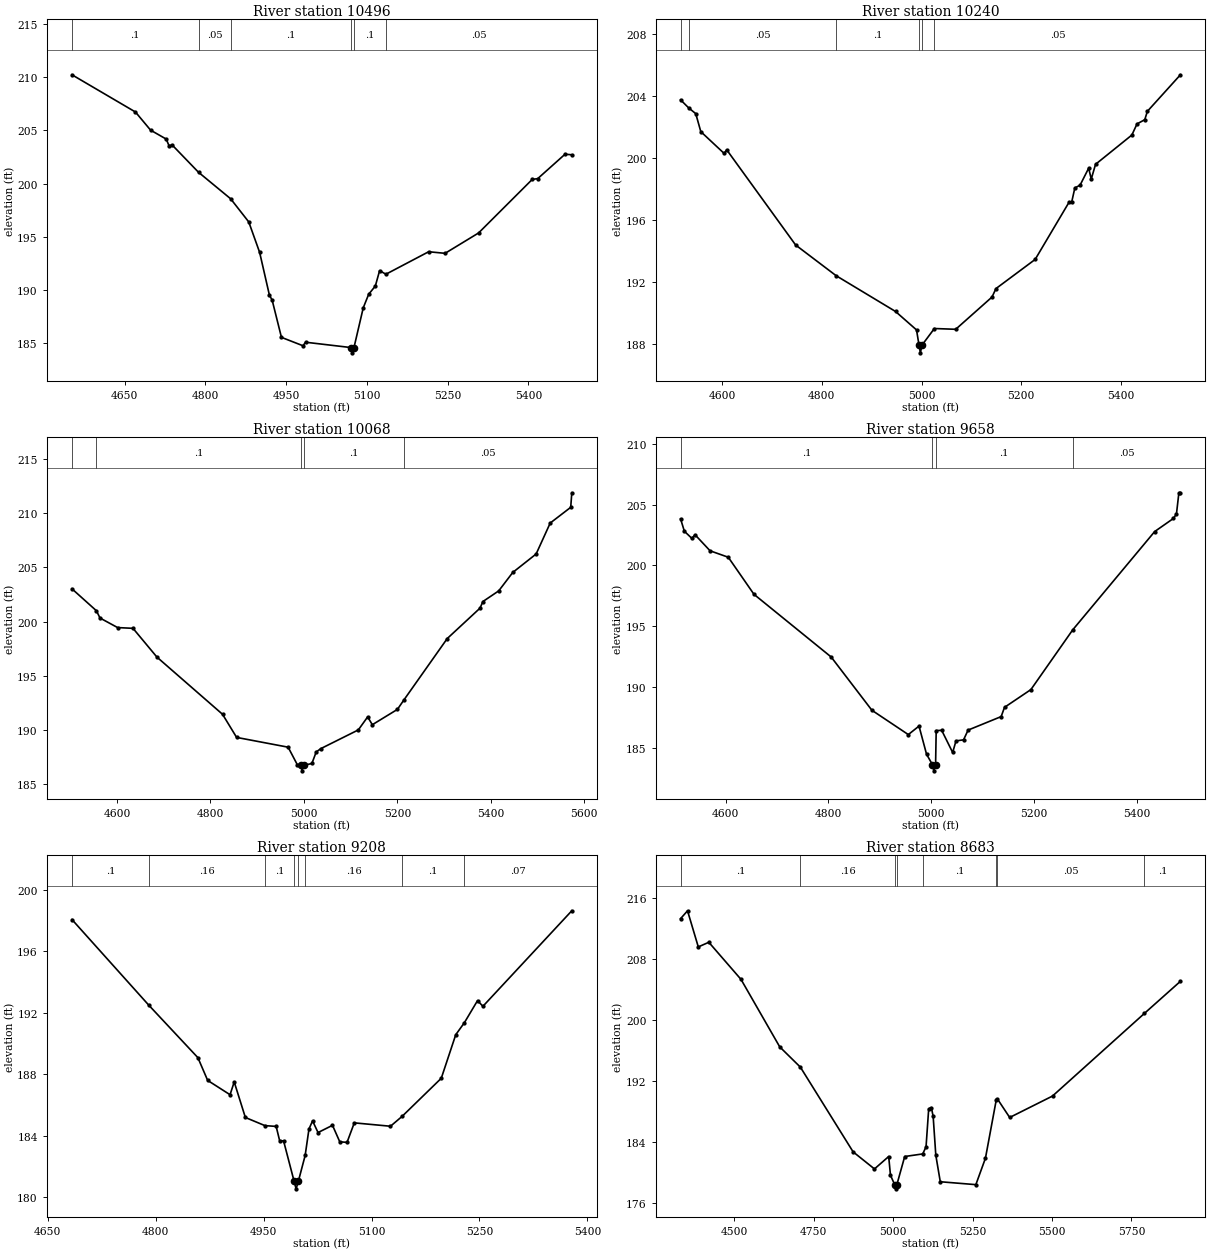
Type RM Length L Ch R = 1 ,10496   ,256,256,256
BEGIN DESCRIPTION:
Mapping XS acc7e754
END DESCRIPTION:
XS GIS Cut Line= 2
      2258871.93     13367609.93      2257955.25     13367464.09
#Sta/Elev= 30
  4552.3  210.25  4670.2  206.74  4698.3  205.03  4727.3  204.19  4732.4  203.58
  4738.8  203.61  4787.3  201.06    4847  198.56  4880.6  196.38  4900.8  193.51
    4919  189.47    4924  189.02  4941.3   185.5  4981.2  184.71  4986.2  185.04
    5070  184.54  5072.7  184.04    5076  184.54  5093.2  188.28  5103.3  189.56
  5115.7  190.34  5123.6  191.79  5135.3  191.45  5214.7  193.57  5245.2  193.42
  5307.4  195.34  5407.1  200.39  5417.2  200.46  5467.9  202.76  5480.5  202.71
#Mann= 6 ,-1 , 0
  4552.3      .1       0  4787.3     .05       0    4847      .1       0
    5070     .07       0    5076      .1       0  5135.3     .05       0
Bank Sta=5070,5076
XS Rating Curve= 0 ,0
Exp/Cntr=0.3,0.1

Type RM Length L Ch R = 1 ,10240   ,172,172,172
BEGIN DESCRIPTION:
Mapping XS 6521d3f4
END DESCRIPTION:
XS GIS Cut Line= 3
      2258868.12     13367267.17      2258330.96     13367295.41
      2257883.94     13367421.25
#Sta/Elev= 30
  4516.8  203.75  4533.1  203.23  4547.2  202.86  4557.3   201.7  4604.2  200.29
  4609.2  200.53  4747.5  194.38  4828.7   192.4  4947.8  190.09  4989.9   188.9
  4994.9  187.92  4997.6  187.42  5000.9  187.92  5025.7  188.99  5068.5  188.94
  5141.2  191.02  5149.3  191.57  5227.8  193.45  5295.9  197.15  5301.1  197.16
  5307.4  198.07  5317.8  198.24  5335.1  199.34  5340.3  198.64  5348.9  199.59
  5421.7  201.48  5432.1   202.2  5447.6  202.47  5452.8  203.01  5519.1  205.37
#Mann= 6 ,-1 , 0
  4516.8      .1       0  4533.1     .05       0  4828.7      .1       0
  4994.9     .07       0  5000.9      .1       0  5025.7     .05       0
Bank Sta=4994.9,5000.9
XS Rating Curve= 0 ,0
Exp/Cntr=0.3,0.1

Type RM Length L Ch R = 1 ,10068   ,410,410,410
BEGIN DESCRIPTION:
UNT078 IN SUCR 18.0
END DESCRIPTION:
XS GIS Cut Line= 3
      2258887.24     13367154.76      2258560.04      13367112.2
      2257821.57     13367152.04
#Sta/Elev= 30
  4503.7  203.02    4556     201  4563.7  200.33  4601.4  199.45  4634.3  199.38
  4685.5  196.73  4825.9  191.46    4856  189.33  4966.2  188.43  4986.2  186.79
  4993.2  186.75    4996  186.25  4999.2  186.75  5017.1  186.93  5026.3  187.99
  5036.3   188.3  5116.4  190.02  5136.4  191.22  5146.4   190.5    5200  191.91
  5214.6  192.82  5306.7  198.44  5376.8  201.24    5383  201.85  5416.8  202.83
  5446.9  204.53  5496.9  206.23    5527  209.08  5570.9  210.53  5573.2  211.87
#Mann= 5 ,-1 , 0
  4503.7     .05       0    4556      .1       0  4993.2     .07       0
  4999.2      .1       0  5214.6     .05       0
Bank Sta=4993.2,4999.2
XS Rating Curve= 0 ,0
Exp/Cntr=0.3,0.1

Type RM Length L Ch R = 1 ,9658    ,450,450,450
BEGIN DESCRIPTION:
UNT078 IN SUCR 17.0
END DESCRIPTION:
XS GIS Cut Line= 3
      2258937.71     13367046.85      2258537.72     13366746.85
      2258137.71     13366496.85
#Sta/Elev= 30
  4512.7  203.82    4520  202.81  4534.6  202.22  4540.8  202.52    4570   201.2
  4605.4  200.67  4655.4  197.62  4805.4  192.47  4884.6  188.09  4955.4  186.09
  4976.2  186.79  4990.8  184.48  5002.4  183.61  5005.1  183.11  5008.4  183.61
  5009.6  186.42  5020.3  186.44  5041.6  184.62  5048.1  185.57  5062.8  185.66
  5071.6  186.46  5135.9  187.57  5142.4  188.33  5193.7  189.79    5275   194.7
  5434.3  202.78  5470.8  203.86  5476.7  204.23  5481.4  205.97  5484.4  205.97
#Mann= 4 ,-1 , 0
  4512.7      .1       0  5002.4     .07       0  5008.4      .1       0
    5275     .05       0
Bank Sta=5002.4,5008.4
XS Rating Curve= 0 ,0
Exp/Cntr=0.3,0.1

Type RM Length L Ch R = 1 ,9208    ,525,525,525
BEGIN DESCRIPTION:
UNT078 IN SUCR 16.0
END DESCRIPTION:
XS GIS Cut Line= 3
      2258987.75     13366546.87      2258737.72     13366396.85
      2258337.71     13366346.85
#Sta/Elev= 30
  4683.6  198.05  4790.4  192.48  4858.6  189.07  4872.2  187.59  4903.3  186.66
  4909.1  187.49  4924.6  185.18  4951.8  184.65  4967.4   184.6  4972.3  183.66
  4977.7  183.66  4992.3  181.04  4995.1  180.54  4998.3  181.04  5007.7  182.71
    5013  184.43    5018  184.96  5025.6   184.2  5045.7  184.67  5055.8   183.6
  5065.9  183.56    5076  184.83  5126.3  184.61  5142.4  185.25  5196.9  187.73
    5217  190.56  5229.1  191.35  5247.3  192.78  5254.8  192.41  5378.3  198.62
#Mann= 8 ,-1 , 0
  4683.6      .1       0  4790.4     .16       0  4951.8      .1       0
  4992.3     .07       0  4998.3      .1       0  5007.7     .16       0
  5142.4      .1       0  5229.1     .07       0
Bank Sta=4992.3,4998.3
XS Rating Curve= 0 ,0
Exp/Cntr=0.3,0.1

Type RM Length L Ch R = 1 ,8683    ,405,405,405
BEGIN DESCRIPTION:
UNT078 IN SUCR 15.0
END DESCRIPTION:
XS GIS Cut Line= 3
      2259587.22     13366304.37      2258538.63     13365783.54
      2258198.33     13365568.25
#Sta/Elev= 30
  4330.9   213.3  4352.7  214.33  4386.6  209.59  4419.7   210.2  4521.1  205.33
    4643  196.48    4708  193.82    4874  182.71  4941.2  180.47    4986   182.1
  4991.6  179.64  5005.4  178.36  5008.2  177.86  5011.4  178.36  5036.4   182.1
  5093.2  182.44  5103.6  183.38  5111.9  188.34  5120.4  188.52    5126  187.35
  5134.3  182.28  5148.4  178.79  5260.4  178.41  5290.6  181.88  5324.7  189.54
  5328.1  189.66  5366.9  187.22  5501.7  190.03  5791.3  200.88  5904.4  205.08
#Mann= 8 ,-1 , 0
  4330.9      .1       0    4708     .16       0  5005.4     .07       0
  5011.4     .16       0  5093.2      .1       0  5324.7     .07       0
  5328.1     .05       0  5791.3      .1       0
Bank Sta=5005.4,5011.4
XS Rating Curve= 0 ,0
Exp/Cntr=0.3,0.1