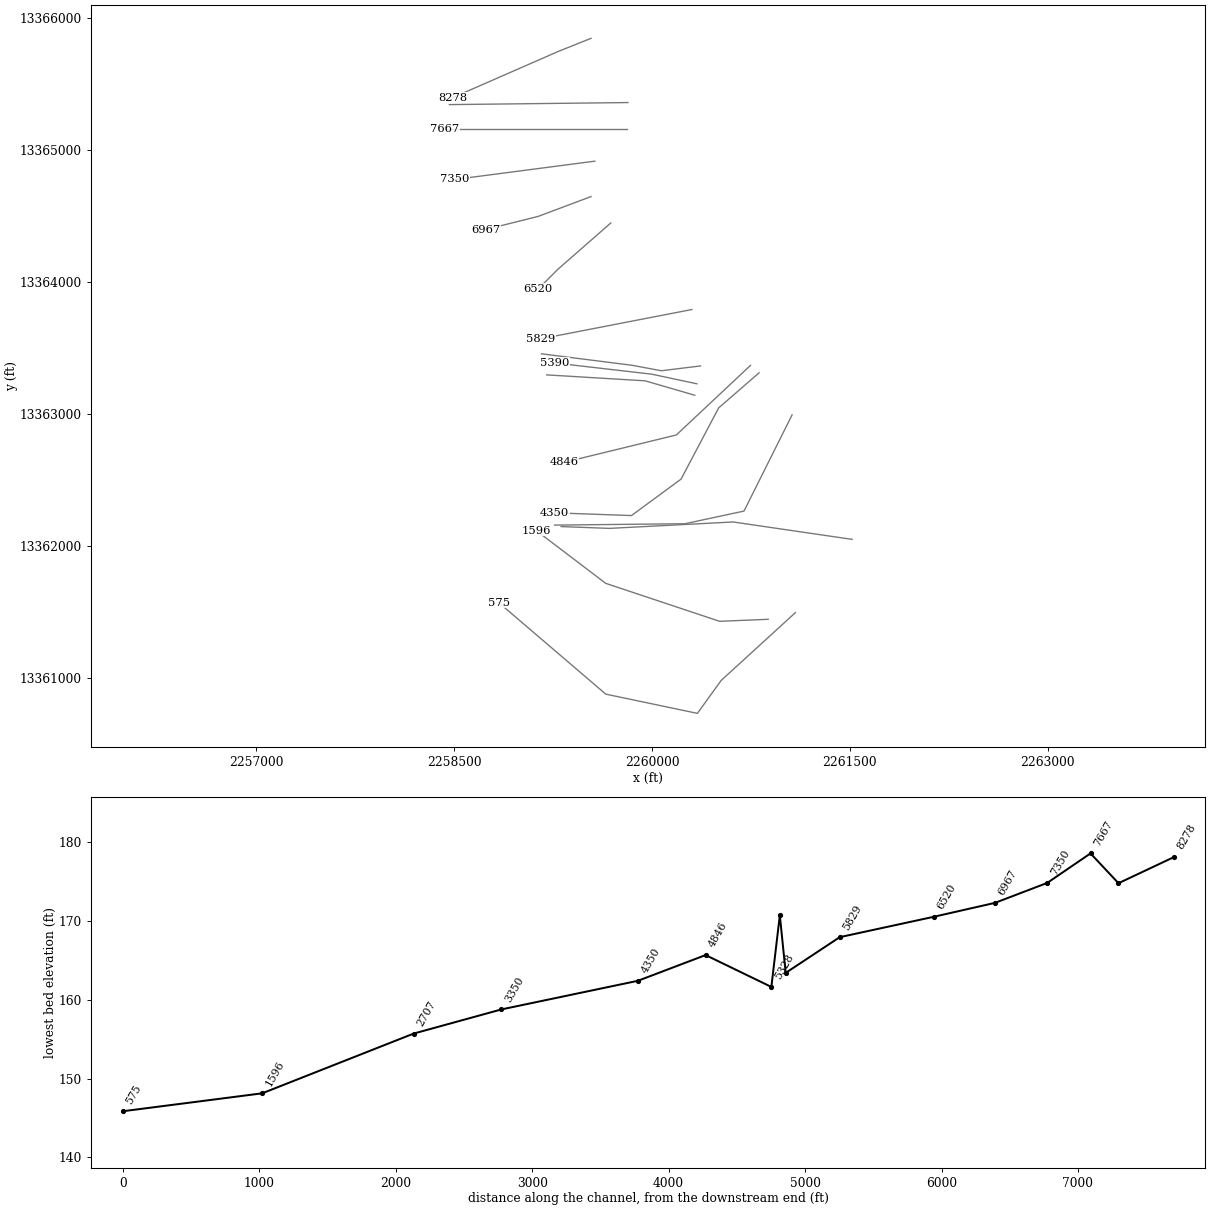
HEC-RAS study UNT078 IN SUCR.prj: UNT078 IN SUCR Base Level Engineering

--- UNT078 IN SUCR.g01 (geometry) --- (continued)

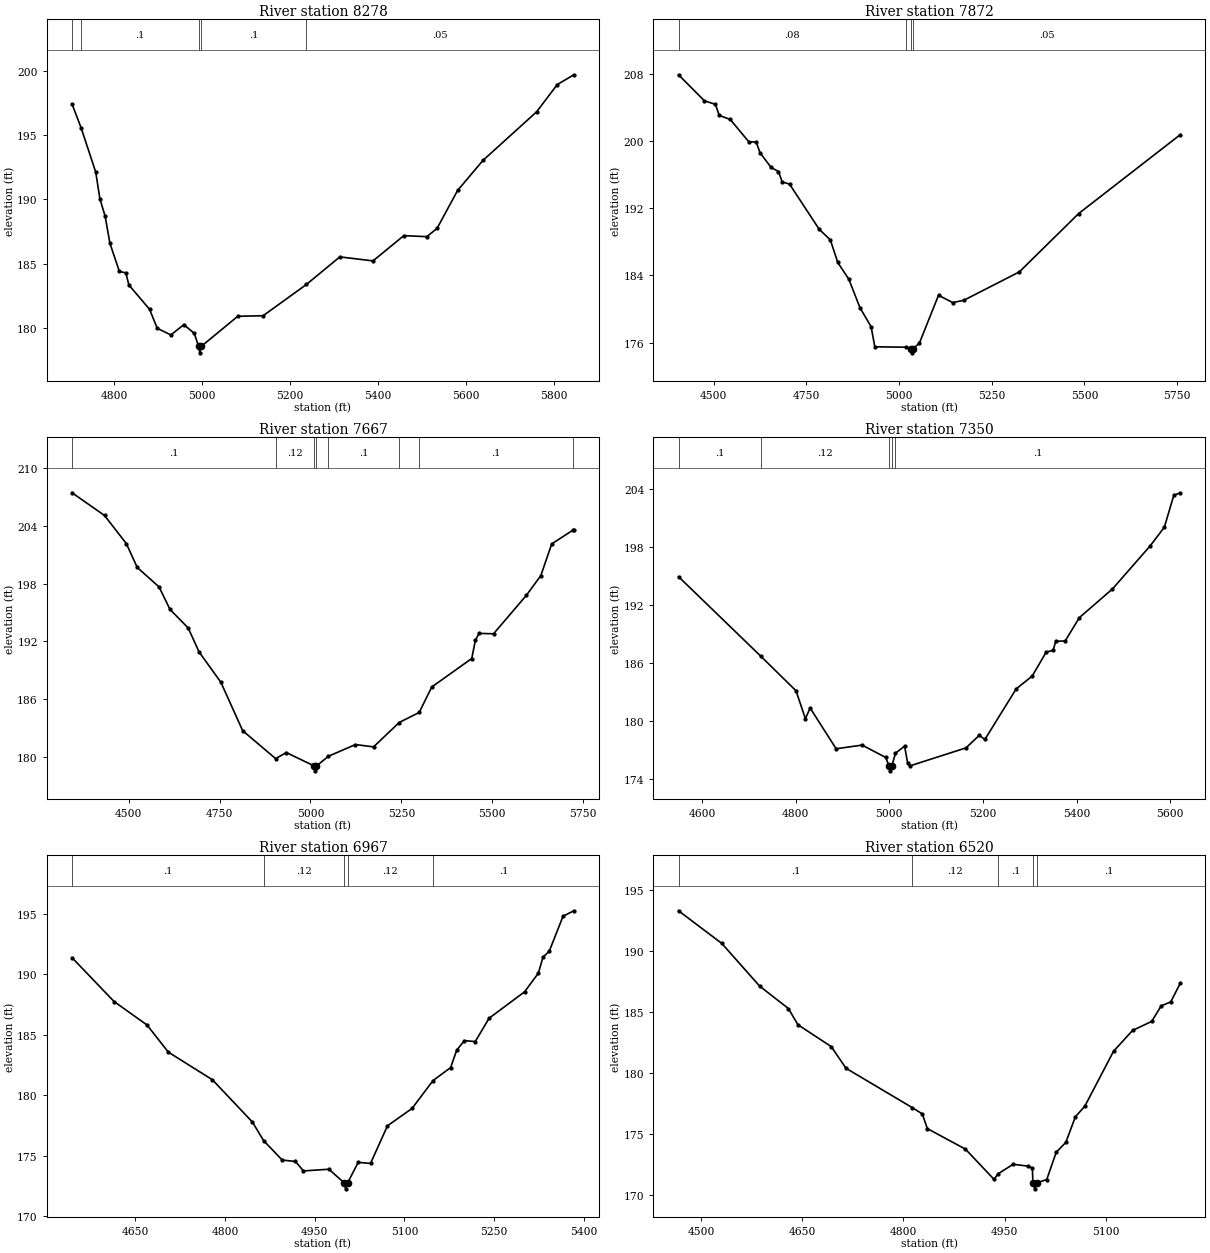
Type RM Length L Ch R = 1 ,8278    ,406,406,406
BEGIN DESCRIPTION:
UNT078 IN SUCR 14.0
END DESCRIPTION:
XS GIS Cut Line= 3
      2259537.75     13365846.87      2259287.72     13365746.85
      2258487.72     13365396.86
#Sta/Elev= 30
  4703.8  197.39  4724.3  195.56  4757.7  192.11  4767.1  190.05  4779.2  188.67
    4790  186.58  4811.5   184.4  4826.3  184.29  4833.1  183.35  4880.2  181.46
  4897.7  179.99  4928.7  179.47  4958.3  180.27  4982.1  179.59  4991.9  178.58
  4994.7  178.08  4997.9  178.58  5081.1  180.92  5138.8  180.96  5237.4  183.39
  5313.4  185.53    5389  185.22  5459.2  187.18  5511.4   187.1  5534.8  187.74
  5581.6  190.69  5639.3  193.02  5761.7   196.8  5808.5  198.91  5846.3  199.67
#Mann= 5 ,-1 , 0
  4703.8     .05       0  4724.3      .1       0  4991.9     .07       0
  4997.9      .1       0  5237.4     .05       0
Bank Sta=4991.9,4997.9
XS Rating Curve= 0 ,0
Exp/Cntr=0.3,0.1

Type RM Length L Ch R = 1 ,7872    ,205,205,205
BEGIN DESCRIPTION:
UNT078 IN SUCR 13.0
END DESCRIPTION:
XS GIS Cut Line= 2
      2259817.43     13365359.91      2258463.32     13365344.29
#Sta/Elev= 30
  4404.7  207.85  4474.4  204.76  4504.4  204.33  4514.4  203.02  4544.4  202.53
  4594.4  199.87  4614.4  199.86  4624.4  198.59  4654.4  196.83  4674.4  196.34
  4684.4  195.11  4704.4  194.84  4784.4  189.46  4814.4  188.21  4834.4  185.52
  4864.4  183.52  4894.4  180.13  4924.4  177.88  4934.4  175.49  5018.7  175.44
  5031.5  175.27  5034.2  174.77  5037.5  175.27  5054.5   175.9  5106.3  181.62
  5144.5  180.75  5174.5  181.02  5324.5   184.4  5484.5  191.34  5758.9  200.73
#Mann= 4 ,-1 , 0
  4404.7     .08       0  5018.7     .05       0  5031.5     .07       0
  5037.5     .05       0
Bank Sta=5031.5,5037.5
XS Rating Curve= 0 ,0
Exp/Cntr=0.3,0.1

Type RM Length L Ch R = 1 ,7667    ,317,317,317
BEGIN DESCRIPTION:
Mapping XS 5b523d56
END DESCRIPTION:
XS GIS Cut Line= 2
        2259807.       13365162.       2258426.8       13365162.
#Sta/Elev= 30
  4344.3  207.44  4433.6  205.08  4493.6  202.16  4523.6  199.68  4583.6  197.66
  4613.6  195.32  4663.6   193.4  4693.6  190.91  4753.6  187.75  4813.6  182.72
  4904.2  179.82  4933.6  180.45  5010.6  179.05  5013.3  178.55  5016.6  179.05
  5049.2  180.06  5123.6  181.28  5173.6  181.04    5244  183.57  5299.2  184.62
  5333.6  187.26  5443.6  190.22  5453.6  192.11  5463.6  192.83  5503.6  192.79
  5593.6  196.77  5633.6  198.83  5663.6  202.13  5720.9  203.53  5724.5  203.55
#Mann= 8 ,-1 , 0
  4344.3      .1       0  4904.2     .12       0  5010.6     .07       0
  5016.6     .12       0  5049.2      .1       0    5244     .05       0
  5299.2      .1       0  5720.9     .05       0
Bank Sta=5010.6,5016.6
XS Rating Curve= 0 ,0
Exp/Cntr=0.3,0.1

Type RM Length L Ch R = 1 ,7350    ,383,383,383
BEGIN DESCRIPTION:
UNT078 IN SUCR 12.0
END DESCRIPTION:
XS GIS Cut Line= 2
      2259566.37     13364915.48      2258503.91      13364776.6
#Sta/Elev= 30
  4549.8  194.95    4725  186.72  4800.6  183.12  4820.7  180.22  4830.8  181.33
  4886.3   177.1  4941.8  177.48  4992.2   176.2  4999.3  175.31    5002  174.81
  5005.3  175.31    5013  176.64  5032.5  177.37  5039.1  175.59  5044.2  175.33
  5163.6  177.19  5191.9  178.49    5204  178.07  5270.8  183.31  5304.8  184.63
  5335.1  187.14  5349.7   187.3  5355.2  188.25  5375.4  188.28  5405.7   190.7
  5476.3  193.67  5556.9  198.14  5587.2  200.08  5607.4  203.39  5621.3  203.65
#Mann= 5 ,-1 , 0
  4549.8      .1       0    4725     .12       0  4999.3     .07       0
  5005.3     .12       0    5013      .1       0
Bank Sta=4999.3,5005.3
XS Rating Curve= 0 ,0
Exp/Cntr=0.3,0.1

Type RM Length L Ch R = 1 ,6967    ,447,447,447
BEGIN DESCRIPTION:
UNT078 IN SUCR 11.0
END DESCRIPTION:
XS GIS Cut Line= 3
      2259537.68     13364646.84      2259137.72     13364496.85
      2258737.69     13364396.85
#Sta/Elev= 30
    4544  191.38  4614.3  187.76  4669.4  185.82    4705  183.58  4778.9  181.29
  4845.7   177.8  4864.4  176.27  4895.5  174.66  4917.8  174.54  4931.1  173.76
  4973.7   173.9  4999.1  172.78  5001.8  172.28  5005.1  172.78  5022.7  174.47
  5043.3  174.38  5071.7  177.49  5112.9  178.93  5147.9  181.23  5177.3   182.3
  5187.6  183.75  5200.5  184.53  5218.5  184.45  5241.7  186.38    5301  188.56
  5324.2  190.11  5331.9  191.44  5342.2   191.9  5365.4  194.81  5383.5  195.26
#Mann= 5 ,-1 , 0
    4544      .1       0  4864.4     .12       0  4999.1     .07       0
  5005.1     .12       0  5147.9      .1       0
Bank Sta=4999.1,5005.1
XS Rating Curve= 0 ,0
Exp/Cntr=0.3,0.1

Type RM Length L Ch R = 1 ,6520    ,691,691,691
BEGIN DESCRIPTION:
UNT078 IN SUCR 10.0
END DESCRIPTION:
XS GIS Cut Line= 3
      2259687.74     13364446.87      2259287.72     13364096.85
      2259137.69     13363946.83
#Sta/Elev= 30
  4466.8  193.28  4530.9  190.61  4586.9  187.12  4629.6  185.28  4643.8  183.95
  4693.2  182.16    4715  180.39  4813.4  177.16    4828  176.66  4835.6  175.45
    4892  173.77  4934.3   171.3  4940.4  171.75  4962.7  172.53  4984.6  172.38
  4991.2  172.22    4992  171.02  4994.8  170.52    4998  171.02  5012.5  171.28
  5026.6  173.52  5040.8  174.32  5054.9  176.41    5069  177.29  5111.5  181.78
  5139.8  183.49    5168  184.22  5182.2   185.5  5196.3  185.82  5210.5  187.36
#Mann= 5 ,-1 , 0
  4466.8      .1       0  4813.4     .12       0  4940.4      .1       0
    4992     .07       0    4998      .1       0
Bank Sta=4992,4998
XS Rating Curve= 0 ,0
Exp/Cntr=0.3,0.1

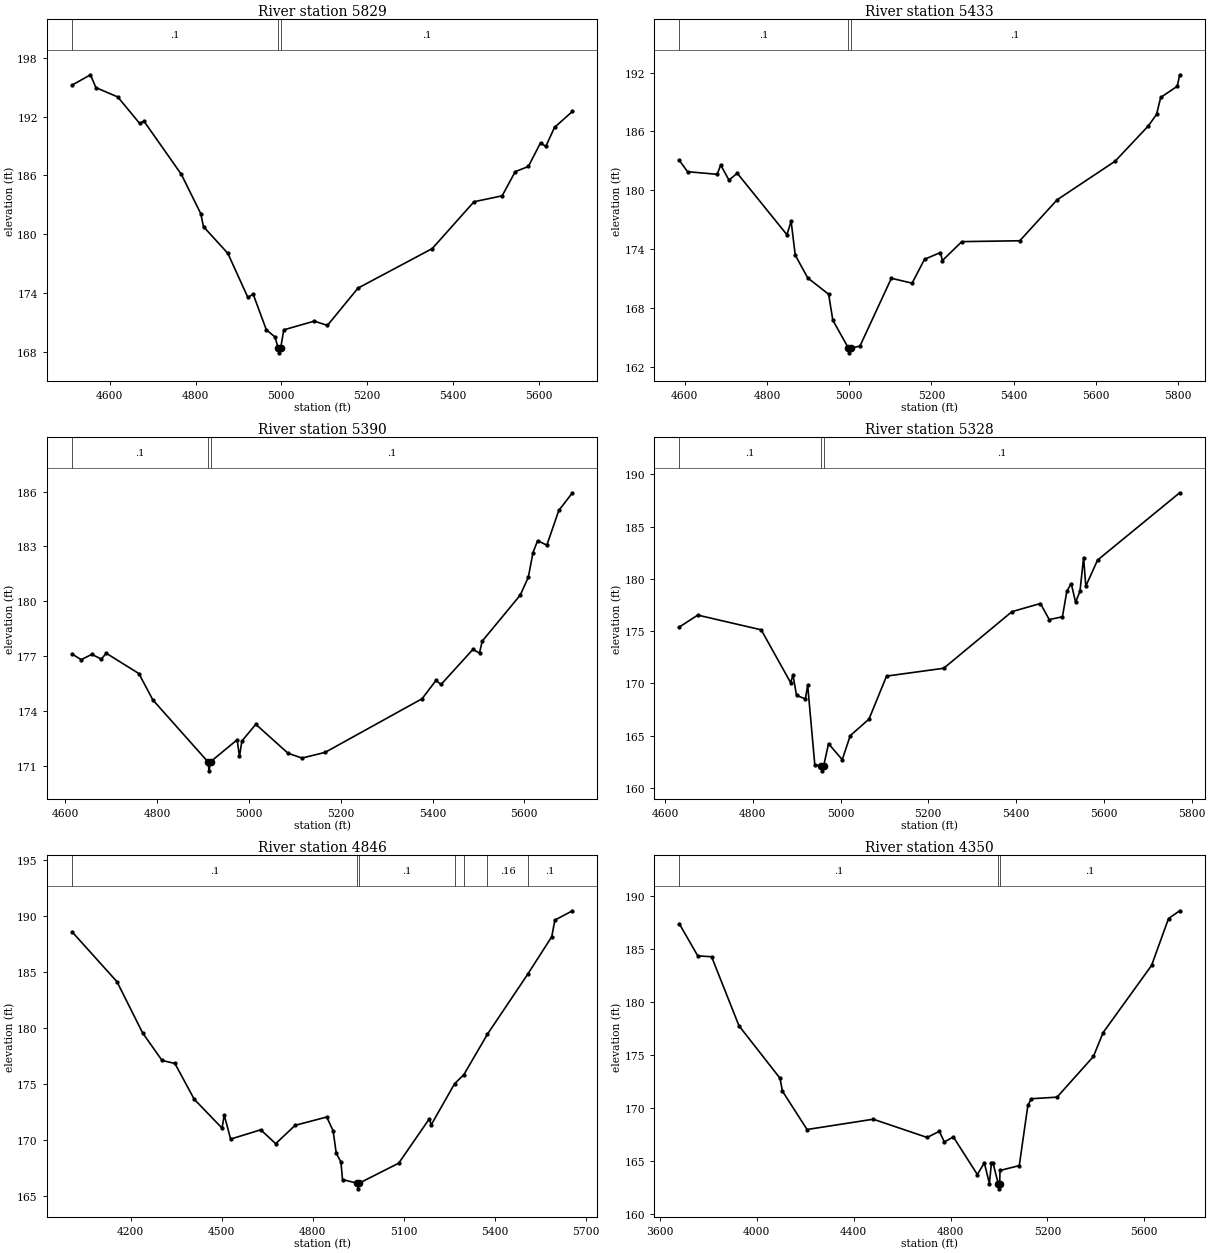
Type RM Length L Ch R = 1 ,5829    ,396,396,396
BEGIN DESCRIPTION:
UNT078 IN SUCR 9.0
END DESCRIPTION:
XS GIS Cut Line= 2
      2260302.54     13363790.49      2259156.69     13363568.27
#Sta/Elev= 30
  4511.9  195.19  4554.9  196.25  4567.7  194.94  4618.7  193.99  4669.6   191.3
  4679.8  191.52  4766.9  186.11  4812.2  182.11  4818.6  180.78  4875.4  178.06
    4922  173.58  4934.5   173.9    4965  170.29  4985.4  169.54  4992.6  168.43
  4995.3  167.93  4998.6  168.43  5005.8  170.27  5077.1  171.16  5107.6  170.72
  5178.9  174.52  5352.1  178.55  5449.5  183.32  5515.1  183.92  5545.6  186.38
  5576.2  186.91  5604.7  189.32  5616.9  188.95  5637.3  190.89  5679.1  192.52
#Mann= 3 ,-1 , 0
  4511.9      .1       0  4992.6     .07       0  4998.6      .1       0
Bank Sta=4992.6,4998.6
XS Rating Curve= 0 ,0
Exp/Cntr=0.3,0.1

Type RM Length L Ch R = 1 ,5433    ,43,43,43
BEGIN DESCRIPTION:
UNT078 IN SUCR 8.0
END DESCRIPTION:
XS GIS Cut Line= 4
       2260367.9     13363362.66      2260070.98     13363326.19
      2259847.02     13363367.86      2259161.94     13363454.58
#Sta/Elev= 30
  4586.6  183.06  4606.9  181.89  4678.9  181.62  4687.5  182.57  4707.7  181.03
  4727.8  181.73  4848.7  175.45  4858.8  176.84  4868.9  173.37  4899.2  171.05
  4950.1  169.38  4960.3  166.73    4998   163.9  5000.7   163.4    5004   163.9
  5026.2  164.08  5102.7  171.01  5153.2  170.51  5183.4  172.95  5221.8  173.63
  5226.9  172.82  5274.1  174.75  5415.2  174.84    5506  179.02  5647.1  182.96
  5727.7  186.55  5747.9  187.74    5758  189.47  5798.3  190.61  5804.1  191.78
#Mann= 3 ,-1 , 0
  4586.6      .1       0    4998     .07       0    5004      .1       0
Bank Sta=4998,5004
XS Rating Curve= 0 ,0
Exp/Cntr=0.3,0.1

Type RM Length L Ch R = 1 ,5390    ,62,62,62
BEGIN DESCRIPTION:
Mapping XS a9318939
END DESCRIPTION:
XS GIS Cut Line= 3
       2260340.1     13363227.23      2259998.06     13363300.15
      2259262.29     13363385.18
#Sta/Elev= 30
  4614.4  177.11  4634.4   176.8  4657.7  177.09  4678.2  176.83    4689  177.15
    4760  176.04  4790.7  174.59  4910.4  171.21  4913.1  170.71  4916.4  171.21
  4974.2  172.41  4979.3   171.5  4984.6  172.34  5014.8  173.26  5085.3  171.67
  5115.5  171.41  5165.8  171.72  5377.2  174.66  5407.4  175.66  5418.5  175.44
  5487.9  177.36  5502.3  177.16  5508.1  177.81  5591.2  180.34  5608.7  181.32
  5618.8  182.66  5628.9  183.32    5649  183.07    5675  184.97  5704.8  185.94
#Mann= 3 ,-1 , 0
  4614.4      .1       0  4910.4     .07       0  4916.4      .1       0
Bank Sta=4910.4,4916.4
XS Rating Curve= 0 ,0
Exp/Cntr=0.3,0.1

Type RM Length L Ch R = 1 ,5328    ,482,482,482
BEGIN DESCRIPTION:
UNT078 IN SUCR 7.0
END DESCRIPTION:
XS GIS Cut Line= 3
      2260324.45     13363140.43      2259947.71      13363249.8
      2259201.06     13363294.84
#Sta/Elev= 30
  4632.5  175.38  4674.7  176.53  4819.3  175.12  4886.4  170.06  4891.7   170.8
  4899.8  168.84    4920  168.51  4925.2  169.81  4941.5  162.17  4955.8  162.12
  4958.5  161.62  4961.8  162.12  4972.7  164.22    5004  162.69  5022.2  164.99
  5064.9  166.57  5104.9  170.69  5235.2  171.44  5390.7  176.86  5455.6  177.64
  5475.6   176.1  5505.7  176.37  5515.7  178.81  5525.7  179.55  5535.7  177.76
  5545.7  178.82  5553.9  182.04  5558.9   179.3  5585.8   181.8  5772.8  188.24
#Mann= 3 ,-1 , 0
  4632.5      .1       0  4955.8     .07       0  4961.8      .1       0
Bank Sta=4955.8,4961.8
XS Rating Curve= 0 ,0
Exp/Cntr=0.3,0.1

Type RM Length L Ch R = 1 ,4846    ,496,496,496
BEGIN DESCRIPTION:
UNT078 IN SUCR 6.0
END DESCRIPTION:
XS GIS Cut Line= 3
      2260746.94     13363366.85      2260184.46      13362839.1
      2259331.47     13362631.05
#Sta/Elev= 30
  4006.4  188.61  4154.6  184.15  4239.1  179.58  4303.1  177.12  4345.6  176.85
  4409.1  173.66  4500.9  171.08  4508.2  172.24  4529.2   170.1  4628.4  170.93
  4677.7  169.69  4741.7  171.33  4845.9  172.07    4867  170.84  4877.3  168.83
  4892.7  168.06  4897.9  166.49  4946.3  166.16  4949.1  165.66  4952.3  166.16
  5083.1  167.95  5184.5  171.93  5189.7  171.35  5267.2  175.04  5297.8  175.85
  5375.7  179.47  5509.3  184.86  5587.5  188.17  5597.8  189.65  5655.7  190.48
#Mann= 7 ,-1 , 0
  4006.4      .1       0  4946.3     .07       0  4952.3      .1       0
  5267.2     .16       0  5297.8      .1       0  5375.7     .16       0
  5509.3      .1       0
Bank Sta=4946.3,4952.3
XS Rating Curve= 0 ,0
Exp/Cntr=0.3,0.1

Type RM Length L Ch R = 1 ,4350    ,1000,1000,1000
BEGIN DESCRIPTION:
UNT078 IN SUCR 5.0
END DESCRIPTION:
XS GIS Cut Line= 5
      2260812.26     13363310.68      2260505.19     13363044.08
      2260220.65     13362504.66      2259844.19     13362227.99
      2259261.78     13362248.79
#Sta/Elev= 30
  3679.7  187.39  3756.4  184.35  3813.4  184.27  3926.3  177.77  4095.9  172.82
  4105.8  171.61  4207.6  167.99    4481  168.96  4703.5  167.24  4753.7  167.82
  4774.5  166.82  4811.6  167.29  4910.8  163.75  4939.6  164.85  4960.5   162.9
  4968.9  164.81  4975.1  164.86    4997   162.9  4999.8   162.4    5003   162.9
  5004.4  164.13  5083.9  164.59  5119.4  170.27    5134  170.89  5239.9  171.04
    5390  174.87  5430.1  177.12  5630.2  183.45  5700.2  187.87  5746.2   188.6
#Mann= 3 ,-1 , 0
  3679.7      .1       0    4997     .07       0    5003      .1       0
Bank Sta=4997,5003
XS Rating Curve= 0 ,0
Exp/Cntr=0.3,0.1

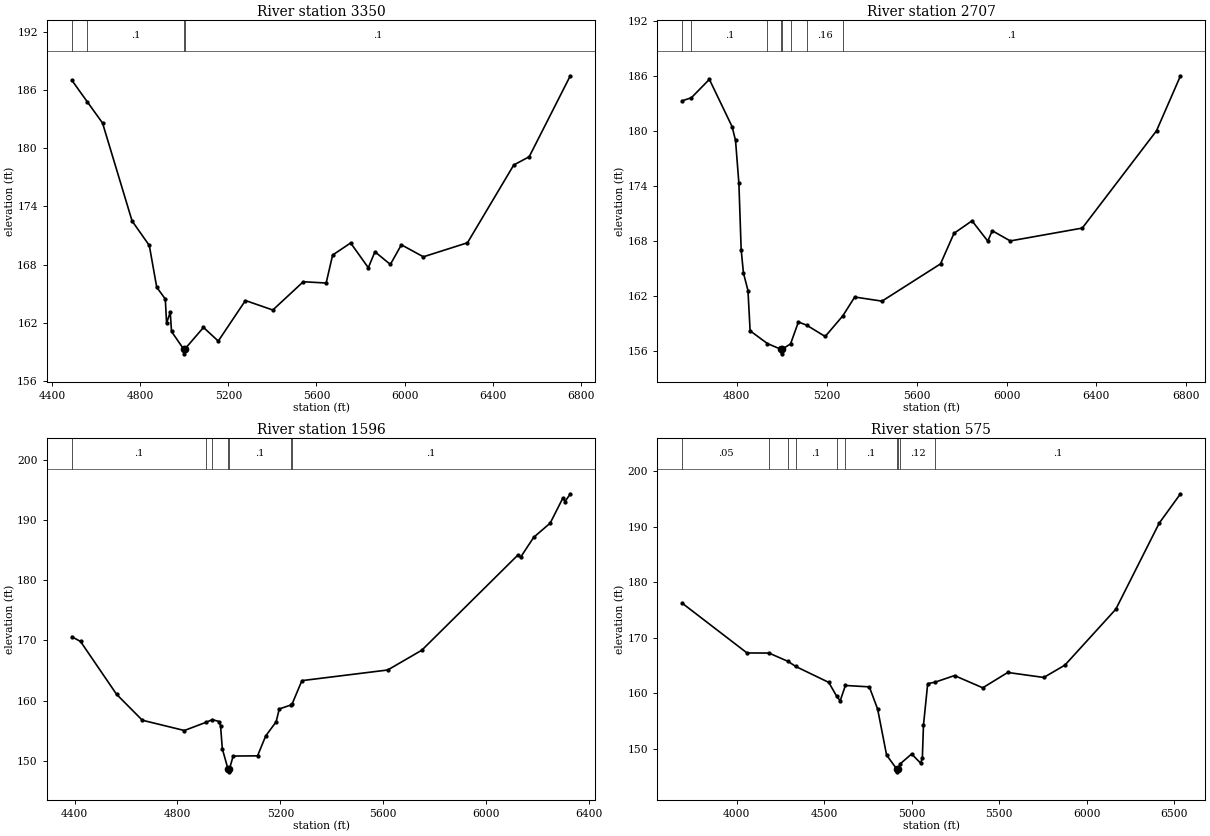
Type RM Length L Ch R = 1 ,3350    ,643,643,643
BEGIN DESCRIPTION:
UNT078 IN SUCR 5.1
END DESCRIPTION:
XS GIS Cut Line= 4
      2261062.23     13362991.19      2260697.65     13362262.05
      2260250.21     13362166.13      2259261.09     13362155.73
#Sta/Elev= 30
  4490.1  187.04  4560.5   184.8  4629.1  182.63  4763.3   172.5  4841.4  169.97
  4875.1  165.65    4914  164.44  4919.8  161.95  4936.4  163.07  4942.2  161.08
    4997  159.27  4999.8  158.77    5003  159.27  5087.3   161.5  5154.4  160.09
  5277.6  164.28    5402   163.3  5540.1  166.22    5644  166.09  5673.4  168.98
  5755.2  170.23  5835.4  167.67  5865.4  169.32  5935.4  168.01  5985.4  170.04
  6085.4   168.8  6285.4  170.25  6495.5  178.29  6565.5  179.14  6752.1  187.51
#Mann= 4 ,-1 , 0
  4490.1     .05       0  4560.5      .1       0    4997     .07       0
    5003      .1       0
Bank Sta=4997,5003
XS Rating Curve= 0 ,0
Exp/Cntr=0.3,0.1

Type RM Length L Ch R = 1 ,2707    ,1111,1111,1111
BEGIN DESCRIPTION:
Mapping XS d69fe6cd
END DESCRIPTION:
XS GIS Cut Line= 4
      2261517.84     13362047.43      2260615.02     13362179.38
      2259677.52     13362130.76      2259311.05     13362144.59
#Sta/Elev= 30
  4556.3  183.27  4597.7  183.61  4677.7  185.61  4778.8  180.46  4794.1  178.96
  4809.1  174.27  4819.2  167.06  4829.3  164.52  4849.5   162.6    4859  158.22
    4936  156.83  4995.9  156.21  4998.7  155.71  5001.9  156.21  5039.1   156.8
  5073.9  159.18  5110.8  158.83  5193.1   157.6  5271.5  159.85  5324.5   161.9
  5445.8  161.45  5706.3  165.51  5766.4  168.84  5846.5   170.2  5916.6  167.99
  5936.6  169.12  6016.7  168.01  6337.2  169.41  6667.5  180.01  6774.2     186
#Mann= 8 ,-1 , 0
  4556.3     .05       0  4597.7      .1       0    4936     .16       0
  4995.9     .07       0  5001.9     .16       0  5039.1      .1       0
  5110.8     .16       0  5271.5      .1       0
Bank Sta=4995.9,5001.9
XS Rating Curve= 0 ,0
Exp/Cntr=0.3,0.1

Type RM Length L Ch R = 1 ,1596    ,1021,1021,1021
BEGIN DESCRIPTION:
UNT078 IN SUCR 2.0
END DESCRIPTION:
XS GIS Cut Line= 4
      2260881.14     13361441.36       2260512.5     13361426.21
      2259648.93     13361714.06      2259124.51     13362112.42
#Sta/Elev= 30
  4389.6  170.61  4423.1  169.83  4563.2  161.04  4663.3  156.72  4826.8  155.01
  4910.9  156.37  4935.7  156.82  4962.4   156.5  4967.6  155.78  4974.4  151.97
  4996.3  148.63    4999  148.13  5002.3  148.63  5016.6  150.76  5111.4  150.79
  5143.1   154.1  5183.7  156.46  5195.8  158.59  5240.5  159.25  5246.2  159.47
  5283.9  163.31  5617.4  165.08  5749.9  168.37  6122.1  184.15    6135  183.91
  6185.2  187.17  6249.1  189.52    6299  193.74  6307.2  193.12  6327.4  194.41
#Mann= 7 ,-1 , 0
  4389.6      .1       0  4910.9     .12       0  4935.7      .1       0
  4996.3     .07       0  5002.3      .1       0  5240.5     .12       0
  5246.2      .1       0
Bank Sta=4996.3,5002.3
XS Rating Curve= 0 ,0
Exp/Cntr=0.3,0.1

Type RM Length L Ch R = 1 ,575     ,0,0,0
BEGIN DESCRIPTION:
UNT078 IN SUCR 1.0
END DESCRIPTION:
XS GIS Cut Line= 5
      2261087.21     13361491.85      2260524.74     13360977.99
      2260344.19     13360727.99      2259649.74     13360873.82
      2258837.21     13361568.29
#Sta/Elev= 30
  3688.3  176.22  4059.5  167.25  4184.9  167.23  4294.8  165.72  4337.2  164.83
  4526.8  161.95  4571.2  159.49  4591.8  158.63  4621.7   161.4  4758.5  161.15
    4806  157.15  4857.1  148.88  4915.3  146.36  4918.1  145.86  4921.3  146.36
  4936.5  147.34  5000.2  149.07  5051.3  147.44  5061.5   148.3  5067.9  154.23
  5092.1  161.72  5134.8     162  5245.4  163.18  5406.8  160.98  5549.7  163.74
  5755.6  162.84  5876.3  165.06  6167.3  175.12  6415.4  190.61    6537  195.89
#Mann= 10 ,-1 , 0
  3688.3     .05       0  4184.9      .1       0  4294.8     .05       0
  4337.2      .1       0  4571.2     .05       0  4621.7      .1       0
  4915.3     .07       0  4921.3      .1       0  4936.5     .12       0
  5134.8      .1       0
Bank Sta=4915.3,4921.3
XS Rating Curve= 0 ,0
Exp/Cntr=0.3,0.1

Chan Stop Cuts=-1
Use User Specified Reach Order=0
Composite Channel Slope=5