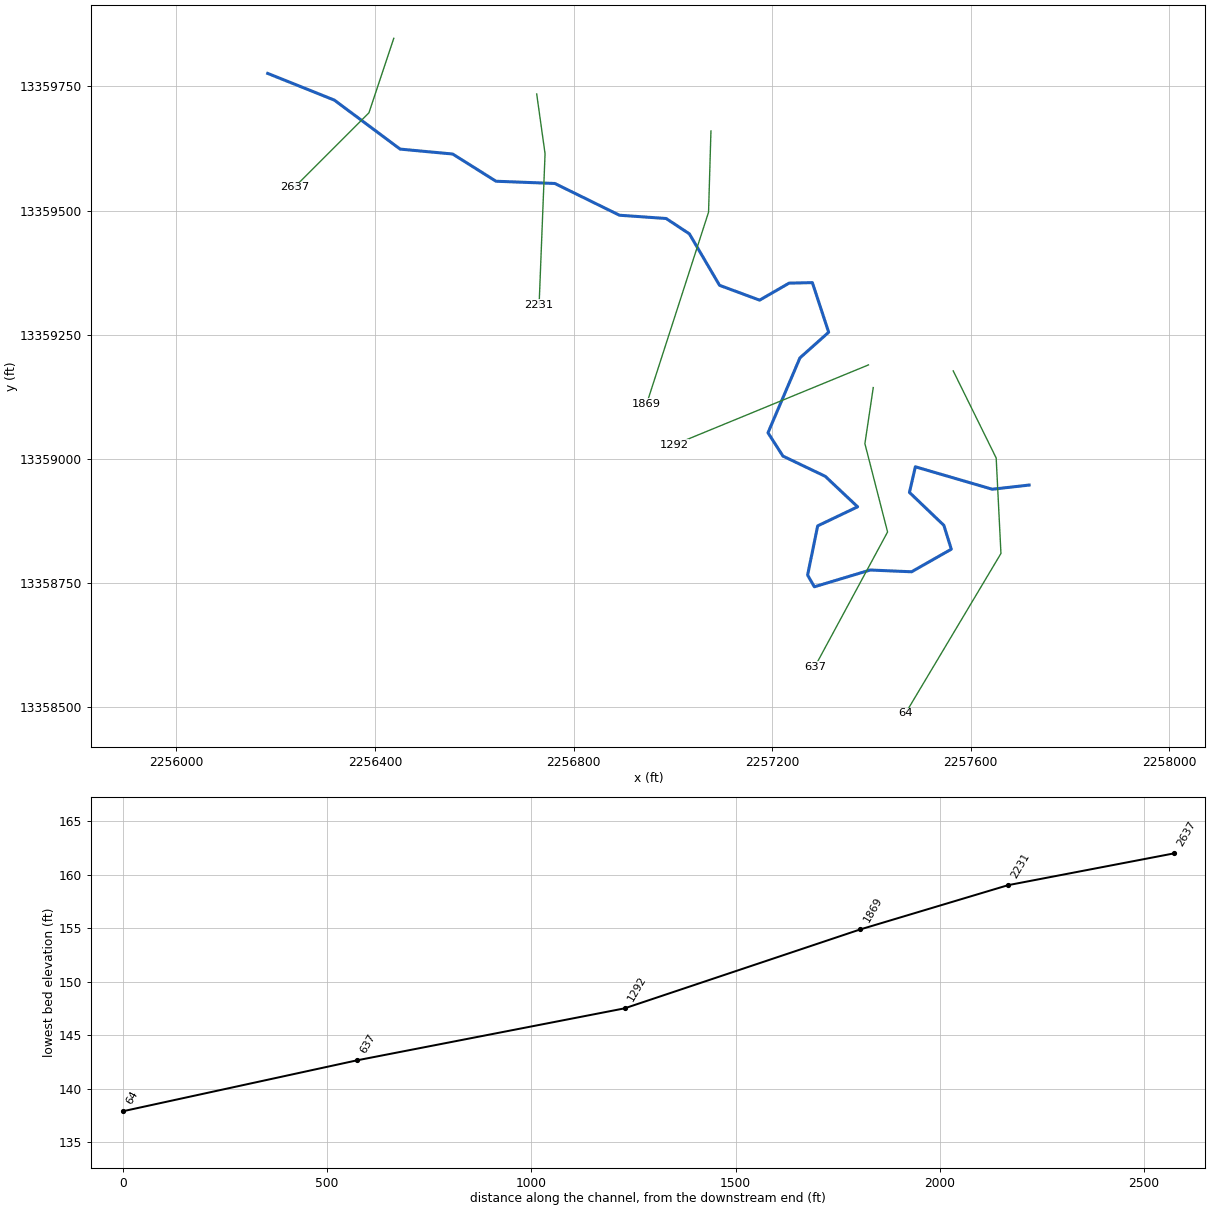
--- UNT079 IN SUCR.prj (project) ---

Proj Title=UNT079 IN SUCR Base Level Engineering
Current Plan=p01
Default Exp/Contr=0.3,0.1
English Units
Geom File=g01
Flow File=f01
Plan File=p01
BEGIN DESCRIPTION:
UNT079 IN SUCR
END DESCRIPTION:

--- UNT079 IN SUCR.p01 (plan) ---

Plan Title=Multiple Run
Short Identifier=Multiple
Geom File=g01
Flow File=f01
Subcritical Flow
K Sum by GR= 0
Std Step Tol= 0.01
Critical Tol= 0.01
Num of Std Step Trials= 20
Max Error Tol= 0.3
Flow Tol Ratio= 0.001
Split Flow NTrial= 30
Split Flow Tol= 0.02
Split Flow Ratio= 0.02
Log Output Level= 0
Friction Slope Method= 1
Unsteady Friction Slope Method= 2
Unsteady Bridges Friction Slope Method= 1
Parabolic Critical Depth
Global Vel Dist=  1 , 1 , 1
Global Log Level= 0
CheckData=True
Encroach Param= -1, 0, 0, 0
BEGIN DESCRIPTION:
Multiple Run
END DESCRIPTION:

--- UNT079 IN SUCR.f01 (steady flow) ---

Flow Title=Multiple
Number of Profiles=7
Profile Names=10-year,25-year,50-year,1pct_min,100-year,1pct_plu,500-year
River Rch & RM= UNT079 IN SUCR,Reach-1,2637
     195     269     329     298     403     545     611
Boundary for River Rch & Prof#=UNT079 IN SUCR,Reach-1,1
Up Type=0
Dn Type=3
Dn Slope=0.005
Boundary for River Rch & Prof#=UNT079 IN SUCR,Reach-1,2
Up Type=0
Dn Type=3
Dn Slope=0.005
Boundary for River Rch & Prof#=UNT079 IN SUCR,Reach-1,3
Up Type=0
Dn Type=3
Dn Slope=0.005
Boundary for River Rch & Prof#=UNT079 IN SUCR,Reach-1,4
Up Type=0
Dn Type=3
Dn Slope=0.005
Boundary for River Rch & Prof#=UNT079 IN SUCR,Reach-1,5
Up Type=0
Dn Type=3
Dn Slope=0.005
Boundary for River Rch & Prof#=UNT079 IN SUCR,Reach-1,6
Up Type=0
Dn Type=3
Dn Slope=0.005
Boundary for River Rch & Prof#=UNT079 IN SUCR,Reach-1,7
Up Type=0
Dn Type=3
Dn Slope=0.005

--- UNT079 IN SUCR.g01 (geometry) ---

Geom Title=Existing Conditions

River Reach=UNT079 IN SUCR,Reach-1
Reach XY= 30
      2256183.83     13359776.21      2256318.07     13359722.40
      2256450.60     13359623.70      2256556.40     13359613.81
      2256643.69     13359558.98      2256762.26     13359554.44
      2256892.45     13359490.50      2256986.47     13359483.88
      2257033.31     13359452.97      2257094.05     13359349.29
      2257174.78     13359319.40      2257234.22     13359353.68
      2257281.10     13359354.72      2257313.91     13359254.72
      2257256.02     13359203.06      2257191.69     13359052.22
      2257221.77     13359005.24      2257306.96     13358964.55
      2257372.24     13358903.05      2257291.77     13358864.62
      2257271.48     13358765.47      2257285.08     13358741.91
      2257397.60     13358775.70      2257481.00     13358772.15
      2257560.95     13358817.62      2257546.02     13358865.69
      2257476.68     13358932.06      2257488.60     13358983.67
      2257643.49     13358938.46      2257717.72     13358946.86

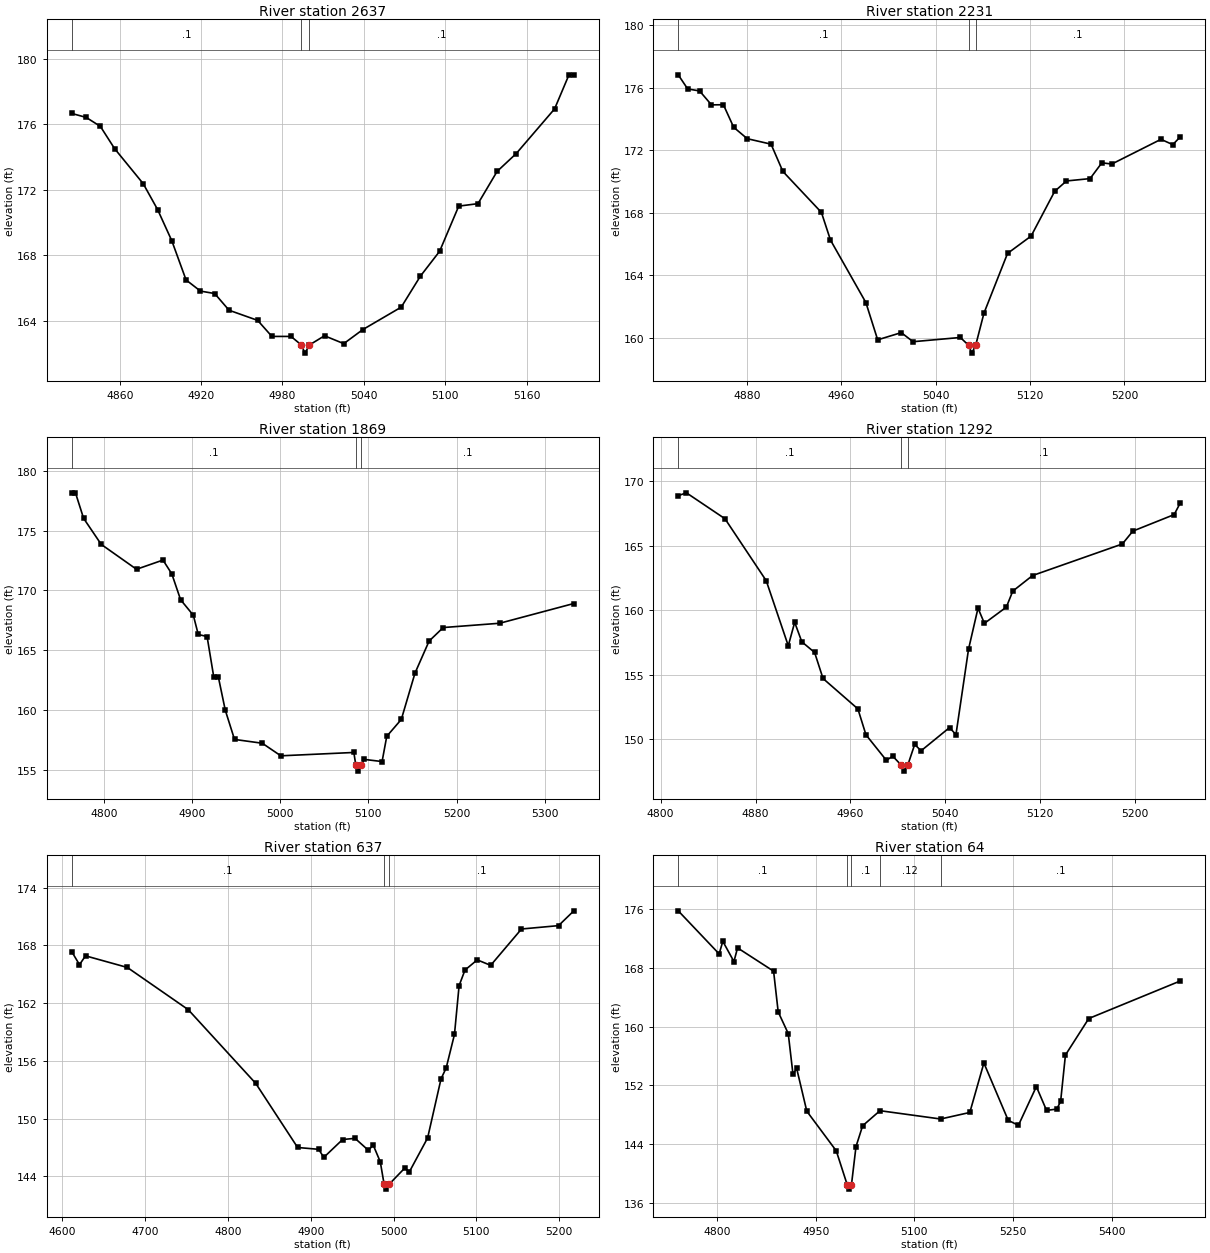
Type RM Length L Ch R = 1,2637,406,406,406
BEGIN DESCRIPTION:
UNT079 IN SUCR 5.0
END DESCRIPTION:
XS GIS Cut Line= 3
      2256437.73     13359846.87      2256387.72     13359696.85
      2256237.70     13359546.83
#Sta/Elev= 30
  4824.6  176.65  4835.2  176.41  4845.7  175.86  4856.2  174.50  4877.3  172.36
  4887.9  170.78  4898.4  168.87  4908.9  166.48  4919.5  165.80  4930.0  165.65
  4940.6  164.63  4961.7  164.01  4972.2  163.03  4986.3  163.03  4993.9  162.51
  4996.6  162.01  4999.9  162.51  5011.0  163.07  5025.2  162.59  5039.3  163.45
  5067.6  164.82  5081.7  166.71  5095.9  168.23  5110.0  170.99  5124.2  171.14
  5138.3  173.11  5152.4  174.20  5180.7  176.93  5191.3  179.01  5194.9  179.01
#Mann=3,-1,0
  4824.6     0.1       0  4993.9    0.07       0  4999.9     0.1       0
Bank Sta=4993.9,4999.9
Exp/Cntr=0.3,0.1

Type RM Length L Ch R = 1,2231,362,362,362
BEGIN DESCRIPTION:
UNT079 IN SUCR 4.0
END DESCRIPTION:
XS GIS Cut Line= 3
      2256725.71     13359734.75      2256742.54     13359614.51
      2256730.57     13359310.46
#Sta/Elev= 30
  4821.7  176.82  4829.7  175.92  4839.8  175.79  4849.9  174.90  4860.0  174.91
  4868.7  173.47  4880.2  172.74  4900.4  172.39  4910.4  170.65  4943.1  168.03
  4950.8  166.26  4980.8  162.27  4990.8  159.89  5010.8  160.35  5020.8  159.77
  5060.9  160.04  5067.9  159.54  5070.6  159.04  5073.9  159.54  5080.9  161.59
  5100.9  165.41  5120.9  166.52  5140.9  169.38  5150.9  170.04  5170.9  170.19
  5180.9  171.20  5189.3  171.12  5231.0  172.70  5241.0  172.36  5247.4  172.86
#Mann=3,-1,0
  4821.7     0.1       0  5067.9    0.07       0  5073.9     0.1       0
Bank Sta=5067.9,5073.9
Exp/Cntr=0.3,0.1

Type RM Length L Ch R = 1,1869,577,577,577
BEGIN DESCRIPTION:
Mapping XS 82c5fbaa
END DESCRIPTION:
XS GIS Cut Line= 3
      2257076.75     13359660.23      2257071.94     13359496.69
      2256947.29     13359110.74
#Sta/Elev= 30
  4763.8  178.16  4768.0  178.16  4777.2  176.03  4797.2  173.85  4837.2  171.77
  4867.2  172.54  4877.2  171.39  4887.2  169.22  4901.6  167.93  4907.2  166.32
  4917.2  166.15  4924.8  162.76  4930.0  162.76  4937.8  160.00  4948.3  157.55
  4979.8  157.23  5000.8  156.18  5083.6  156.46  5085.8  155.40  5088.6  154.90
  5091.8  155.40  5095.4  155.88  5115.6  155.70  5120.9  157.81  5137.4  159.22
  5152.9  163.09  5168.9  165.77  5184.9  166.90  5249.0  167.26  5333.0  168.91
#Mann=3,-1,0
  4763.8     0.1       0  5085.8    0.07       0  5091.8     0.1       0
Bank Sta=5085.8,5091.8
Exp/Cntr=0.3,0.1

Type RM Length L Ch R = 1,1292,655,655,655
BEGIN DESCRIPTION:
UNT079 IN SUCR 3.0
END DESCRIPTION:
XS GIS Cut Line= 2
      2257394.12     13359188.92      2257002.51     13359027.96
#Sta/Elev= 30
  4814.8  168.90  4821.7  169.12  4854.2  167.11  4889.0  162.30  4907.6  157.25
  4913.0  159.07  4919.0  157.56  4929.8  156.73  4936.9  154.71  4966.3  152.35
  4973.1  150.34  4990.3  148.36  4995.7  148.68  5002.5  148.02  5005.3  147.52
  5008.5  148.02  5014.2  149.59  5019.6  149.10  5043.6  150.90  5049.0  150.35
  5059.6  156.98  5067.6  160.17  5073.0  158.99  5091.5  160.25  5096.9  161.49
  5113.6  162.70  5189.3  165.15  5198.2  166.15  5233.0  167.43  5238.2  168.34
#Mann=3,-1,0
  4814.8     0.1       0  5002.5    0.07       0  5008.5     0.1       0
Bank Sta=5002.5,5008.5
Exp/Cntr=0.3,0.1

Type RM Length L Ch R = 1,637,573,573,573
BEGIN DESCRIPTION:
UNT079 IN SUCR 2.0
END DESCRIPTION:
XS GIS Cut Line= 4
      2257403.75     13359143.27      2257386.92     13359030.24
      2257432.60     13358852.31      2257286.28     13358581.26
#Sta/Elev= 30
  4611.6  167.35  4620.9  166.00  4628.2  166.92  4678.7  165.71  4752.2  161.32
  4833.7  153.65  4884.2  146.99  4909.6  146.80  4915.8  145.96  4938.5  147.82
  4953.5  147.94  4969.7  146.69  4975.4  147.25  4984.0  145.49  4988.6  143.16
  4991.3  142.66  4994.6  143.16  5013.5  144.85  5019.2  144.48  5041.1  147.98
  5057.3  154.13  5063.5  155.26  5073.5  158.74  5079.1  163.82  5086.2  165.44
  5101.0  166.50  5117.2  165.93  5154.4  169.71  5199.1  170.06  5217.6  171.60
#Mann=3,-1,0
  4611.6     0.1       0  4988.6    0.07       0  4994.6     0.1       0
Bank Sta=4988.6,4994.6
Exp/Cntr=0.3,0.1

Type RM Length L Ch R = 1,64,0,0,0
BEGIN DESCRIPTION:
UNT079 IN SUCR 1.0
END DESCRIPTION:
XS GIS Cut Line= 4
      2257564.84     13359176.92      2257651.40     13359001.39
      2257661.02     13358809.03      2257468.69     13358486.89
#Sta/Elev= 30
  4741.0  175.76  4803.2  169.90  4808.8  171.61  4825.7  168.86  4831.2  170.72
  4886.0  167.55  4893.0  162.01  4908.3  159.06  4915.5  153.52  4921.1  154.32
  4936.5  148.50  4981.3  143.11  4998.3  138.40  5001.1  137.90  5004.3  138.40
  5011.3  143.68  5021.4  146.52  5047.8  148.57  5140.0  147.44  5184.4  148.33
  5205.8  155.06  5242.8  147.26  5258.3  146.58  5285.6  151.85  5301.1  148.61
  5316.7  148.79  5322.5  149.84  5329.8  156.14  5365.3  161.11  5504.5  166.22
#Mann=5,-1,0
  4741.0     0.1       0  4998.3    0.07       0  5004.3     0.1       0
  5047.8    0.12       0  5140.0     0.1       0
Bank Sta=4998.3,5004.3
Exp/Cntr=0.3,0.1

Chan Stop Cuts=-1