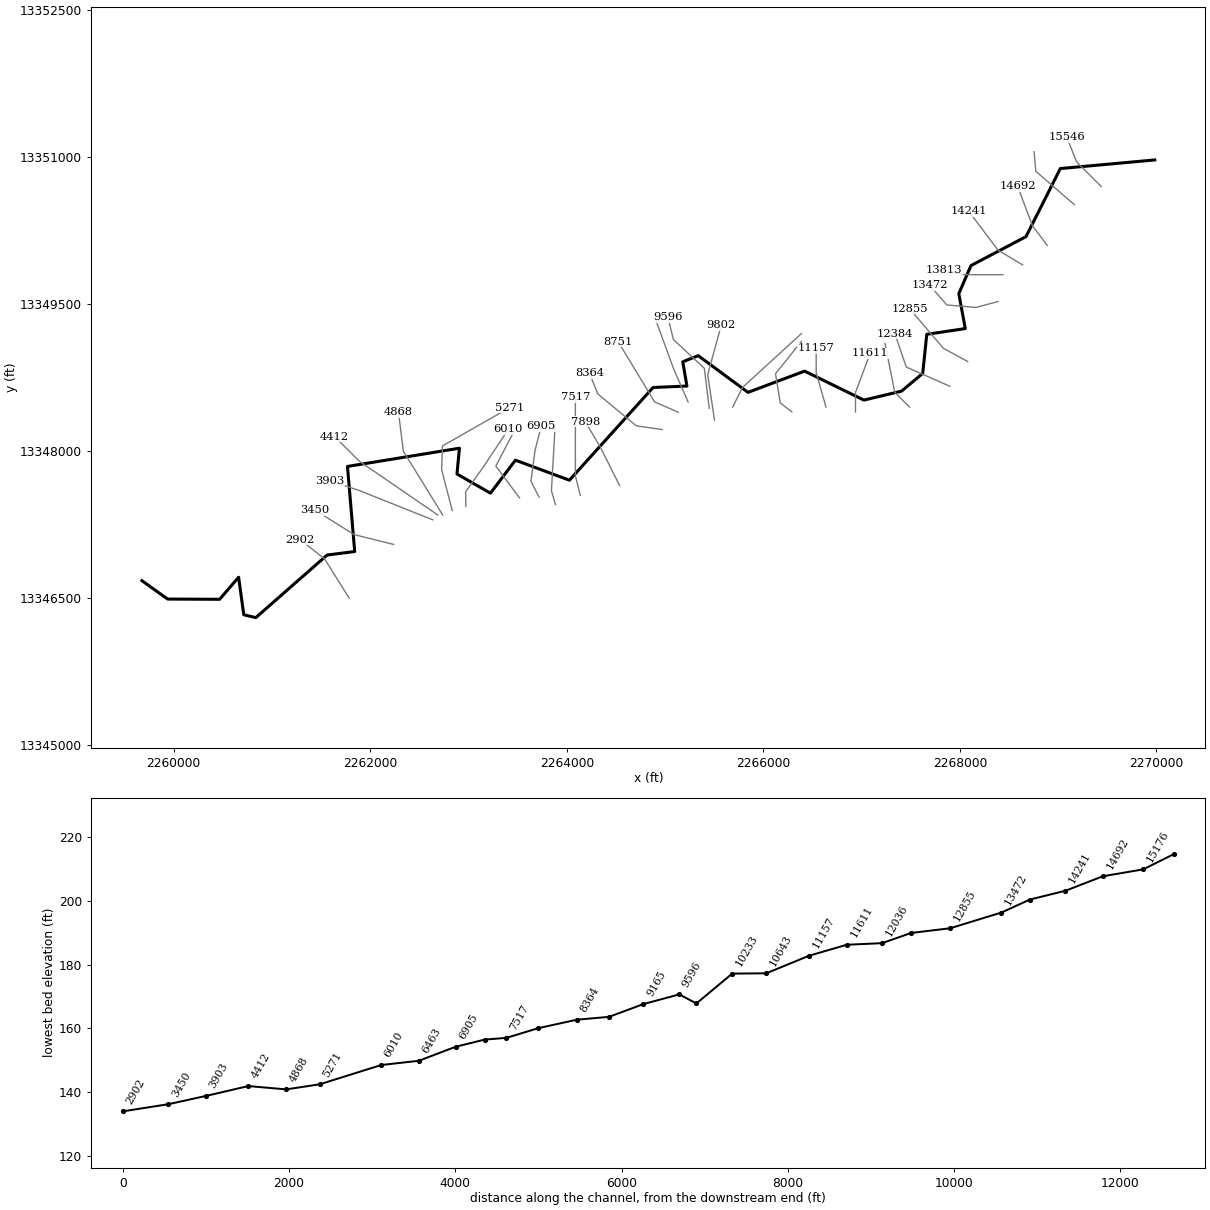
--- UNT080 IN SUCR.prj (project) ---

Proj Title=UNT080 IN SUCR Base Level Engineering
Current Plan=p01
Default Exp/Contr=0.3,0.1
English Units
Geom File=g01
Flow File=f01
Plan File=p01
Y Axis Title=Elevation
X Axis Title(PF)=Main Channel Distance
X Axis Title(XS)=Station
BEGIN DESCRIPTION:
UNT080 IN SUCR
END DESCRIPTION:
DSS Export Rating Curves= 0
DSS Export Rating Curve Sorted= 0
DSS Export Volume Flow Curves= 0
DXF OffsetX= 0
DXF OffsetY= 0
DXF ScaleX= 1
DXF ScaleY= 10

--- UNT080 IN SUCR.p01 (plan) ---

Plan Title=Multiple Run
Short Identifier=Multiple
Geom File=g01
Flow File=f01
Subcritical Flow
K Sum by GR= 0
Std Step Tol= 0.01
Critical Tol= 0.01
Num of Std Step Trials= 20
Max Error Tol= 0.3
Flow Tol Ratio= 0.001
Split Flow NTrial= 30
Split Flow Tol= 0.02
Split Flow Ratio= 0.02
Log Output Level= 0
Friction Slope Method= 1
Unsteady Friction Slope Method= 2
Unsteady Bridges Friction Slope Method= 1
Parabolic Critical Depth
Global Vel Dist=  1 , 1 , 1
Global Log Level= 0
CheckData=True
Encroach Param= -1, 0, 0, 0
BEGIN DESCRIPTION:
Multiple Run
END DESCRIPTION:

--- UNT080 IN SUCR.f01 (steady flow) ---

Flow Title=Multiple
Number of Profiles=7
Profile Names=10-year,25-year,50-year,1pct_min,100-year,1pct_plu,500-year
River Rch & RM= UNT080 IN SUCR,Reach-1,15546
     216     301     370     337     455     616     698
River Rch & RM= UNT080 IN SUCR,Reach-1,14692
     350     497     622     573     775    1048    1219
River Rch & RM= UNT080 IN SUCR,Reach-1,4868
     483     696     880     818    1106    1495    1773
River Rch & RM= UNT080 IN SUCR,Reach-1,1914
     565     819    1040     969    1310    1771    2112
Boundary for River Rch & Prof#=UNT080 IN SUCR,Reach-1,1
Up Type=0
Dn Type=3
Dn Slope=0.005
Boundary for River Rch & Prof#=UNT080 IN SUCR,Reach-1,2
Up Type=0
Dn Type=3
Dn Slope=0.005
Boundary for River Rch & Prof#=UNT080 IN SUCR,Reach-1,3
Up Type=0
Dn Type=3
Dn Slope=0.005
Boundary for River Rch & Prof#=UNT080 IN SUCR,Reach-1,4
Up Type=0
Dn Type=3
Dn Slope=0.005
Boundary for River Rch & Prof#=UNT080 IN SUCR,Reach-1,5
Up Type=0
Dn Type=3
Dn Slope=0.005
Boundary for River Rch & Prof#=UNT080 IN SUCR,Reach-1,6
Up Type=0
Dn Type=3
Dn Slope=0.005
Boundary for River Rch & Prof#=UNT080 IN SUCR,Reach-1,7
Up Type=0
Dn Type=3
Dn Slope=0.005

--- UNT080 IN SUCR.g01 (geometry) ---

Geom Title=Existing Conditions
Program Version=4.10

River Reach=UNT080 IN SUCR  ,Reach-1
Reach XY= 30
      2269982.63     13350966.97      2269021.78     13350879.01
      2268672.47     13350184.96      2268112.73     13349889.75
      2267988.61      13349603.2      2268054.84     13349247.76
      2267662.93     13349188.85      2267621.56      13348790.1
      2267406.45     13348609.91       2267023.4     13348518.24
      2266420.23      13348813.8      2265844.02     13348597.14
      2265337.77     13348971.09       2265180.4     13348908.89
      2265222.38     13348661.44      2264878.32     13348646.85
      2264026.87     13347701.56      2263477.67     13347905.74
       2263223.7     13347569.41      2262883.07     13347764.63
      2262907.94     13348027.85      2261768.91     13347841.72
      2261842.49     13346974.22      2261561.97     13346938.69
      2260836.23     13346300.25      2260713.81      13346329.6
      2260661.34      13346712.3      2260467.99     13346487.18
      2259938.97     13346489.67      2259677.72     13346676.86

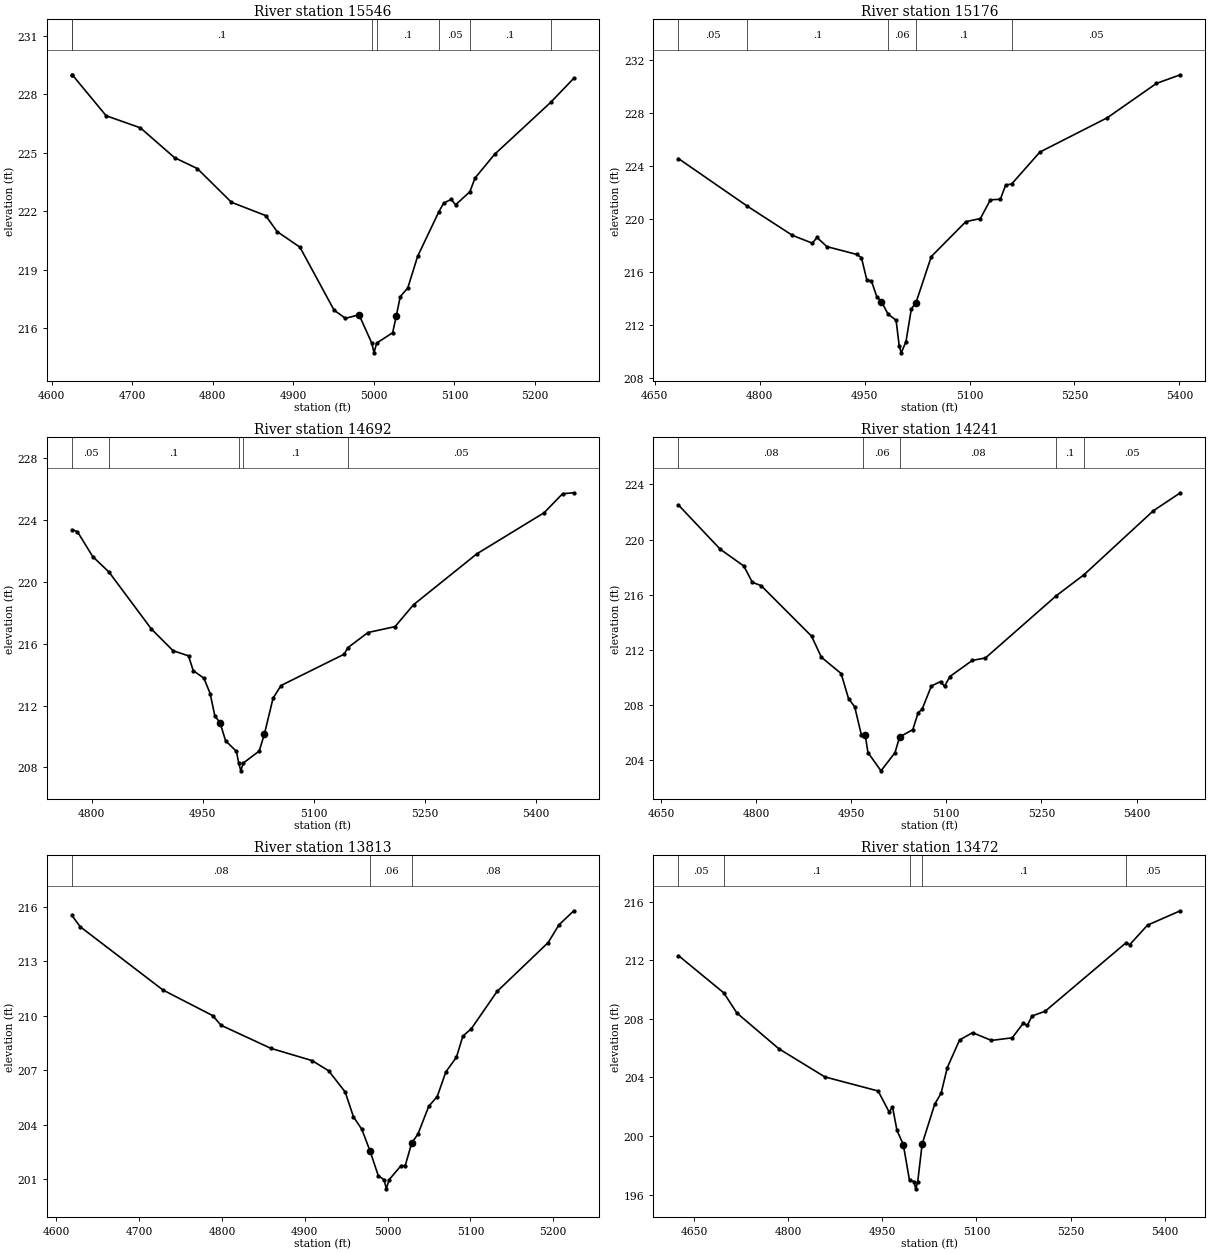
Type RM Length L Ch R = 1 ,15546   ,370,370,370
BEGIN DESCRIPTION:
UNT080 IN SUCR 33.0
END DESCRIPTION:
XS GIS Cut Line= 3
      2269437.73     13350696.85      2269187.72     13350946.85
      2269087.73     13351196.83
#Sta/Elev= 30
  4625.3  228.99  4625.7  228.99  4667.7  226.89  4710.2  226.27  4752.6  224.74
  4780.9  224.18  4823.3  222.45  4865.7  221.77  4879.9  220.95  4908.2  220.15
  4950.6  216.92  4964.7   216.5  4981.6  216.68  4997.4  215.23  5000.2  214.73
  5003.4  215.23  5023.3  215.76 5027.78  216.61  5032.7  217.61  5042.1  218.06
  5054.3  219.68  5080.7  221.97  5086.6  222.41    5096   222.6  5101.4  222.32
  5119.1  222.99  5125.6   223.7  5149.8  224.91  5219.3  227.57  5248.1  228.81
#Mann= 7 ,-1 , 0
  4625.3     .05       0  4625.7      .1       0  4997.4     .07       0
  5003.4      .1       0  5080.7     .05       0  5119.1      .1       0
  5219.3     .05       0
Bank Sta=4981.6,5027.78
XS Rating Curve= 0 ,0
Exp/Cntr=0.3,0.1

Type RM Length L Ch R = 1 ,15176   ,484,484,484
BEGIN DESCRIPTION:
UNT080 IN SUCR 32.0
END DESCRIPTION:
XS GIS Cut Line= 3
      2269162.78     13350512.57      2268772.12     13350851.14
      2268754.76     13351050.83
#Sta/Elev= 30
  4683.9  224.58  4782.1     221  4846.8  218.79  4875.3   218.2  4881.9  218.63
  4896.1  217.94  4938.9  217.35  4945.5   217.1  4953.1  215.44  4959.8  215.34
  4967.4  214.16    4974   213.8  4983.6  212.84    4995  212.39  4999.5  210.43
  5002.3  209.93  5009.1  210.77  5016.8  213.25  5023.4  213.71  5045.3  217.19
  5094.6  219.82  5115.5  220.06  5129.8  221.47    5144  221.51  5151.6  222.58
  5160.3  222.67  5200.5  225.07  5296.9  227.66  5367.2  230.25  5401.3   230.9
#Mann= 5 ,-1 , 0
  4683.9     .05       0  4782.1      .1       0  4983.6     .06       0
  5023.4      .1       0  5160.3     .05       0
Bank Sta=4974,5023.4
XS Rating Curve= 0 ,0
Exp/Cntr=0.3,0.1

Type RM Length L Ch R = 1 ,14692   ,451,451,451
BEGIN DESCRIPTION:
UNT080 IN SUCR 31.0
END DESCRIPTION:
XS GIS Cut Line= 3
      2268887.73     13350096.84      2268737.72     13350296.85
      2268587.73     13350696.83
#Sta/Elev= 30
  4773.6  223.38  4780.9  223.26  4801.7  221.64  4823.6  220.64  4880.9  216.95
  4910.1  215.55  4930.9  215.22  4937.2  214.27  4951.7  213.77  4960.1  212.78
  4966.3  211.36  4973.6  210.87  4980.9  209.73  4995.5  209.04  4998.7  208.28
  5001.5  207.78  5004.7  208.28  5026.3  209.06  5033.4  210.18    5045  212.48
  5055.7   213.3  5141.1  215.33  5145.7  215.74  5173.1  216.73  5209.6  217.11
  5234.6  218.53    5320  221.82  5410.8  224.48  5435.7  225.71  5450.8  225.77
#Mann= 5 ,-1 , 0
  4773.6     .05       0  4823.6      .1       0  4998.7     .07       0
  5004.7      .1       0  5145.7     .05       0
Bank Sta=4973.6,5033.4
XS Rating Curve= 0 ,0
Exp/Cntr=0.3,0.1

Type RM Length L Ch R = 1 ,14241   ,428,428,428
BEGIN DESCRIPTION:
UNT080 IN SUCR 30.0
END DESCRIPTION:
XS GIS Cut Line= 3
      2268637.68     13349896.88      2268387.72     13350046.85
      2268087.72     13350446.85
#Sta/Elev= 30
  4677.6   222.5  4743.6  219.29  4780.6  218.08  4794.2  216.89  4807.8  216.66
  4887.5  212.99    4903  211.46  4934.1  210.28  4945.8  208.46  4955.5  207.87
  4966.2   205.8  4969.1   205.8  4972.2   205.8  4976.4  204.55    4997  203.22
  5019.1  204.54  5026.4  205.68  5047.2  206.21  5055.6  207.44  5061.8  207.68
  5076.4  209.37    5091   209.7  5097.2  209.35  5105.6  210.06    5141  211.23
  5161.8  211.41  5273.4  215.92  5317.3  217.45  5426.4  222.08  5469.1  223.39
#Mann= 5 ,-1 , 0
  4677.6     .08       0  4969.1     .06       0  5026.4     .08       0
  5273.4      .1       0  5317.3     .05       0
Bank Sta=4972.2,5026.4
XS Rating Curve= 0 ,0
Exp/Cntr=0.3,0.1

Type RM Length L Ch R = 1 ,13813   ,341,341,341
BEGIN DESCRIPTION:
UNT080 IN SUCR 29.0
END DESCRIPTION:
XS GIS Cut Line= 3
      2268437.69     13349796.85      2268037.72     13349796.85
      2267837.75     13349846.85
#Sta/Elev= 30
  4618.7  215.53  4628.7  214.91  4728.7  211.42  4788.7  210.01  4798.7  209.48
  4858.7  208.21  4908.7  207.53  4928.7  206.97  4948.7   205.8  4958.7  204.43
  4968.7  203.75  4978.7  202.55  4988.7  201.18  4995.7  200.96  4998.4  200.46
  5001.7  200.96  5016.2  201.74  5021.2  201.74    5029  202.98  5036.7  203.49
  5049.6  205.01  5059.9  205.55  5070.2   206.9  5083.1  207.72  5090.8  208.88
  5101.1  209.29  5132.1  211.34  5193.9  214.04  5206.8  215.01  5224.8  215.79
#Mann= 3 , 0 , 0
  4618.7     .08       0  4978.7     .06       0    5029     .08       0
Bank Sta=4978.7,5029
XS Rating Curve= 0 ,0
Exp/Cntr=0.3,0.1

Type RM Length L Ch R = 1 ,13472   ,617,617,617
BEGIN DESCRIPTION:
UNT080 IN SUCR 28.0
END DESCRIPTION:
XS GIS Cut Line= 4
      2268387.67     13349523.38      2268161.95     13349462.61
      2267866.81     13349488.65      2267689.22     13349692.24
#Sta/Elev= 30
  4624.8  212.31    4697  209.77    4718  208.39  4784.9  205.95  4858.2  204.03
  4943.1  203.07  4960.9  201.62    4966     202  4973.2  200.38  4983.3  199.41
  4993.2  196.96  5000.3  196.89  5003.1  196.39  5006.3  196.89  5013.4  199.46
  5033.5  202.18  5043.5  202.91  5053.5  204.67    5073  206.55  5093.7  207.05
  5123.8  206.52    5157   206.7  5174.3  207.68    5181  207.54  5188.6  208.19
  5209.4  208.51  5338.8   213.2  5344.2  213.05  5372.7  214.39    5425  215.37
#Mann= 5 ,-1 , 0
  4624.8     .05       0    4697      .1       0  4993.2     .07       0
  5013.4      .1       0  5338.8     .05       0
Bank Sta=4983.3,5013.4
XS Rating Curve= 0 ,0
Exp/Cntr=0.3,0.1

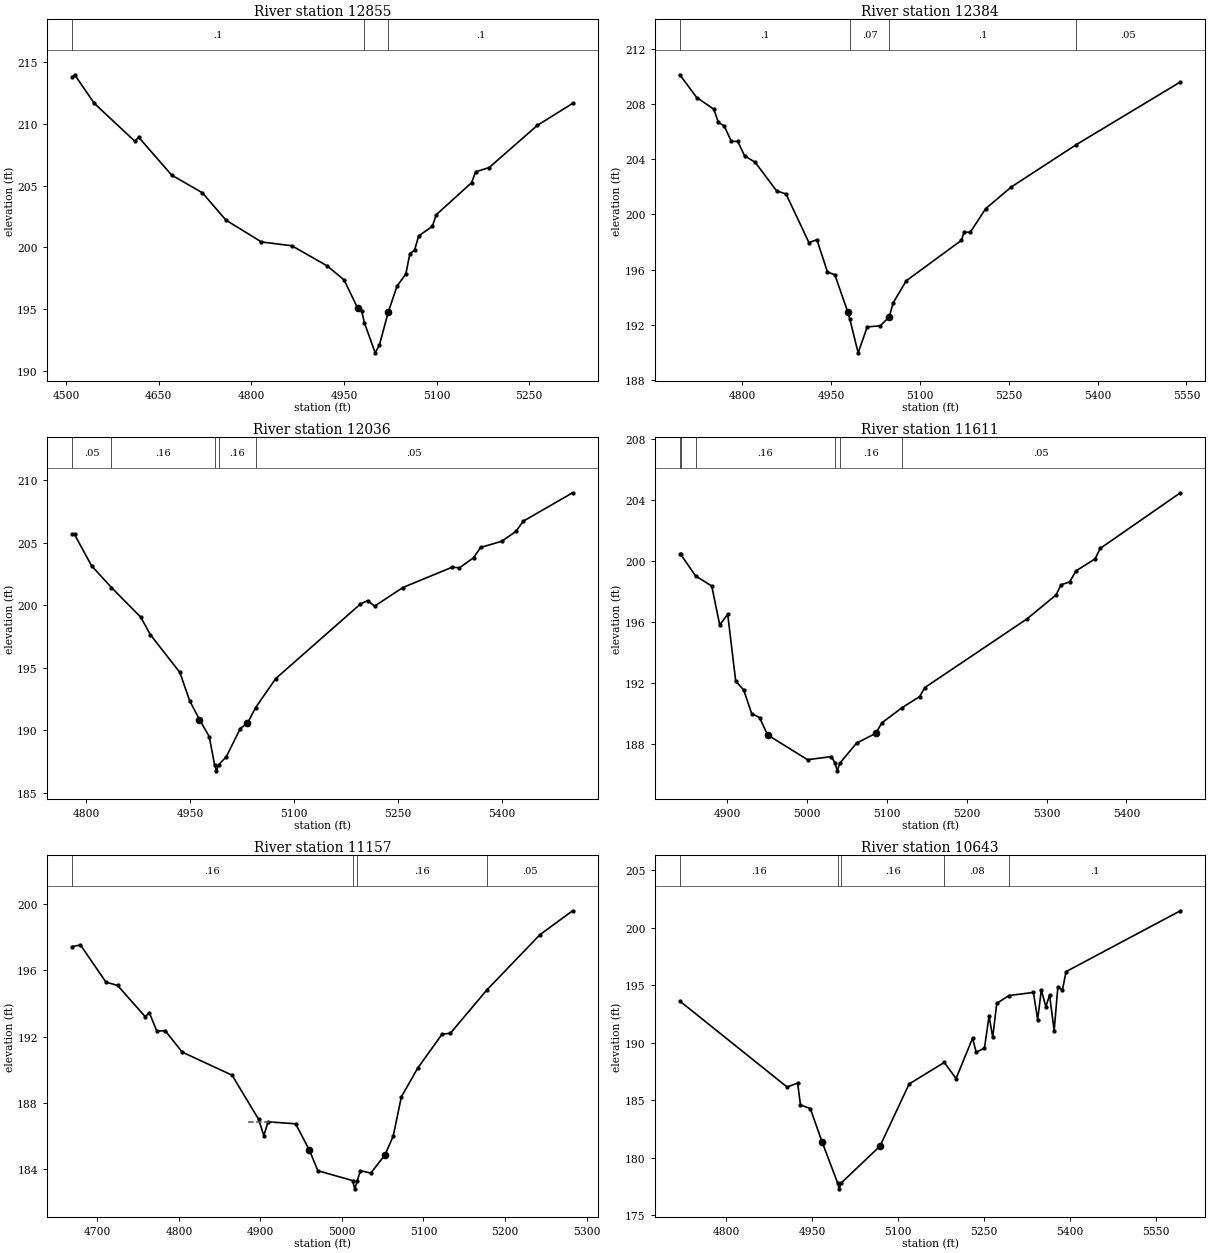
Type RM Length L Ch R = 1 ,12855   ,471,471,471
BEGIN DESCRIPTION:
UNT080 IN SUCR 27.0
END DESCRIPTION:
XS GIS Cut Line= 3
      2268079.49      13348911.4      2267832.09     13349045.95
      2267489.24     13349449.56
#Sta/Elev= 30
  4509.3  213.77  4513.6  213.97  4545.5  211.65  4611.5  208.57  4617.2  208.92
  4670.7  205.85  4720.7  204.41  4758.7   202.2  4816.3  200.43  4865.7  200.12
  4922.9  198.49  4950.3  197.35  4972.3  195.06  4978.8  194.82  4983.1  193.89
  5000.6  191.45  5007.4  192.07  5021.7  194.73    5036  196.85  5050.3  197.84
  5056.8  199.47  5064.5  199.77  5071.1  200.92  5093.1  201.69  5099.7  202.64
  5156.8  205.23  5163.4  206.11  5185.4  206.46  5263.3  209.87  5320.5  211.65
#Mann= 3 ,-1 , 0
  4509.3      .1       0  4983.1     .07       0  5021.7      .1       0
Bank Sta=4972.3,5021.7
XS Rating Curve= 0 ,0
Exp/Cntr=0.3,0.1

Type RM Length L Ch R = 1 ,12384   ,348,348,348
BEGIN DESCRIPTION:
UNT080 IN SUCR 26.0
END DESCRIPTION:
XS GIS Cut Line= 3
      2267897.19     13348659.66      2267454.49     13348854.97
      2267337.74     13349196.81
#Sta/Elev= 30
  4694.6  210.13  4723.1  208.48  4751.9  207.64  4759.6  206.68  4769.7  206.42
  4781.5   205.3  4792.4   205.3    4804  204.25  4821.8  203.79    4858  201.71
  4873.9  201.49  4912.6  197.96    4926  198.17  4943.9  195.83  4956.3  195.63
  4978.2  192.93  4981.7   192.4  4995.7  189.97    5011  191.85  5032.9  191.93
  5048.1  192.57  5054.7  193.59  5076.8  195.19  5170.1  198.13  5174.6  198.73
  5184.8   198.7  5210.9  200.42  5254.4     202  5363.8  205.06  5539.7  209.61
#Mann= 4 ,-1 , 0
  4694.6      .1       0  4981.7     .07       0  5048.1      .1       0
  5363.8     .05       0
Bank Sta=4978.2,5048.1
XS Rating Curve= 0 ,0
Exp/Cntr=0.3,0.1

Type RM Length L Ch R = 1 ,12036   ,425,425,425
BEGIN DESCRIPTION:
UNT080 IN SUCR 25.0
END DESCRIPTION:
XS GIS Cut Line= 3
      2267487.76     13348446.82      2267337.72     13348596.85
      2267237.72     13349096.87
#Sta/Elev= 30
  4779.4  205.66    4783  205.66  4807.7  203.15  4836.3  201.42  4878.4  199.06
  4892.6  197.64    4935  194.63  4949.2  192.36  4963.3  190.87  4977.4   189.5
    4985  187.27  4987.8  186.77    4991  187.27  5001.8  187.88  5022.2  190.15
  5032.4  190.58  5044.4  191.83  5073.2  194.14  5195.5   200.1  5205.7  200.37
  5215.9  199.93  5256.7  201.42  5328.1  203.05  5338.3  202.99  5358.7   203.8
  5368.9  204.62  5399.5  205.12  5419.9  205.91  5430.1  206.71  5501.5  208.99
#Mann= 5 ,-1 , 0
  4779.4     .05       0  4836.3     .16       0    4985     .07       0
    4991     .16       0  5044.4     .05       0
Bank Sta=4963.3,5032.4
XS Rating Curve= 0 ,0
Exp/Cntr=0.3,0.1

Type RM Length L Ch R = 1 ,11611   ,454,454,454
BEGIN DESCRIPTION:
UNT080 IN SUCR 24.0
END DESCRIPTION:
XS GIS Cut Line= 3
      2266937.72     13348396.82      2266937.72     13348596.85
      2267087.71     13348996.82
#Sta/Elev= 30
  4840.5  200.44  4841.5  200.44  4860.3  199.02  4880.5  198.36  4890.5  195.81
  4900.5  196.52  4910.5  192.15  4920.5  191.56  4930.5  190.02  4940.5  189.75
  4950.5  188.62  5000.5     187  5030.5   187.2    5035  186.77  5037.8  186.27
    5041  186.77  5061.9  188.08  5085.9  188.72  5093.9  189.42  5119.2  190.41
  5141.1  191.13  5147.3  191.71  5275.5  196.21    5312  197.78  5318.2  198.44
  5328.9  198.63  5336.9  199.35  5360.9  200.14  5367.2  200.82  5467.7  204.46
#Mann= 6 ,-1 , 0
  4840.5      .1       0  4841.5     .05       0  4860.3     .16       0
    5035     .07       0    5041     .16       0  5119.2     .05       0
Bank Sta=4950.5,5085.9
XS Rating Curve= 0 ,0
Exp/Cntr=0.3,0.1

Type RM Length L Ch R = 1 ,11157   ,514,514,514
BEGIN DESCRIPTION:
UNT080 IN SUCR 23.0
END DESCRIPTION:
XS GIS Cut Line= 3
      2266637.71      13348446.9      2266537.72     13348796.85
      2266537.72      13349046.9
#Sta/Elev= 30
  4668.9  197.42  4679.3  197.52  4710.5  195.28  4724.8  195.08  4758.6   193.2
  4763.8  193.43  4772.9  192.33  4783.3  192.35  4804.1  191.06  4865.2  189.67
  4897.7  187.02  4904.2  186.03  4909.4  186.86  4943.2  186.74  4960.1  185.15
  4970.5  183.91    5013  183.32  5015.7  182.82    5019  183.32  5022.5  183.92
  5035.4  183.77  5052.9  184.87  5062.9     186  5072.9  188.37  5092.9  190.09
  5122.9  192.15  5132.9  192.19  5177.6   194.8  5242.9  198.14  5282.9  199.58
#Mann= 4 ,-1 , 0
  4668.9     .16       0    5013     .07       0    5019     .16       0
  5177.6     .05       0
#XS Ineff= 1 ,-1
  4884.7 4916.98  186.84
Permanent Ineff=
       F
Bank Sta=4960.1,5052.9
XS Rating Curve= 0 ,0
Exp/Cntr=0.3,0.1

Type RM Length L Ch R = 1 ,10643   ,410,410,410
BEGIN DESCRIPTION:
UNT080 IN SUCR 22.0
END DESCRIPTION:
XS GIS Cut Line= 4
       2266290.4      13348398.4      2266172.37     13348488.65
      2266123.76     13348787.27      2266387.67     13349117.16
#Sta/Elev= 30
  4719.3  193.64  4906.6  186.16  4924.9  186.51  4929.9  184.61  4947.1  184.29
  4967.4  181.41  4994.8  177.81  4997.5  177.31  5000.8  177.81  5068.7  181.03
  5119.5  186.43  5180.8   188.3  5201.4   186.9  5230.2  190.41  5236.6  189.18
    5251  189.56    5259  192.34  5265.4  190.49  5272.4  193.44  5293.9  194.12
  5336.4  194.39  5343.8  192.03  5350.2   194.6  5358.2  193.14  5364.6  194.17
  5372.6  191.06    5379  194.83    5387   194.6  5393.4   196.2  5592.9  201.49
#Mann= 5 ,-1 , 0
  4719.3     .16       0  4994.8     .07       0  5000.8     .16       0
  5180.8     .08       0  5293.9      .1       0
Bank Sta=4967.4,5068.7
XS Rating Curve= 0 ,0
Exp/Cntr=0.3,0.1

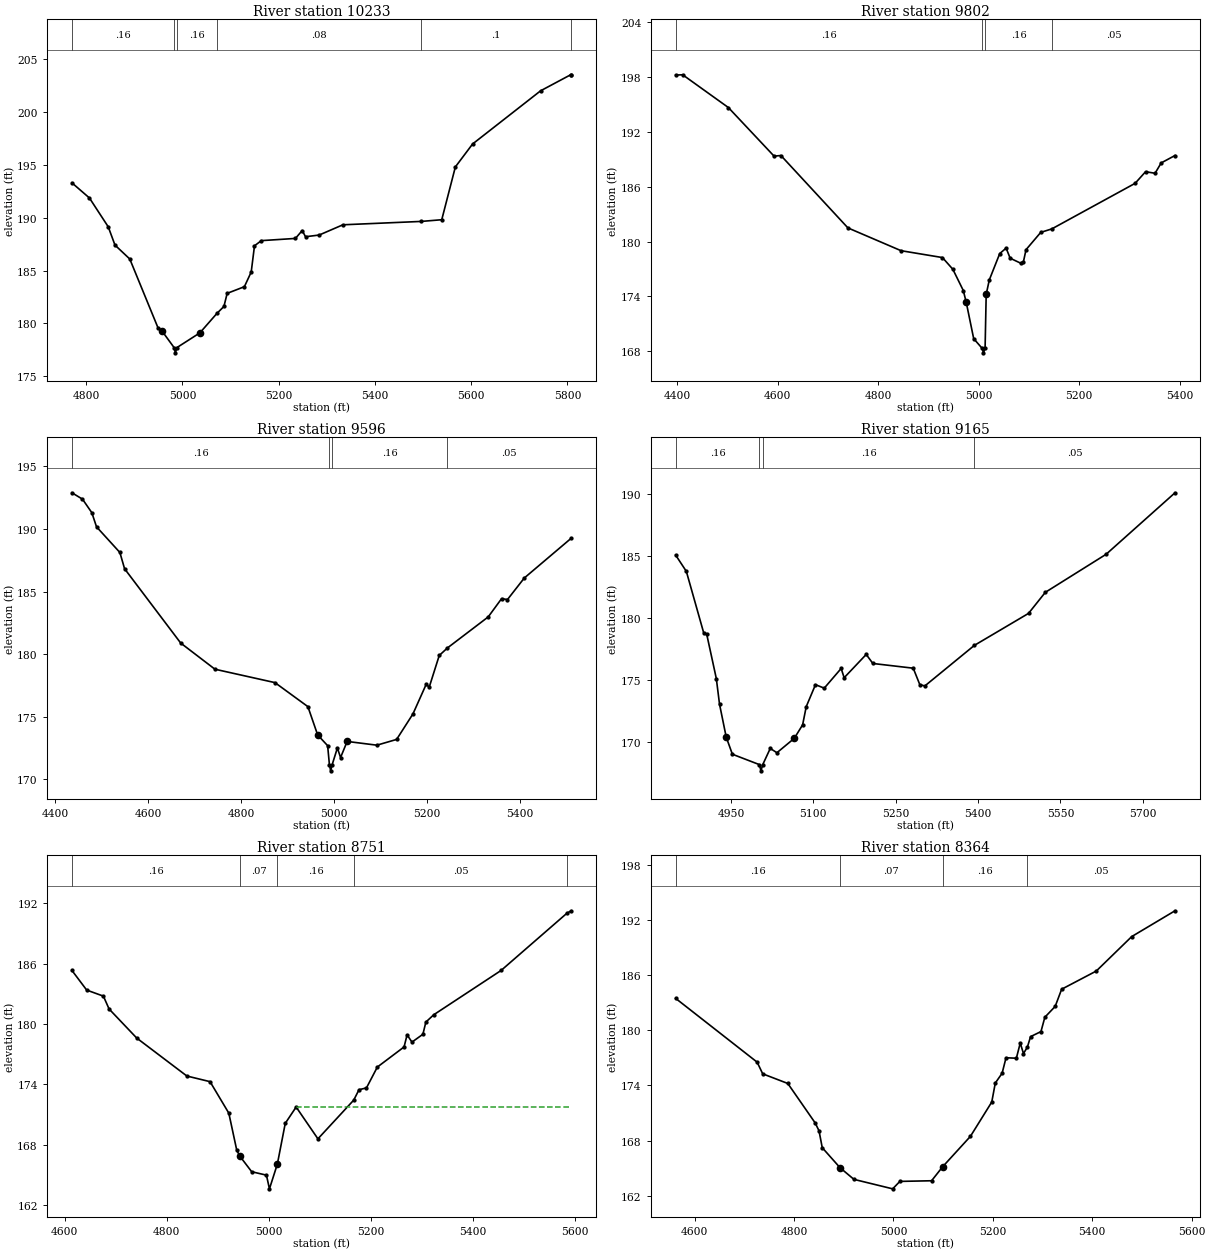
Type RM Length L Ch R = 1 ,10233   ,431,431,431
BEGIN DESCRIPTION:
UNT080 IN SUCR 21.0
END DESCRIPTION:
XS GIS Cut Line= 3
      2265687.74     13348446.89      2265787.72     13348646.85
      2266387.71     13349196.85
#Sta/Elev= 30
  4770.5   193.3  4806.8  191.87  4845.9  189.14  4859.9  187.41  4890.7  186.09
  4949.3  179.58  4957.7  179.27  4982.7  177.71  4985.4  177.21  4988.7  177.71
  5036.3   179.1  5071.9  180.95  5086.3   181.6    5093  182.84  5128.8  183.47
    5143  184.86  5149.8  187.34    5164  187.83  5234.9  188.04    5249  188.79
  5255.8   188.2  5284.2  188.36  5333.5  189.33  5496.4  189.65  5538.9  189.81
  5567.2  194.81    5603  196.98  5744.2  202.01  5806.7  203.53    5808  203.53
#Mann= 6 ,-1 , 0
  4770.5     .16       0  4982.7     .07       0  4988.7     .16       0
  5071.9     .08       0  5496.4      .1       0  5806.7     .05       0
Bank Sta=4957.7,5036.3
XS Rating Curve= 0 ,0
Exp/Cntr=0.3,0.1

Type RM Length L Ch R = 1 ,9802    ,206,206,206
BEGIN DESCRIPTION:
UNT080 IN SUCR 20.0
END DESCRIPTION:
XS GIS Cut Line= 3
      2265503.41     13348313.06      2265433.95     13348778.39
      2265572.31      13349283.4
#Sta/Elev= 30
  4396.6  198.19  4410.5  198.22  4501.5  194.64  4592.5  189.33  4606.1   189.4
  4739.5  181.49  4845.3     179  4927.7  178.25  4948.4  176.97  4969.2  174.65
  4975.1  173.35  4989.9  169.39  5006.6  168.34  5009.4  167.84  5012.6  168.34
  5014.8  174.23    5021  175.81  5041.8  178.69  5054.5  179.28  5062.5  178.18
  5083.2  177.64  5088.9  177.79  5094.1  179.11  5123.4     181  5145.4  181.38
  5311.3  186.36  5332.1  187.63    5351  187.46  5363.2  188.59  5390.7   189.4
#Mann= 4 ,-1 , 0
  4396.6     .16       0  5006.6     .07       0  5012.6     .16       0
  5145.4     .05       0
Bank Sta=4975.1,5014.8
XS Rating Curve= 0 ,0
Exp/Cntr=0.3,0.1

Type RM Length L Ch R = 1 ,9596    ,431,431,431
XS GIS Cut Line= 4
      2265449.88     13348434.37      2265399.97     13348842.33
       2265085.3      13349135.3      2265029.05      13349362.5
#Sta/Elev= 30
  4435.8   192.9  4458.5  192.39  4478.6  191.31  4488.7  190.18    4539  188.13
  4549.1  186.83    4670  180.89  4743.7   178.8  4872.9  177.73  4943.8  175.81
  4964.8  173.55  4986.3  172.69  4990.1  171.18  4992.8  170.68  4996.1  171.18
  5007.3  172.51  5014.1  171.74  5028.3  173.03  5092.3  172.73  5134.8  173.19
    5170  175.23  5198.3  177.58  5205.1  177.38  5226.6   179.9  5244.2   180.5
    5332  182.98  5360.8  184.44  5373.5  184.37  5409.7  186.09  5510.8  189.27
#Mann= 4 ,-1 , 0
  4435.8     .16       0  4990.1     .07       0  4996.1     .16       0
  5244.2     .05       0
Bank Sta=4964.8,5028.3
XS Rating Curve= 0 ,0
Exp/Cntr=0.3,0.1

Type RM Length L Ch R = 1 ,9165    ,414,414,414
BEGIN DESCRIPTION:
UNT080 IN SUCR 19.0
END DESCRIPTION:
XS GIS Cut Line= 3
      2265234.87     13348499.06      2265089.03      13348832.4
      2264902.14     13349344.62
#Sta/Elev= 30
  4849.5  185.05  4868.9  183.74  4900.5  178.78  4905.9  178.69  4923.5  175.09
  4929.3  173.03 4941.51  170.37  4952.7  168.99    5002  168.15  5004.7  167.65
    5008  168.15  5021.7  169.46  5033.8  169.11  5065.4  170.27  5080.6  171.36
  5087.2  172.83    5104   174.6    5120  174.32  5150.8  175.91  5156.2  175.16
  5196.4  177.04  5208.5  176.31    5282  175.93    5294   174.6  5303.2   174.5
  5393.3  177.77  5491.9  180.35  5522.5  182.05  5633.2  185.12  5758.6  190.08
#Mann= 4 ,-1 , 0
  4849.5     .16       0    5002     .07       0    5008     .16       0
  5393.3     .05       0
Bank Sta=4941.51,5065.4
XS Rating Curve= 0 ,0
Exp/Cntr=0.3,0.1

Type RM Length L Ch R = 1 ,8751    ,387,387,387
BEGIN DESCRIPTION:
UNT080 IN SUCR 18.0
END DESCRIPTION:
XS GIS Cut Line= 3
       2265134.2     13348394.89      2264894.59     13348499.07
       2264523.6     13349112.77
#Sta/Elev= 30
  4614.5  185.33  4643.4  183.38  4676.1  182.78  4687.3   181.5  4741.5  178.61
  4839.7  174.84  4885.1  174.28  4921.9  171.15  4937.4  167.48  4943.3  166.89
  4966.7  165.33  4995.6  164.99  5001.5  163.63    5017  166.09  5032.5  170.14
  5053.8  171.76  5096.5   168.6  5166.7  172.45    5177  173.48  5191.6  173.66
  5212.9  175.73  5265.3  177.73  5271.2  178.93  5280.8  178.21  5302.2  178.99
    5308   180.2  5323.5  180.93  5455.4  185.33  5584.7  191.03  5592.9  191.26
#Mann= 5 ,-1 , 0
  4614.5     .16       0  4943.3     .07       0    5017     .16       0
  5166.7     .05       0  5584.7      .1       0
#XS Ineff= 2 , 0
                         5054.93          171.81
Permanent Ineff=
       F       F
Bank Sta=4943.3,5017
XS Rating Curve= 0 ,0
Exp/Cntr=0.3,0.1

Type RM Length L Ch R = 1 ,8364    ,466,466,466
BEGIN DESCRIPTION:
UNT080 IN SUCR 17.0
END DESCRIPTION:
XS GIS Cut Line= 4
      2264971.01     13348217.82      2264707.09     13348256.02
      2264314.73      13348582.4      2264231.38     13348794.25
#Sta/Elev= 30
  4561.8  183.47  4725.7  176.53  4736.9  175.26  4787.4  174.21  4842.4  169.92
  4850.2  169.06  4856.7  167.22  4892.7  165.03  4920.5  163.77  4998.4  162.74
  5012.9  163.55  5076.7  163.62  5098.9  165.14  5154.8  168.45  5197.8  172.19
  5204.9  174.26  5218.6  175.32  5226.5  177.01  5247.3  176.96  5255.1  178.61
  5261.6  177.47  5269.4  178.16  5275.9  179.31  5296.8  179.86  5304.6  181.42
  5325.4   182.6  5338.4  184.47  5408.1  186.45  5479.4   190.2  5566.5  193.01
#Mann= 4 ,-1 , 0
  4561.8     .16       0  4892.7     .07       0  5098.9     .16       0
  5269.4     .05       0
Bank Sta=4892.7,5098.9
XS Rating Curve= 0 ,0
Exp/Cntr=0.3,0.1

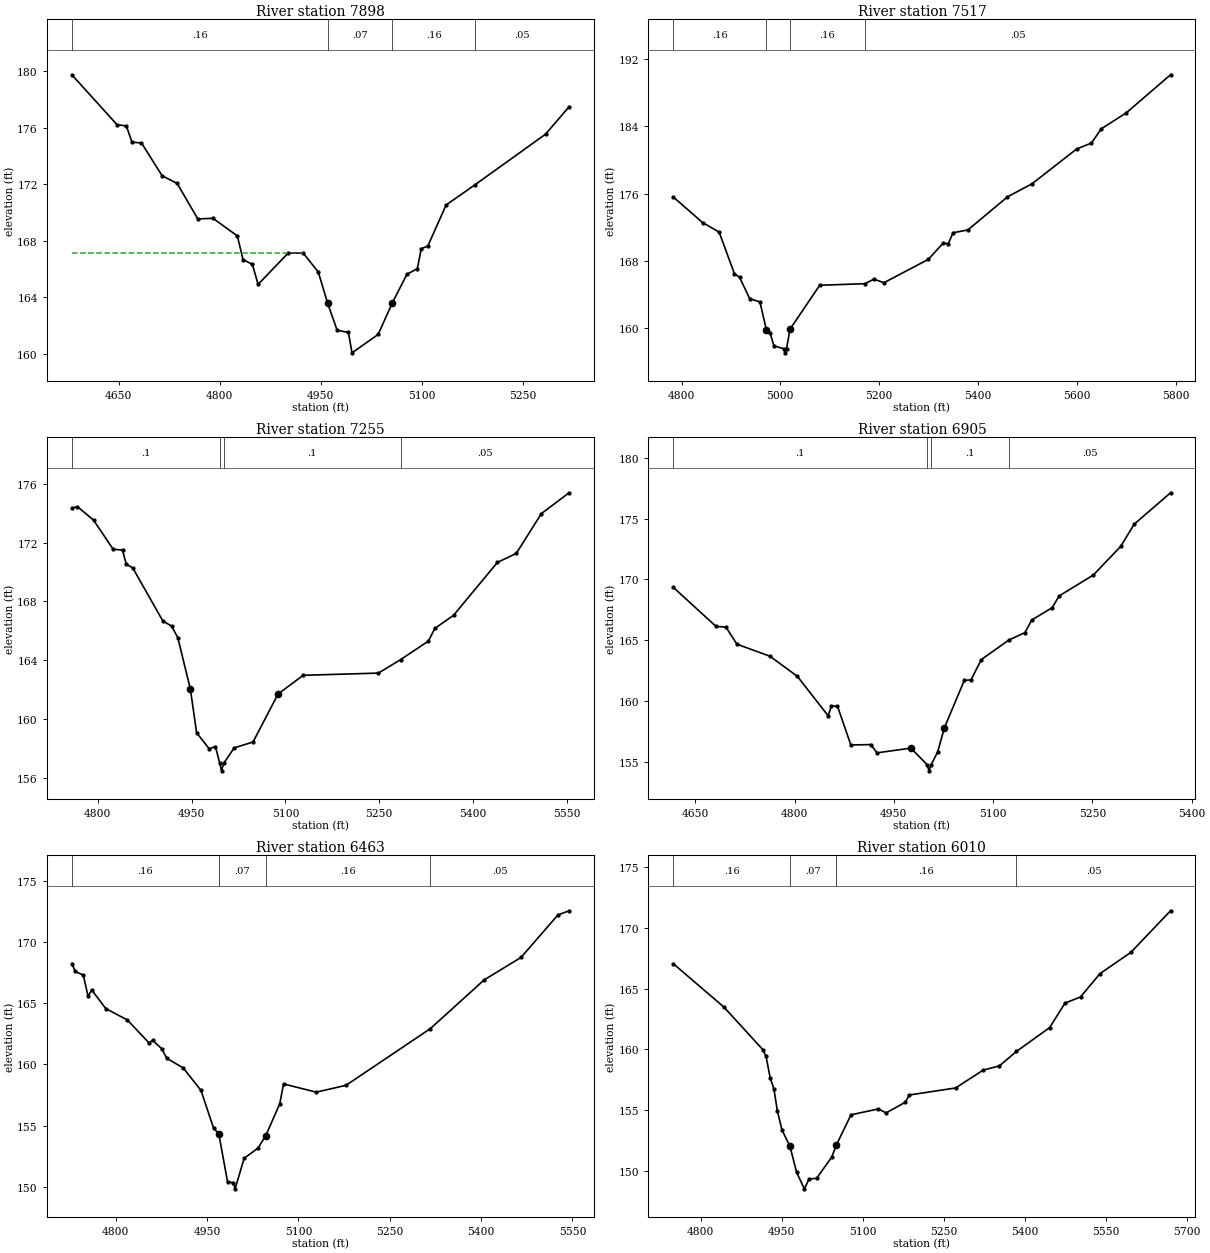
Type RM Length L Ch R = 1 ,7898    ,381,381,381
BEGIN DESCRIPTION:
UNT080 IN SUCR 16.0
END DESCRIPTION:
XS GIS Cut Line= 3
      2264537.71     13347646.87      2264337.72     13348046.85
      2264187.74     13348296.82
#Sta/Elev= 30
  4580.4  179.74  4647.5  176.21  4661.4  176.12  4669.8  174.97  4683.8  174.92
  4714.5   172.6  4736.9  172.05  4767.6  169.54    4790  169.59  4826.3  168.34
  4834.7  166.67  4848.7  166.32  4857.1  164.91  4901.8  167.13  4924.2  167.12
  4946.5  165.79  4960.5  163.57  4974.5  161.67  4991.3  161.51  4996.6  160.07
  5035.4  161.37  5056.6  163.61  5078.1  165.62  5093.7  166.03  5099.5  167.44
  5109.2  167.62  5136.4  170.53  5178.8  171.94  5284.2  175.54  5319.1  177.48
#Mann= 4 ,-1 , 0
  4580.4     .16       0  4960.5     .07       0  5056.6     .16       0
  5178.8     .05       0
#XS Ineff= 2 , 0
         4924.53  167.15
Permanent Ineff=
       F       F
Bank Sta=4960.5,5056.6
XS Rating Curve= 0 ,0
Exp/Cntr=0.3,0.1

Type RM Length L Ch R = 1 ,7517    ,262,262,262
BEGIN DESCRIPTION:
UNT080 IN SUCR 15.0
END DESCRIPTION:
XS GIS Cut Line= 3
      2264137.73     13347546.81      2264087.72     13347746.85
      2264087.72     13348546.85
#Sta/Elev= 30
  4783.4  175.58  4842.7  172.54  4876.2  171.41  4907.1  166.45  4917.4  166.04
  4938.1  163.48  4958.7   163.1  4971.6  159.81  4979.3   159.4    4987  157.87
  5006.6  157.54  5009.4  157.04  5012.6  157.54  5019.6  159.85  5079.6  165.08
    5171  165.27  5189.6  165.81  5209.6  165.38  5299.6  168.17  5329.6  170.11
  5339.6  170.01  5349.6  171.33  5379.6  171.67  5459.6   175.6  5509.6  177.17
  5599.6   181.3  5629.6  182.01  5649.6  183.71  5699.6  185.58  5789.6  190.13
#Mann= 4 ,-1 , 0
  4783.4     .16       0  4971.6     .07       0  5019.6     .16       0
    5171     .05       0
Bank Sta=4971.6,5019.6
XS Rating Curve= 0 ,0
Exp/Cntr=0.3,0.1

Type RM Length L Ch R = 1 ,7255    ,350,350,350
XS GIS Cut Line= 3
      2263885.22     13347453.42      2263843.98      13347594.5
      2263880.87     13348241.16
#Sta/Elev= 30
  4758.6  174.34  4767.5  174.44  4793.4  173.52  4824.7  171.54  4839.6  171.49
  4845.5  170.53  4855.9  170.28  4904.2  166.66    4918  166.33    4928  165.53
    4948  162.05    4958  159.08  4978.1  157.99  4988.1  158.14  4995.1  156.99
  4997.8  156.49  5001.1  156.99  5018.1  158.05  5048.2  158.45  5088.2  161.71
  5128.3  162.98  5248.5  163.13  5283.9  164.04  5328.6  165.31  5338.6  166.16
  5368.7  167.06  5438.8  170.65  5468.9  171.26  5508.9  173.96  5553.3  175.38
#Mann= 4 ,-1 , 0
  4758.6      .1       0  4995.1     .07       0  5001.1      .1       0
  5283.9     .05       0
Bank Sta=4948,5088.2
XS Rating Curve= 0 ,0
Exp/Cntr=0.3,0.1

Type RM Length L Ch R = 1 ,6905    ,442,442,442
XS GIS Cut Line= 4
      2263718.12     13347529.38      2263635.65     13347689.99
      2263676.88     13348004.66      2263739.82      13348249.9
#Sta/Elev= 30
  4616.9  169.34  4681.5  166.12  4696.4  166.07    4713  164.66  4762.9  163.67
  4804.4  162.01  4850.8  158.77  4855.8  159.58  4864.9  159.56  4885.1  156.37
  4915.3   156.4  4924.6  155.72  4975.8  156.11  5000.4  154.74  5003.2  154.24
  5006.4  154.74  5016.2  155.79  5026.3  157.77  5056.5  161.69  5066.6  161.72
  5082.2   163.4    5124  165.01    5148  165.61  5158.4  166.65  5189.3  167.67
  5199.7  168.63  5251.3  170.35  5292.6   172.7  5313.2  174.54    5368  177.12
#Mann= 4 ,-1 , 0
  4616.9      .1       0  5000.4     .07       0  5006.4      .1       0
    5124     .05       0
Bank Sta=4975.8,5026.3
XS Rating Curve= 0 ,0
Exp/Cntr=0.3,0.1

Type RM Length L Ch R = 1 ,6463    ,453,453,453
BEGIN DESCRIPTION:
UNT080 IN SUCR 13.0
END DESCRIPTION:
XS GIS Cut Line= 3
      2263519.29     13347521.66      2263278.26      13347845.8
      2263469.43     13348211.52
#Sta/Elev= 30
  4727.8  168.25  4733.4   167.6  4746.7   167.3  4754.3  165.59  4760.5  166.09
  4783.5  164.57  4818.9  163.64  4854.4  161.77  4860.6  161.97  4875.2   161.3
  4883.6  160.51  4910.7  159.72  4939.9  157.88  4960.7  154.78  4969.1  154.35
  4983.5  150.41  4993.2  150.34  4995.9  149.84  5010.8  152.34  5033.4  153.16
  5046.3  154.19  5069.2  156.78  5075.5  158.41  5129.3  157.74  5178.1   158.3
  5316.3  162.92  5404.9  166.91  5465.5  168.75  5526.1  172.22  5544.4  172.56
#Mann= 4 ,-1 , 0
  4727.8     .16       0  4969.1     .07       0  5046.3     .16       0
  5316.3     .05       0
Bank Sta=4969.1,5046.3
XS Rating Curve= 0 ,0
Exp/Cntr=0.3,0.1

Type RM Length L Ch R = 1 ,6010    ,739,739,739
BEGIN DESCRIPTION:
UNT080 IN SUCR 12.0
END DESCRIPTION:
XS GIS Cut Line= 4
      2262973.51     13347433.01      2262970.74      13347582.6
      2263148.05     13347831.95      2263405.69     13348219.79
#Sta/Elev= 30
  4749.2  167.06  4843.1  163.48  4914.8  159.99    4921  159.43  4928.6  157.67
  4935.7  156.72  4941.9  154.95  4950.5  153.36  4965.3  152.02  4977.7  149.86
    4992  148.51  5000.9  149.33  5014.5  149.37  5042.7  151.12  5051.3  152.12
  5078.4  154.61  5128.8  155.09  5143.6  154.77  5179.2  155.65  5186.3  156.24
  5272.1  156.82  5323.2  158.29  5353.3  158.64  5384.9  159.83  5446.5   161.8
  5474.8  163.81  5503.6  164.32  5539.7  166.24  5596.8  167.99  5670.4  171.42
#Mann= 4 ,-1 , 0
  4749.2     .16       0  4965.3     .07       0  5051.3     .16       0
  5384.9     .05       0
Bank Sta=4965.3,5051.3
XS Rating Curve= 0 ,0
Exp/Cntr=0.3,0.1

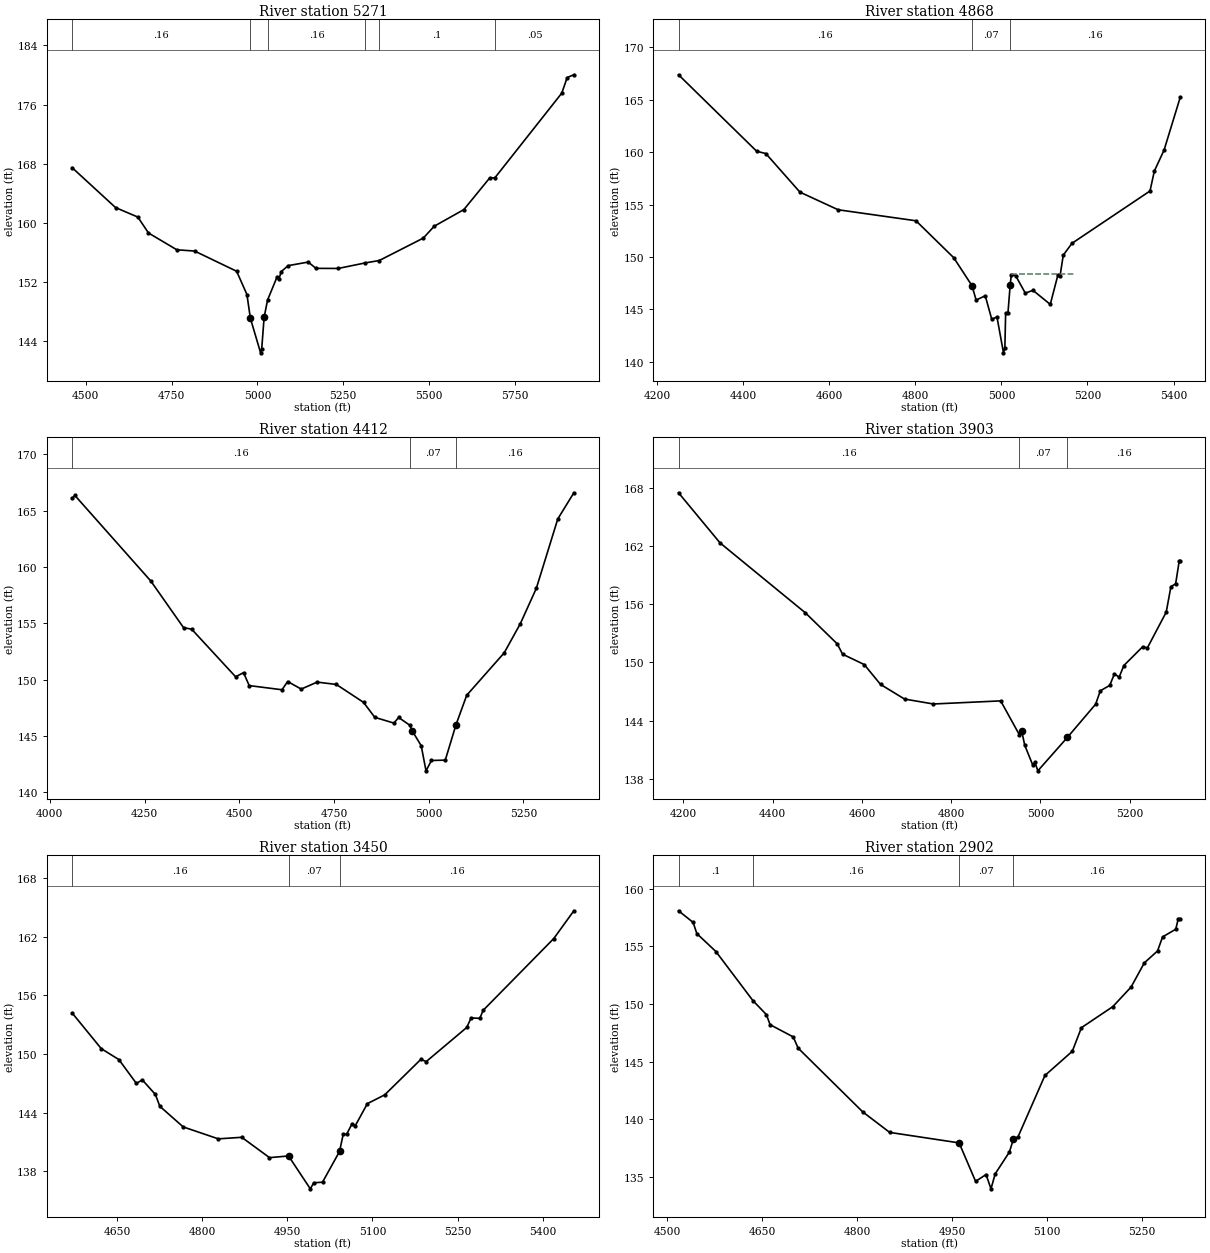
Type RM Length L Ch R = 1 ,5271    ,403,403,403
BEGIN DESCRIPTION:
UNT080 IN SUCR 11.0
END DESCRIPTION:
XS GIS Cut Line= 4
      2262834.98     13347391.44      2262726.93     13347809.78
      2262735.24     13348050.82      2263419.54     13348441.45
#Sta/Elev= 30
  4460.3  167.48    4587  162.08  4651.8   160.8  4682.8  158.65  4765.4  156.38
  4817.1  156.21  4939.5  153.48  4969.5  150.34  4979.5  147.14  5009.3  142.46
  5012.5  142.96  5019.5  147.24  5029.5  149.59  5057.5  152.74  5062.5  152.42
  5069.6  153.44  5089.6  154.24  5147.9  154.72  5170.6  153.87  5235.4  153.86
  5314.3  154.61  5354.8  154.93  5483.1  157.96  5514.8  159.56  5601.2  161.81
    5676  166.06  5691.8  166.12  5886.3  177.54  5902.1  179.65  5921.5  180.02
#Mann= 6 ,-1 , 0
  4460.3     .16       0  4979.5     .07       0  5029.5     .16       0
  5314.3     .05       0  5354.8      .1       0  5691.8     .05       0
Bank Sta=4979.5,5019.5
XS Rating Curve= 0 ,0
Exp/Cntr=0.3,0.1

Type RM Length L Ch R = 1 ,4868    ,456,456,456
BEGIN DESCRIPTION:
UNT080 IN SUCR 10.0
END DESCRIPTION:
XS GIS Cut Line= 3
      2262737.72     13347346.85      2262337.72     13347996.85
      2262287.72     13348396.82
#Sta/Elev= 30
  4249.5  167.37  4431.1  160.08  4452.4  159.86  4531.7  156.18  4620.5   154.5
  4801.4  153.45  4889.1  149.93  4931.6  147.26  4941.2  145.89  4962.4   146.3
  4977.5  144.06  4989.6  144.28  5004.8  140.86    5008  141.36  5009.8  144.68
  5015.2  144.68 5020.34  147.33  5022.8  148.26  5032.9  148.23  5055.5  146.55
  5073.2  146.82  5113.5  145.48  5131.1  148.26  5136.2  148.18  5143.7  150.17
  5163.9   151.3  5345.3  156.29  5355.4  158.19    5378  160.19  5415.8  165.25
#Mann= 3 , 0 , 0
  4249.5     .16       0  4931.6     .07       0 5020.34     .16       0
#XS Ineff= 1 ,-1
 5024.74 5170.02  148.35
Permanent Ineff=
       F
Bank Sta=4931.6,5020.34
XS Rating Curve= 0 ,0
Exp/Cntr=0.3,0.1

Type RM Length L Ch R = 1 ,4412    ,509,509,509
BEGIN DESCRIPTION:
UNT080 IN SUCR 9.0
END DESCRIPTION:
XS GIS Cut Line= 3
      2262687.75     13347346.83      2261887.72     13347896.85
      2261637.73     13348146.84
#Sta/Elev= 30
  4058.6   166.1  4066.1  166.35  4266.3  158.76  4352.9  154.61  4374.2  154.48
  4490.3  150.25  4511.2  150.62  4526.1  149.47  4612.7   149.1  4627.6  149.83
  4663.5  149.16  4705.4  149.78  4756.1  149.57  4827.9  147.98  4857.6  146.65
  4908.1  146.14  4920.5  146.64  4950.3  145.94  4956.7  145.43  4980.1  144.13
  4992.8   141.9  5007.1  142.82  5043.6  142.85  5071.9  145.99  5100.2  148.61
  5199.2  152.38  5241.6  154.96    5284  158.11  5340.6  164.27    5383  166.59
#Mann= 3 ,-1 , 0
  4058.6     .16       0  4950.3     .07       0  5071.9     .16       0
Bank Sta=4956.7,5071.9
XS Rating Curve= 0 ,0
Exp/Cntr=0.3,0.1

Type RM Length L Ch R = 1 ,3903    ,453,453,453
BEGIN DESCRIPTION:
UNT080 IN SUCR 8.0
END DESCRIPTION:
XS GIS Cut Line= 3
      2262637.73     13347296.85      2261887.72     13347596.85
      2261587.73     13347696.85
#Sta/Elev= 30
  4189.3  167.51  4282.2  162.34  4473.4  155.12  4544.7  151.92  4556.8  150.85
  4605.3  149.78  4641.7  147.73  4695.5  146.22  4760.1  145.71  4910.9  146.03
  4952.7  142.54    4958   142.9  4964.8  141.45  4982.3  139.46  4987.7  139.69
  4994.1  138.81  5060.3  142.26  5123.6  145.69  5134.1  147.07  5155.2  147.63
  5165.7  148.82  5176.3  148.48  5186.8  149.68    5229  151.62  5239.5   151.5
  5281.7  155.19  5292.2  157.82  5302.8  158.12  5310.7  160.43  5313.3  160.43
#Mann= 3 ,-1 , 0
  4189.3     .16       0  4952.7     .07       0  5060.3     .16       0
Bank Sta=4958,5060.3
XS Rating Curve= 0 ,0
Exp/Cntr=0.3,0.1

Type RM Length L Ch R = 1 ,3450    ,548,548,548
BEGIN DESCRIPTION:
UNT080 IN SUCR 7.0
END DESCRIPTION:
XS GIS Cut Line= 3
      2262237.68     13347046.86      2261837.72     13347146.85
       2261437.7     13347396.87
#Sta/Elev= 30
  4570.9   154.2  4622.4  150.54  4653.3  149.43  4684.2  146.99  4694.6  147.35
  4717.7  145.86  4725.5  144.65  4766.7  142.54  4828.6  141.32  4869.8  141.48
  4918.7   139.4  4952.3  139.57  4990.6  136.21  4996.7  136.83  5012.1  136.89
  5042.1  140.03  5048.6   141.8  5054.5  141.78    5064  142.85  5069.8  142.66
  5091.1  144.92  5121.7  145.82  5185.4  149.45  5194.8  149.22  5266.2  152.71
  5273.9  153.69  5289.2  153.64  5295.1  154.46  5419.5   161.8  5454.9  164.64
#Mann= 3 , 0 , 0
  4570.9     .16       0  4952.3     .07       0  5042.1     .16       0
Bank Sta=4952.3,5042.1
XS Rating Curve= 0 ,0
Exp/Cntr=0.3,0.1

Type RM Length L Ch R = 1 ,2902    ,356,356,356
BEGIN DESCRIPTION:
UNT080 IN SUCR 6.0
END DESCRIPTION:
XS GIS Cut Line= 3
      2261787.73     13346496.83      2261537.72     13346896.85
       2261287.7     13347096.87
#Sta/Elev= 30
  4518.3   158.1  4541.3  157.09  4547.2  156.12  4577.3  154.56  4635.7   150.3
  4656.9  149.09  4662.8  148.21  4699.3  147.15    4707  146.18    4809  140.64
  4851.5  138.86  4961.1  137.95  4987.1  134.61  5003.6   135.2  5011.4  133.96
    5018  135.26  5040.4  137.15  5046.9  138.29  5054.1  138.48  5096.5   143.8
  5139.7   145.9  5154.1  147.95  5203.7  149.78  5232.5  151.48  5253.4  153.58
  5274.2  154.61  5282.2  155.83    5303   156.5    5307  157.42  5310.2  157.42
#Mann= 4 ,-1 , 0
  4518.3      .1       0  4635.7     .16       0  4961.1     .07       0
  5046.9     .16       0
Bank Sta=4961.1,5046.9
XS Rating Curve= 0 ,0
Exp/Cntr=0.3,0.1