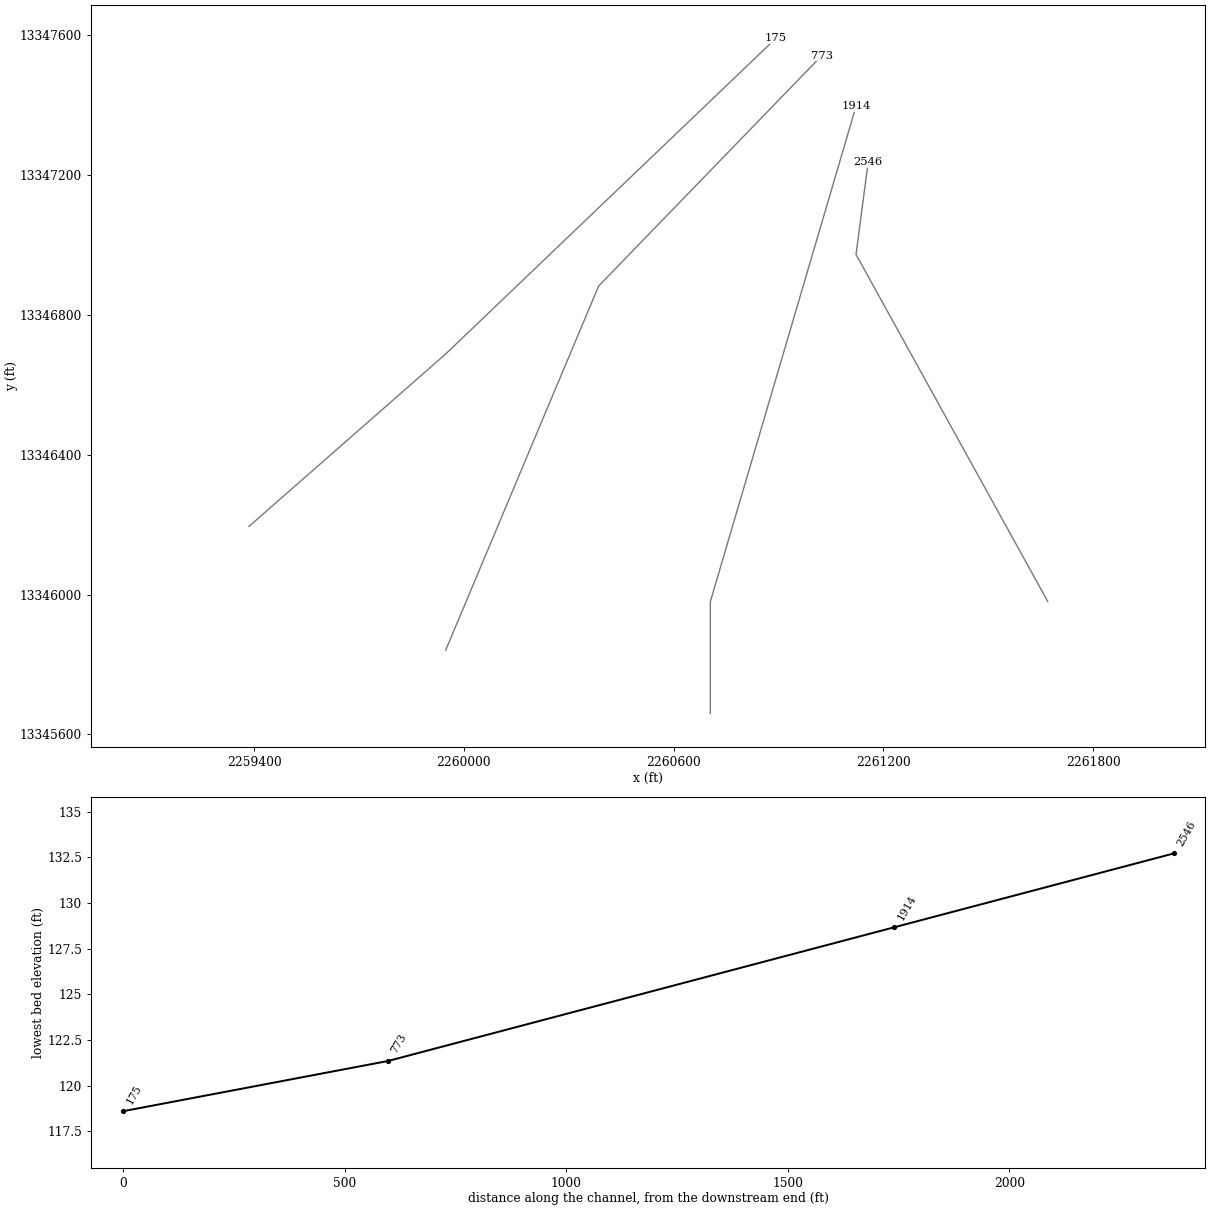
HEC-RAS study UNT080 IN SUCR.prj: UNT080 IN SUCR Base Level Engineering

--- UNT080 IN SUCR.g01 (geometry) --- (continued)

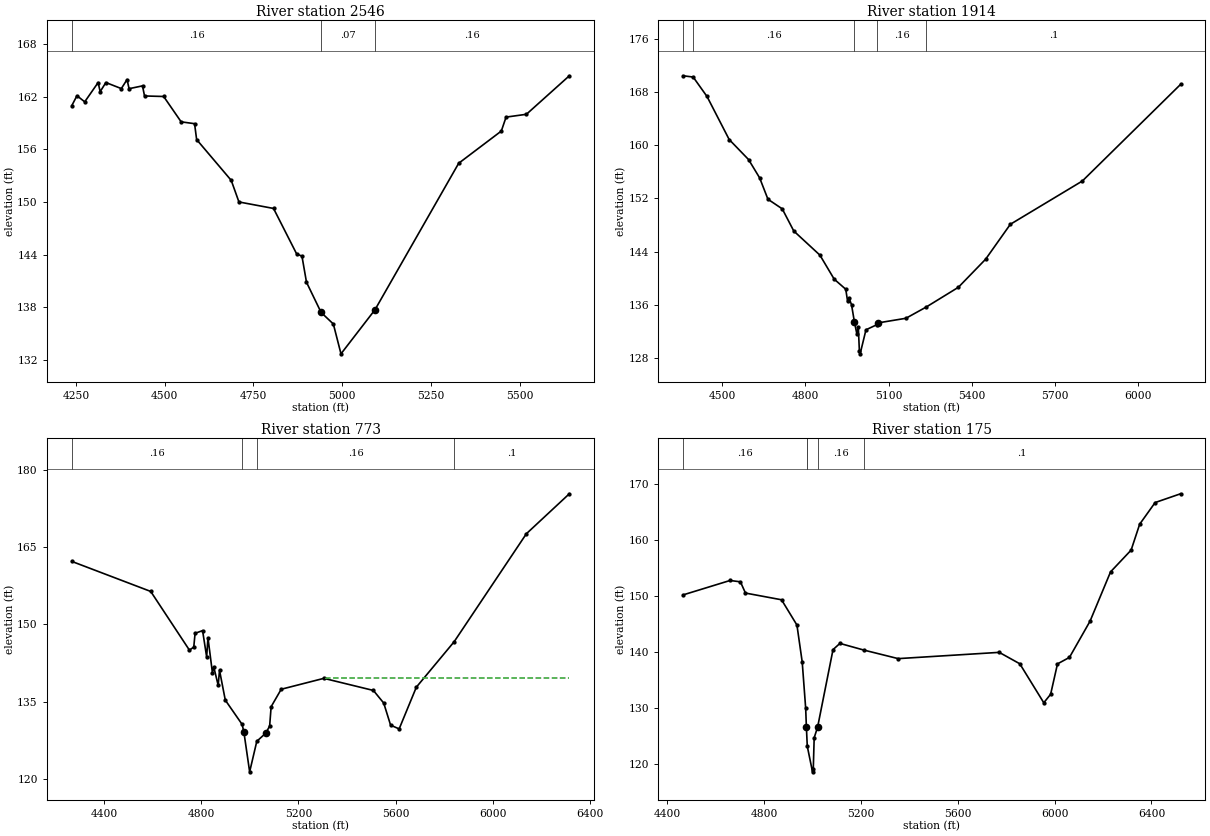
Type RM Length L Ch R = 1 ,2546    ,632,632,632
BEGIN DESCRIPTION:
UNT080 IN SUCR 5.0
END DESCRIPTION:
XS GIS Cut Line= 3
      2261670.04     13345979.82      2261121.45     13346972.83
      2261156.17     13347236.68
#Sta/Elev= 30
  4238.7  161.01  4253.1  162.13  4274.9  161.43  4312.7  163.63  4318.4  162.59
  4334.5  163.63    4378  162.94  4394.1  163.97  4399.8  162.93  4437.6  163.25
  4443.3   162.1  4497.2  162.04  4546.4  159.15  4584.2  158.94    4590  157.13
  4687.4  152.48  4709.1  150.02  4806.5  149.28  4871.8  144.08  4886.5  143.85
  4899.3  140.87  4940.4  137.43  4974.9  136.11  4996.4  132.71  5092.2  137.74
  5327.8  154.43  5447.8   158.1  5461.2  159.69  5518.4  160.01  5639.3   164.4
#Mann= 3 , 0 , 0
  4238.7     .16       0  4940.4     .07       0  5092.2     .16       0
Bank Sta=4940.4,5092.2
XS Rating Curve= 0 ,0
Exp/Cntr=0.3,0.1

Type RM Length L Ch R = 1 ,1914    ,1141,1141,1141
BEGIN DESCRIPTION:
UNT080 IN SUCR 4.0
END DESCRIPTION:
XS GIS Cut Line= 3
      2260704.79     13345660.32      2260704.79     13345979.78
      2261121.45     13347396.42
#Sta/Elev= 30
  4358.1  170.41  4394.6  170.22  4444.6   167.3  4524.6  160.84  4594.6  157.83
  4634.6  155.08  4664.6  151.87  4716.2  150.43  4757.9   147.1  4852.2  143.48
  4903.8  139.87  4945.5  138.36  4952.2  136.53  4957.5  137.03  4966.4  136.02
  4976.8  133.44  4985.6  131.65  4990.8  132.72  4994.6  129.16  4997.4  128.66
  5018.5  132.27  5057.5  133.03  5062.7  133.31  5162.8     134  5236.1  135.69
    5352  138.65  5450.5  142.87  5539.7  148.11  5799.7  154.61  6154.2  169.11
#Mann= 5 ,-1 , 0
  4358.1      .1       0  4394.6     .16       0  4976.8     .07       0
  5057.5     .16       0  5236.1      .1       0
Bank Sta=4976.8,5062.7
XS Rating Curve= 0 ,0
Exp/Cntr=0.3,0.1

Type RM Length L Ch R = 1 ,773     ,598,598,598
BEGIN DESCRIPTION:
UNT080 IN SUCR 2.0
END DESCRIPTION:
XS GIS Cut Line= 3
      2259947.84     13345840.89      2260385.34     13346882.55
      2261023.27     13347541.28
#Sta/Elev= 30
  4268.2  162.22  4592.7  156.39  4751.9  144.99  4769.8  145.58  4775.2  148.26
  4806.1  148.78  4822.8  143.67  4828.2   147.4  4846.5  140.61  4851.9  141.74
  4870.3  138.15  4875.7  141.08  4899.5  135.28  4968.8  130.56  4976.2  129.02
  4999.7  121.35  5029.1  127.28  5066.4  128.88    5082  130.25  5088.1     134
  5129.5  137.39  5305.1  139.51  5508.8  137.16  5551.3  134.71  5579.6  130.42
  5614.8  129.69  5685.6   137.8  5841.2  146.63  6138.3   167.6    6315  175.36
#Mann= 4 ,-1 , 0
  4268.2     .16       0  4968.8     .07       0  5029.1     .16       0
  5841.2      .1       0
#XS Ineff= 2 , 0
                         5312.89           139.6
Permanent Ineff=
       F       F
Bank Sta=4976.2,5066.4
XS Rating Curve= 0 ,0
Exp/Cntr=0.3,0.1

Type RM Length L Ch R = 1 ,175     ,0,0,0
BEGIN DESCRIPTION:
UNT080 IN SUCR 1.0
END DESCRIPTION:
XS GIS Cut Line= 3
      2259385.36     13346195.07      2259947.84     13346688.11
      2260892.29     13347590.89
#Sta/Elev= 30
  4465.6  150.23  4659.7  152.81  4702.5  152.57  4723.3  150.56  4872.3  149.36
  4935.9  144.84  4957.7  138.23    4972  129.95 4974.84   126.7  4978.6  123.18
  5000.2   118.6  5003.4   119.1  5007.1  124.69  5021.3   126.6  5084.9  140.45
  5113.4  141.56  5212.1  140.37    5354  138.84  5771.3  139.96  5856.2  137.92
  5955.3  130.95  5983.6  132.47  6011.9   137.9  6061.3  139.06  6146.2  145.52
  6231.1  154.35    6316  158.24  6351.3  162.87  6415.1  166.74  6520.1  168.31
#Mann= 5 ,-1 , 0
  4465.6     .16       0  4978.6     .05       0  4978.6     .07       0
  5021.3     .16       0  5212.1      .1       0
#XS Ineff= 2 , 0
                         5116.35          141.35
Permanent Ineff=
       F       F
Bank Sta=4974.84,5021.3
XS Rating Curve= 0 ,0
Exp/Cntr=0.3,0.1

Chan Stop Cuts=-1
Use User Specified Reach Order=0
Composite Channel Slope=5