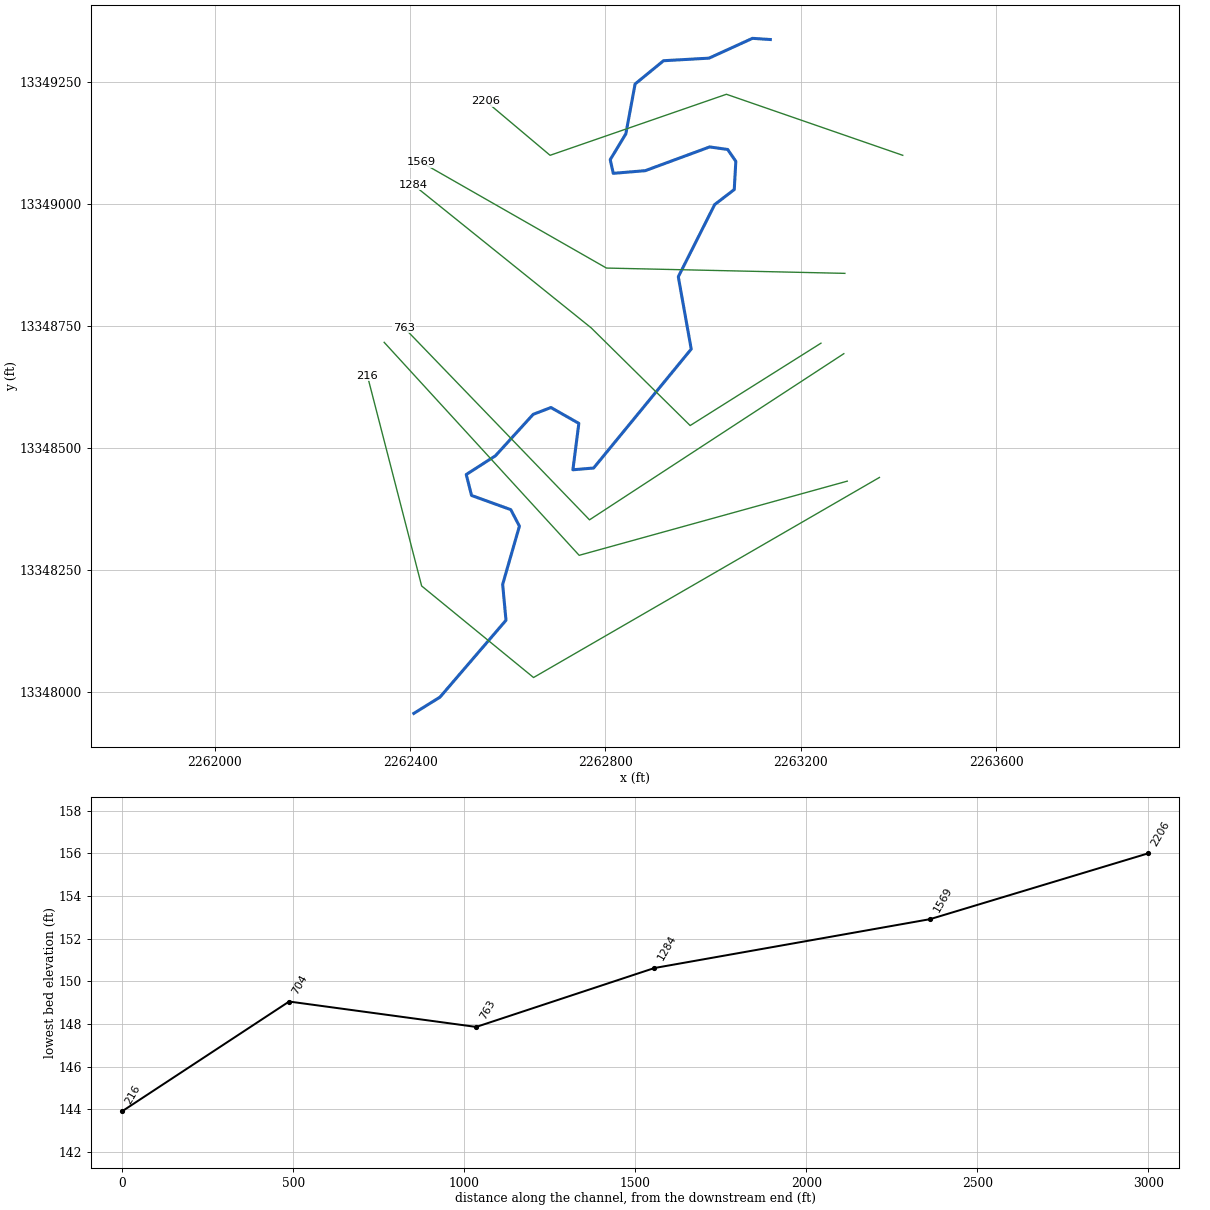
--- UNT081 IN SUCR.prj (project) ---

Proj Title=UNT081 IN SUCR Base Level Engineering
Current Plan=p01
Default Exp/Contr=0.3,0.1
English Units
Geom File=g01
Flow File=f01
Plan File=p01
Y Axis Title=Elevation
X Axis Title(PF)=Main Channel Distance
X Axis Title(XS)=Station
BEGIN DESCRIPTION:
UNT081 IN SUCR
END DESCRIPTION:
DSS Export Rating Curves= 0
DSS Export Rating Curve Sorted= 0
DSS Export Volume Flow Curves= 0
DXF OffsetX= 0
DXF OffsetY= 0
DXF ScaleX= 1
DXF ScaleY= 10

--- UNT081 IN SUCR.p01 (plan) ---

Plan Title=Multiple Run
Short Identifier=Multiple
Geom File=g01
Flow File=f01
Subcritical Flow
K Sum by GR= 0
Std Step Tol= 0.01
Critical Tol= 0.01
Num of Std Step Trials= 20
Max Error Tol= 0.3
Flow Tol Ratio= 0.001
Split Flow NTrial= 30
Split Flow Tol= 0.02
Split Flow Ratio= 0.02
Log Output Level= 0
Friction Slope Method= 1
Unsteady Friction Slope Method= 2
Unsteady Bridges Friction Slope Method= 1
Parabolic Critical Depth
Global Vel Dist=  1 , 1 , 1
Global Log Level= 0
CheckData=True
Encroach Param= -1, 0, 0, 0
BEGIN DESCRIPTION:
Multiple Run
END DESCRIPTION:

--- UNT081 IN SUCR.f01 (steady flow) ---

Flow Title=Multiple
Program Version=4.10
Number of Profiles= 7
Profile Names=10-year,25-year,50-year,1pct_min,100-year,1pct_plu,500-year
River Rch & RM=UNT081 IN SUCR,Reach-1         ,2206
     204     281     345     312     422     570     640
Boundary for River Rch & Prof#=UNT081 IN SUCR,Reach-1         , 1
Up Type= 0
Dn Type= 3
Dn Slope=0.0074
Boundary for River Rch & Prof#=UNT081 IN SUCR,Reach-1         , 2
Up Type= 0
Dn Type= 3
Dn Slope=0.0074
Boundary for River Rch & Prof#=UNT081 IN SUCR,Reach-1         , 3
Up Type= 0
Dn Type= 3
Dn Slope=0.0074
Boundary for River Rch & Prof#=UNT081 IN SUCR,Reach-1         , 4
Up Type= 0
Dn Type= 3
Dn Slope=0.0074
Boundary for River Rch & Prof#=UNT081 IN SUCR,Reach-1         , 5
Up Type= 0
Dn Type= 3
Dn Slope=0.0074
Boundary for River Rch & Prof#=UNT081 IN SUCR,Reach-1         , 6
Up Type= 0
Dn Type= 3
Dn Slope=0.0074
Boundary for River Rch & Prof#=UNT081 IN SUCR,Reach-1         , 7
Up Type= 0
Dn Type= 3
Dn Slope=0.0074
DSS Import GetInterval= 0
DSS Import GetPeak= 0
DSS Import FillOption= 0

--- UNT081 IN SUCR.g01 (geometry) ---

Geom Title=Existing Conditions
Program Version=4.10

River Reach=UNT081 IN SUCR  ,Reach-1
Reach XY= 30
      2263137.72     13349336.85      2263101.17     13349339.28
      2263012.21     13349298.69      2262919.04     13349293.43
      2262860.81     13349245.73      2262841.89     13349143.71
      2262809.87     13349090.78      2262816.11      13349062.8
       2262881.7     13349068.28      2263013.49     13349116.89
      2263050.42     13349111.66       2263067.1     13349087.38
      2263063.87     13349029.56      2263023.81     13348998.87
      2262949.31     13348850.99      2262975.76      13348702.9
       2262775.9     13348459.31      2262733.43     13348455.75
      2262745.61     13348550.74      2262688.47     13348583.21
      2262652.12     13348569.25      2262574.86     13348484.41
      2262515.01     13348445.99      2262525.92      13348403.1
      2262606.27     13348374.08      2262623.93     13348340.25
      2262589.61     13348221.03      2262596.42     13348147.54
      2262461.22     13347990.07      2262407.72     13347956.86

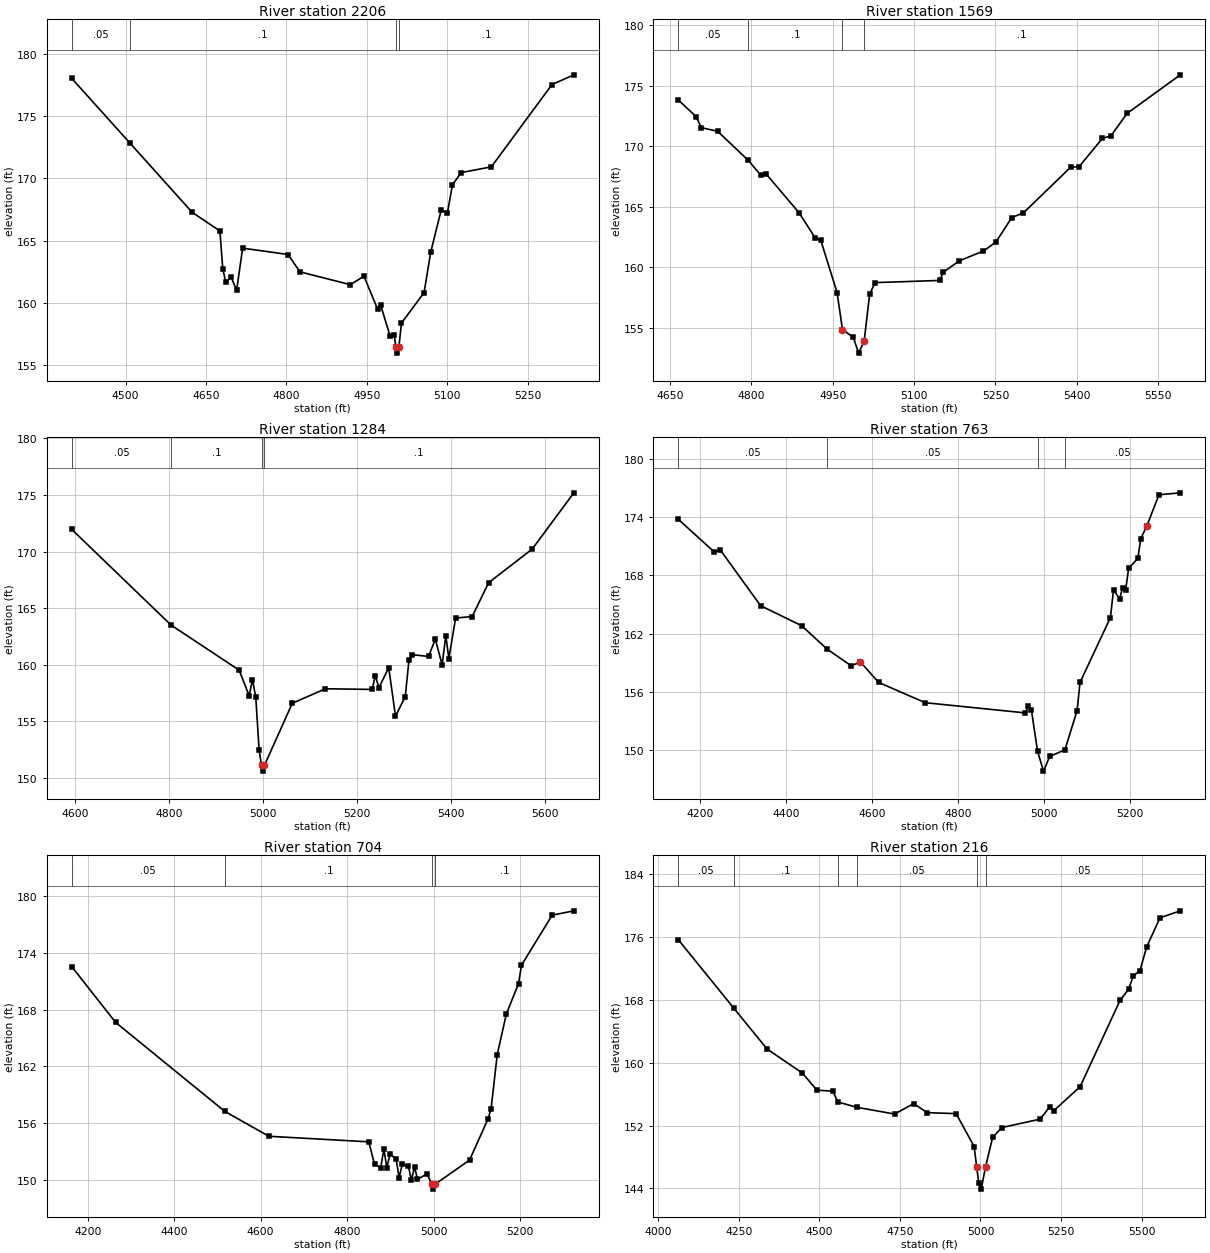
Type RM Length L Ch R = 1 ,2206    ,637,637,637
BEGIN DESCRIPTION:
UNT081 IN SUCR 3.0
END DESCRIPTION:
XS GIS Cut Line= 4
      2263408.98     13349099.72      2263047.84     13349224.73
      2262686.72     13349099.73      2262554.78     13349210.85
#Sta/Elev= 30
  4399.5  178.02  4508.2  172.83  4624.2  167.28  4675.9  165.79  4681.2  162.77
  4686.6  161.71  4697.1  162.07  4707.1  161.02  4718.3  164.41    4803   163.9
  4825.2  162.51  4919.4  161.48  4944.6  162.16  4970.4   159.5  4975.7  159.86
  4993.4  157.37  5001.6  157.41  5003.9  156.49  5006.6  155.99  5009.9  156.49
  5014.6  158.39  5056.9  160.85  5069.2  164.08  5088.7  167.46  5100.4  167.24
  5109.8  169.49  5126.2  170.47  5182.4  170.93  5295.5  177.53  5336.3  178.31
#Mann= 4 ,-1 , 0
  4399.5     .05       0  4508.2      .1       0  5003.9     .07       0
  5009.9      .1       0
Bank Sta=5003.9,5009.9
XS Rating Curve= 0 ,0
Exp/Cntr=0.3,0.1

Type RM Length L Ch R = 1 ,1569    ,806,806,806
BEGIN DESCRIPTION:
Mapping XS eec46ae7
END DESCRIPTION:
XS GIS Cut Line= 3
      2263290.43     13348857.98      2262802.18     13348868.83
      2262422.55     13349085.76
#Sta/Elev= 30
  4665.2  173.85  4697.9  172.47  4707.9  171.55  4737.9  171.25  4794.2  168.85
  4817.9   167.6  4827.9  167.69    4888  164.51    4918  162.42    4928  162.24
    4958  157.92    4968  154.86    4988  154.21  4997.7  152.91    5008  153.91
    5018  157.77    5028  158.74    5148  158.92  5153.3  159.58  5183.7  160.55
  5227.8  161.35  5250.8  162.09  5280.1  164.12  5301.7  164.51  5389.1   168.3
  5403.9  168.31  5447.1  170.66    5463  170.88  5492.7  172.73  5590.8  175.92
#Mann= 4 ,-1 , 0
  4665.2     .05       0  4794.2      .1       0    4968     .07       0
    5008      .1       0
Bank Sta=4968,5008
XS Rating Curve= 0 ,0
Exp/Cntr=0.3,0.1

Type RM Length L Ch R = 1 ,1284    ,521,521,521
BEGIN DESCRIPTION:
Mapping XS eec46ae7
END DESCRIPTION:
XS GIS Cut Line= 4
       2263241.5     13348715.01      2262973.59     13348546.31
      2262770.99     13348746.25      2262406.43     13349039.63
#Sta/Elev= 30
  4592.8  171.95  4804.2  163.51  4949.3  159.53  4970.5  157.27  4977.6   158.7
  4984.7  157.12  4991.7  152.49    4997  151.12  4999.8  150.62    5003  151.12
  5062.4  156.61  5133.1  157.89  5232.6  157.83    5239  159.05    5247  157.98
  5267.8  159.75  5282.2  155.46    5303   157.2    5311  160.46  5317.4   160.9
  5352.6  160.74    5367  162.27  5381.4  160.01  5389.4  162.56  5395.8  160.55
  5410.2  164.13  5445.4  164.26  5480.6  167.25  5573.4  170.22    5662  175.18
#Mann= 4 ,-1 , 0
  4592.8     .05       0  4804.2      .1       0    4997     .07       0
    5003      .1       0
Bank Sta=4997,5003
XS Rating Curve= 0 ,0
Exp/Cntr=0.3,0.1

Type RM Length L Ch R = 1 ,763     ,547,547,547
BEGIN DESCRIPTION:
UNT081 IN SUCR 2.0
END DESCRIPTION:
XS GIS Cut Line= 3
      2263288.27     13348693.47      2262767.45     13348353.21
       2262387.7     13348746.88
#Sta/Elev= 30
  4148.8  173.77  4233.1  170.39  4247.1  170.59  4340.6  164.88  4436.1  162.82
  4495.5  160.41  4551.8  158.69  4572.9   159.1  4615.3  156.99  4723.7   154.9
  4957.1  153.85  4964.3  154.58  4971.2  154.14  4985.4  149.92  4999.3  147.86
  5013.7  149.37  5049.2  150.05  5077.5  154.09  5084.4  156.99  5155.2  163.66
  5162.4  166.53  5176.5  165.57  5183.5  166.71  5190.7  166.53  5197.6  168.73
    5219  169.74  5225.9  171.78  5240.1  173.11  5268.3  176.29  5317.9  176.49
#Mann= 4 ,-1 , 0
  4148.8     .05       0  4495.5     .05       0  4985.4     .03       0
  5049.2     .05       0
Bank Sta=4572.9,5240.1
XS Rating Curve= 0 ,0
Exp/Cntr=0.3,0.1

Type RM Length L Ch R = 1 ,704     ,488,488,488
BEGIN DESCRIPTION:
Mapping XS eec46a
END DESCRIPTION:
XS GIS Cut Line= 3
      2263295.34     13348432.45      2262746.26     13348280.54
      2262346.93     13348716.75
#Sta/Elev= 30
  4163.3  172.53  4264.6  166.65  4517.3  157.25  4619.1  154.63    4850  154.04
  4863.6  151.67  4877.7   151.3  4885.1  153.28  4891.9  151.31  4899.3  152.76
  4913.5  152.19  4920.3  150.27  4927.7  151.68  4941.9  151.47  4948.6  149.98
  4956.1   151.4  4962.8  150.08  4984.4  150.65    4997  149.55  4999.8  149.05
    5003  149.55  5083.1  152.11  5125.6  156.42    5133  157.52  5147.2  163.24
  5168.2  167.52  5196.5  170.74  5203.3  172.68  5274.2  177.96  5324.4  178.42
#Mann= 4 ,-1 , 0
  4163.3     .05       0  4517.3      .1       0    4997     .07       0
    5003      .1       0
Bank Sta=4997,5003
XS Rating Curve= 0 ,0
Exp/Cntr=0.3,0.1

Type RM Length L Ch R = 1 ,216     ,0,0,0
BEGIN DESCRIPTION:
UNT081 IN SUCR 1.0
END DESCRIPTION:
XS GIS Cut Line= 4
      2263361.21     13348440.01      2262652.87     13348030.29
       2262423.7     13348217.79      2262312.66     13348648.09
#Sta/Elev= 30
  4061.6   175.7  4233.4     167  4337.3  161.77  4446.9   158.7  4492.3  156.52
  4541.2  156.39  4557.6  155.01  4616.6  154.33  4733.4  153.48  4792.3   154.8
  4835.3  153.65  4924.3  153.53  4980.3  149.34  4988.2  146.72  4994.6  144.72
  5002.3  143.91  5015.8  146.78  5037.7   150.5  5066.4  151.76  5185.4  152.83
  5215.6  154.43  5226.7  153.87  5309.3  156.96  5433.2  167.95  5459.6  169.36
  5474.5  171.07  5495.1  171.76  5515.8  174.75  5557.2  178.48  5620.4  179.37
#Mann= 6 ,-1 , 0
  4061.6     .05       0  4233.4      .1       0  4557.6     .05       0
  4616.6     .05       0  4988.2     .03       0  5015.8     .05       0
Bank Sta=4988.2,5015.8
XS Rating Curve= 0 ,0
Exp/Cntr=0.3,0.1

Chan Stop Cuts=-1
Use User Specified Reach Order=0
Composite Channel Slope=5