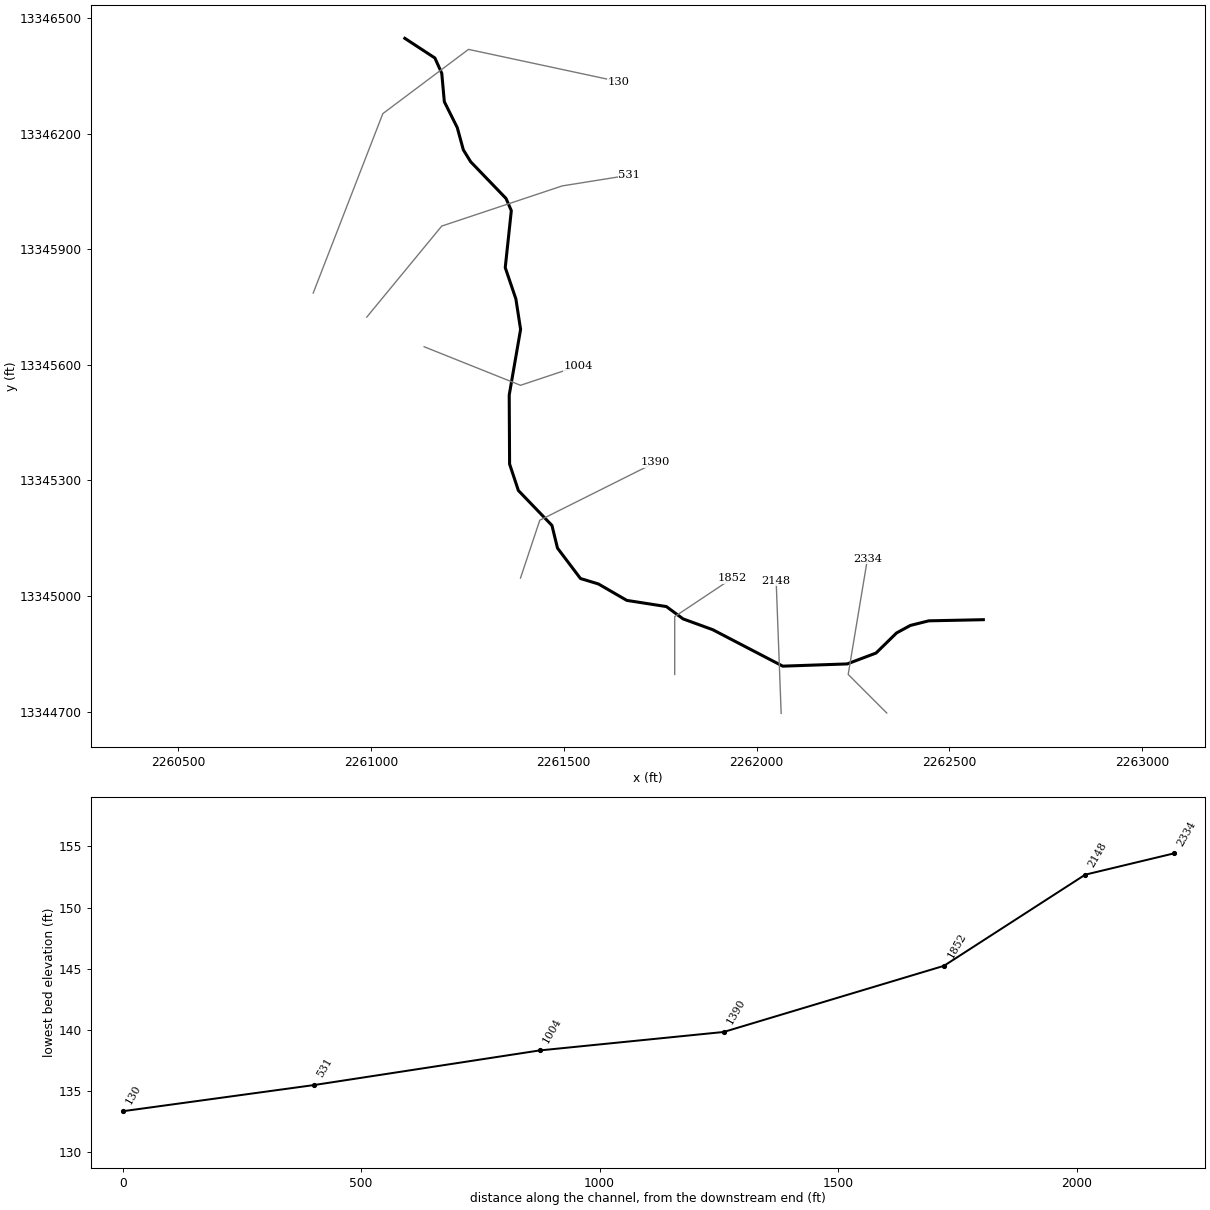
--- UNT082 IN SUCR.prj (project) ---

Proj Title=UNT082 IN SUCR Base Level Engineering
Current Plan=p01
Default Exp/Contr=0.3,0.1
English Units
Geom File=g01
Flow File=f01
Plan File=p01
BEGIN DESCRIPTION:
UNT082 IN SUCR
END DESCRIPTION:

--- UNT082 IN SUCR.p01 (plan) ---

Plan Title=Multiple Run
Short Identifier=Multiple
Geom File=g01
Flow File=f01
Subcritical Flow
K Sum by GR= 0
Std Step Tol= 0.01
Critical Tol= 0.01
Num of Std Step Trials= 20
Max Error Tol= 0.3
Flow Tol Ratio= 0.001
Split Flow NTrial= 30
Split Flow Tol= 0.02
Split Flow Ratio= 0.02
Log Output Level= 0
Friction Slope Method= 1
Unsteady Friction Slope Method= 2
Unsteady Bridges Friction Slope Method= 1
Parabolic Critical Depth
Global Vel Dist=  1 , 1 , 1
Global Log Level= 0
CheckData=True
Encroach Param= -1, 0, 0, 0
BEGIN DESCRIPTION:
Multiple Run
END DESCRIPTION:

--- UNT082 IN SUCR.f01 (steady flow) ---

Flow Title=Multiple
Number of Profiles=7
Profile Names=10-year,25-year,50-year,1pct_min,100-year,1pct_plu,500-year
River Rch & RM= UNT082 IN SUCR,Reach-1,2334
     111     148     177     156     211     286     305
Boundary for River Rch & Prof#=UNT082 IN SUCR,Reach-1,1
Up Type=0
Dn Type=3
Dn Slope=0.005
Boundary for River Rch & Prof#=UNT082 IN SUCR,Reach-1,2
Up Type=0
Dn Type=3
Dn Slope=0.005
Boundary for River Rch & Prof#=UNT082 IN SUCR,Reach-1,3
Up Type=0
Dn Type=3
Dn Slope=0.005
Boundary for River Rch & Prof#=UNT082 IN SUCR,Reach-1,4
Up Type=0
Dn Type=3
Dn Slope=0.005
Boundary for River Rch & Prof#=UNT082 IN SUCR,Reach-1,5
Up Type=0
Dn Type=3
Dn Slope=0.005
Boundary for River Rch & Prof#=UNT082 IN SUCR,Reach-1,6
Up Type=0
Dn Type=3
Dn Slope=0.005
Boundary for River Rch & Prof#=UNT082 IN SUCR,Reach-1,7
Up Type=0
Dn Type=3
Dn Slope=0.005

--- UNT082 IN SUCR.g01 (geometry) ---

Geom Title=Existing Conditions

River Reach=UNT082 IN SUCR,Reach-1
Reach XY= 30
      2262588.34     13344938.86      2262446.71     13344935.90
      2262398.96     13344923.96      2262363.16     13344904.43
      2262309.99     13344852.35      2262235.12     13344824.13
      2262067.98     13344818.34      2261886.13     13344913.01
      2261809.41     13344940.93      2261766.09     13344972.91
      2261663.50     13344988.91      2261589.80     13345031.57
      2261543.29     13345045.64      2261483.64     13345124.57
      2261469.28     13345183.40      2261382.22     13345273.93
      2261359.42     13345342.55      2261358.43     13345521.56
      2261387.95     13345691.86      2261375.70     13345771.00
      2261348.14     13345852.15      2261363.88     13345999.95
      2261350.07     13346031.60      2261258.51     13346126.63
      2261239.44     13346157.57      2261223.72     13346215.20
      2261190.15     13346282.41      2261183.47     13346356.24
      2261165.63     13346395.88      2261087.72     13346446.85

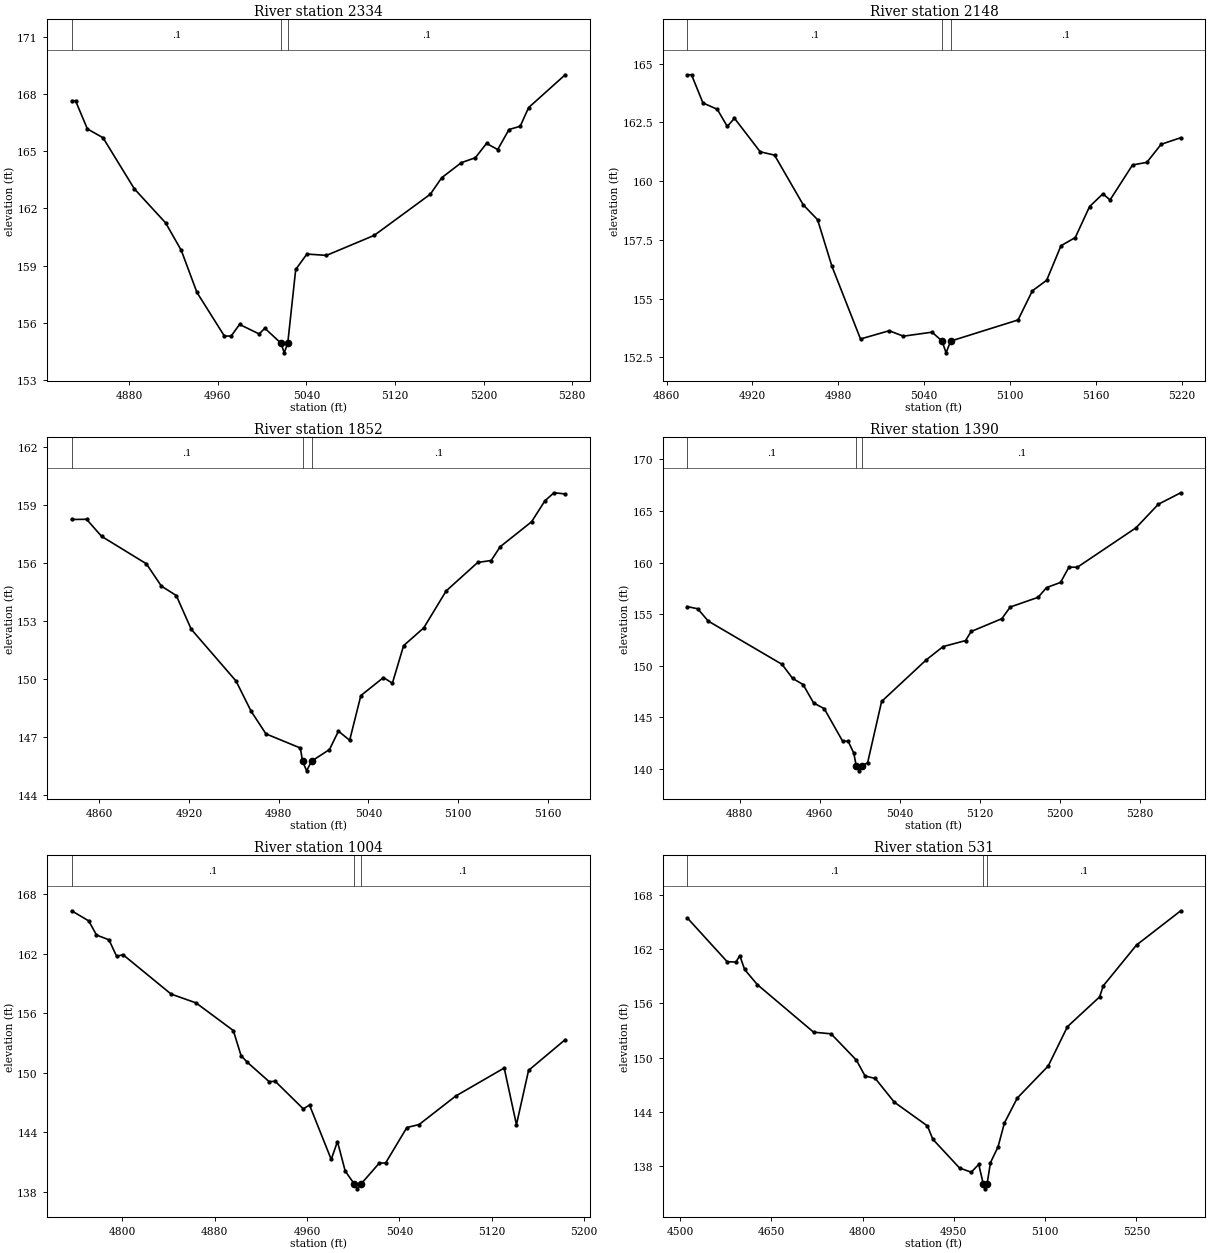
Type RM Length L Ch R = 1,2334,186,186,186
BEGIN DESCRIPTION:
UNT082 IN SUCR 5.0
END DESCRIPTION:
XS GIS Cut Line= 3
      2262337.73     13344696.85      2262237.72     13344796.85
      2262287.73     13345096.89
#Sta/Elev= 30
  4828.0  167.65  4831.5  167.65  4842.2  166.17  4856.3  165.71  4884.6  163.03
  4912.9  161.24  4927.0  159.80  4941.1  157.60  4965.9  155.31  4972.0  155.31
  4979.6  155.92  4997.3  155.42  5002.4  155.72  5017.1  154.93  5019.9  154.43
  5023.1  154.93  5030.3  158.80  5040.4  159.61  5058.1  159.54  5101.2  160.59
  5151.9  162.75  5162.1  163.61  5179.8  164.40  5192.5  164.66  5202.6  165.41
  5212.7  165.09  5222.9  166.14  5233.0  166.31  5240.6  167.29  5273.6  169.01
#Mann=3,-1,0
  4828.0     0.1       0  5017.1    0.07       0  5023.1     0.1       0
Bank Sta=5017.1,5023.1
Exp/Cntr=0.3,0.1

Type RM Length L Ch R = 1,2148,296,296,296
BEGIN DESCRIPTION:
UNT082 IN SUCR 4.1
END DESCRIPTION:
XS GIS Cut Line= 2
      2262063.85     13344695.85      2262050.83     13345040.51
#Sta/Elev= 30
  4874.4  164.53  4877.4  164.53  4885.4  163.33  4895.4  163.06  4902.4  162.33
  4907.4  162.68  4925.4  161.25  4935.4  161.11  4955.5  158.99  4965.5  158.36
  4975.5  156.38  4995.5  153.28  5015.5  153.63  5025.5  153.40  5045.5  153.57
  5052.5  153.19  5055.3  152.69  5058.5  153.19  5105.6  154.09  5115.6  155.33
  5125.6  155.78  5135.6  157.25  5145.6  157.60  5155.6  158.92  5164.9  159.46
  5169.9  159.20  5185.6  160.69  5195.6  160.80  5205.6  161.57  5219.3  161.85
#Mann=3,-1,0
  4874.4     0.1       0  5052.5    0.07       0  5058.5     0.1       0
Bank Sta=5052.5,5058.5
Exp/Cntr=0.3,0.1

Type RM Length L Ch R = 1,1852,462,462,462
BEGIN DESCRIPTION:
UNT082 IN SUCR 4.0
END DESCRIPTION:
XS GIS Cut Line= 3
      2261787.72     13344796.88      2261787.72     13344946.85
      2261937.68     13345046.83
#Sta/Elev= 30
  4841.4  158.23  4851.4  158.24  4861.4  157.36  4891.4  155.94  4901.4  154.79
  4911.4  154.30  4921.4  152.56  4951.4  149.88  4961.4  148.33  4971.4  147.15
  4994.4  146.42  4995.9  145.74  4998.6  145.24  5001.9  145.74  5013.9  146.34
  5019.9  147.29  5027.4  146.82  5034.9  149.13  5050.0  150.06  5056.0  149.77
  5063.5  151.71  5077.0  152.63  5092.0  154.54  5113.1  156.01  5122.1  156.11
  5128.1  156.82  5149.1  158.11  5158.1  159.20  5164.1  159.61  5171.6  159.55
#Mann=3,-1,0
  4841.4     0.1       0  4995.9    0.07       0  5001.9     0.1       0
Bank Sta=4995.9,5001.9
Exp/Cntr=0.3,0.1

Type RM Length L Ch R = 1,1390,386,386,386
BEGIN DESCRIPTION:
UNT082 IN SUCR 3.0
END DESCRIPTION:
XS GIS Cut Line= 3
      2261387.73     13345046.89      2261437.72     13345196.85
      2261737.74     13345346.86
#Sta/Elev= 30
  4827.5  155.73  4838.0  155.52  4848.5  154.33  4922.3  150.14  4932.9  148.78
  4943.4  148.18  4953.9  146.40  4964.5  145.85  4982.9  142.70  4988.4  142.70
  4994.0  141.56  4996.5  140.33  4999.3  139.83  5002.5  140.33  5007.9  140.62
  5021.9  146.55  5066.6  150.58  5083.4  151.86  5105.8  152.44  5111.4  153.32
  5142.1  154.56  5150.5  155.69  5178.4  156.63  5186.8  157.57  5200.8  158.07
  5209.2  159.55  5217.6  159.54  5276.3  163.36  5298.6  165.64  5321.0  166.75
#Mann=3,-1,0
  4827.5     0.1       0  4996.5    0.07       0  5002.5     0.1       0
Bank Sta=4996.5,5002.5
Exp/Cntr=0.3,0.1

Type RM Length L Ch R = 1,1004,473,473,473
BEGIN DESCRIPTION:
UNT082 IN SUCR 2.0
END DESCRIPTION:
XS GIS Cut Line= 3
      2261137.74     13345646.85      2261387.72     13345546.85
      2261537.76     13345596.87
#Sta/Elev= 30
  4756.2  166.30  4771.0  165.28  4777.7  163.86  4788.5  163.38  4795.2  161.70
  4800.6  161.89  4842.3  157.92  4863.9  157.03  4896.2  154.25  4902.9  151.73
  4908.3  151.06  4927.2  149.11  4932.5  149.14  4956.8  146.37  4962.2  146.75
  4981.0  141.28  4986.4  143.08  4993.1  140.11  5000.9  138.82  5003.6  138.32
  5006.9  138.82  5022.7  140.92  5028.1  140.92  5046.5  144.49  5057.1  144.79
  5088.7  147.65  5130.8  150.48  5141.4  144.78  5151.9  150.24  5183.6  153.33
#Mann=3,-1,0
  4756.2     0.1       0  5000.9    0.07       0  5006.9     0.1       0
Bank Sta=5000.9,5006.9
Exp/Cntr=0.3,0.1

Type RM Length L Ch R = 1,531,401,401,401
BEGIN DESCRIPTION:
Mapping XS 27ff6c4d
END DESCRIPTION:
XS GIS Cut Line= 4
      2260988.92     13345723.72      2261183.39     13345959.86
      2261495.89     13346064.03      2261669.47     13346091.80
#Sta/Elev= 30
  4511.9  165.47  4577.5  160.62  4591.9  160.58  4598.3  161.29  4606.2  159.76
  4627.0  158.09  4719.6  152.82  4748.3  152.64  4789.9  149.73  4804.2  147.97
  4821.0  147.70  4852.2  145.08  4906.7  142.45  4915.5  140.98  4959.4  137.80
  4978.7  137.33  4991.0  138.20  4998.6  135.99  5001.3  135.49  5004.6  135.99
  5010.3  138.39  5022.7  140.13  5033.2  142.77  5054.3  145.53  5105.2  149.08
  5136.8  153.43  5189.6  156.72  5195.7  157.95  5250.3  162.46  5323.0  166.25
#Mann=3,-1,0
  4511.9     0.1       0  4998.6    0.07       0  5004.6     0.1       0
Bank Sta=4998.6,5004.6
Exp/Cntr=0.3,0.1

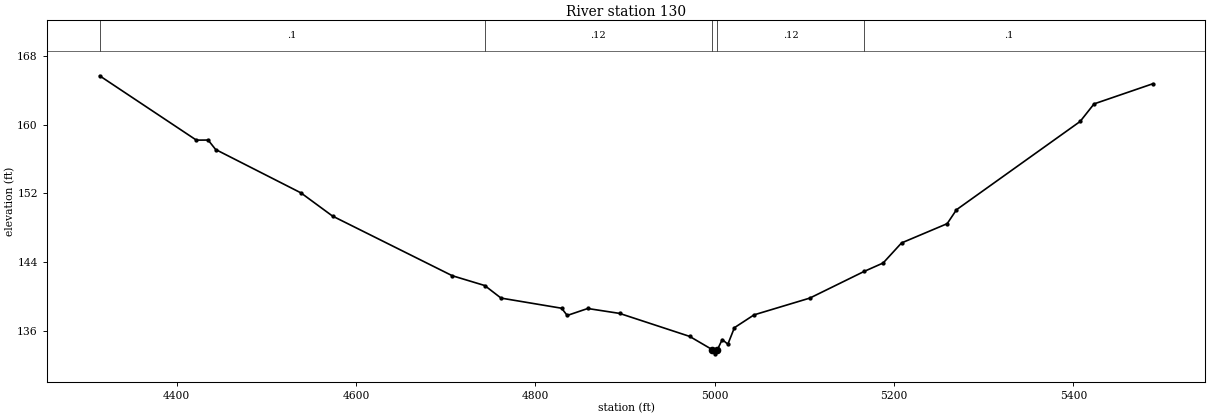
Type RM Length L Ch R = 1,130,0,0,0
BEGIN DESCRIPTION:
UNT082 IN SUCR 1.0
END DESCRIPTION:
XS GIS Cut Line= 4
      2260850.05     13345786.23      2261030.61     13346251.53
      2261252.83     13346418.19      2261641.73     13346334.86
#Sta/Elev= 30
  4314.0  165.67  4421.9  158.19  4435.0  158.20  4443.4  157.10  4538.5  152.06
  4573.8  149.36  4707.3  142.43  4743.5  141.29  4761.7  139.83  4829.3  138.65
  4835.5  137.81  4858.4  138.62  4893.9  138.05  4972.0  135.38  4997.1  133.85
  4999.9  133.35  5003.1  133.85  5008.4  135.01  5014.7  134.47  5022.0  136.39
  5043.9  137.88  5106.1  139.83  5166.7  142.93  5187.9  143.91  5208.4  146.24
  5259.3  148.48  5269.7  150.10  5407.6  160.36  5423.1  162.40  5488.6  164.74
#Mann=5,-1,0
  4314.0     0.1       0  4743.5    0.12       0  4997.1    0.07       0
  5003.1    0.12       0  5166.7     0.1       0
Bank Sta=4997.1,5003.1
Exp/Cntr=0.3,0.1

Chan Stop Cuts=-1